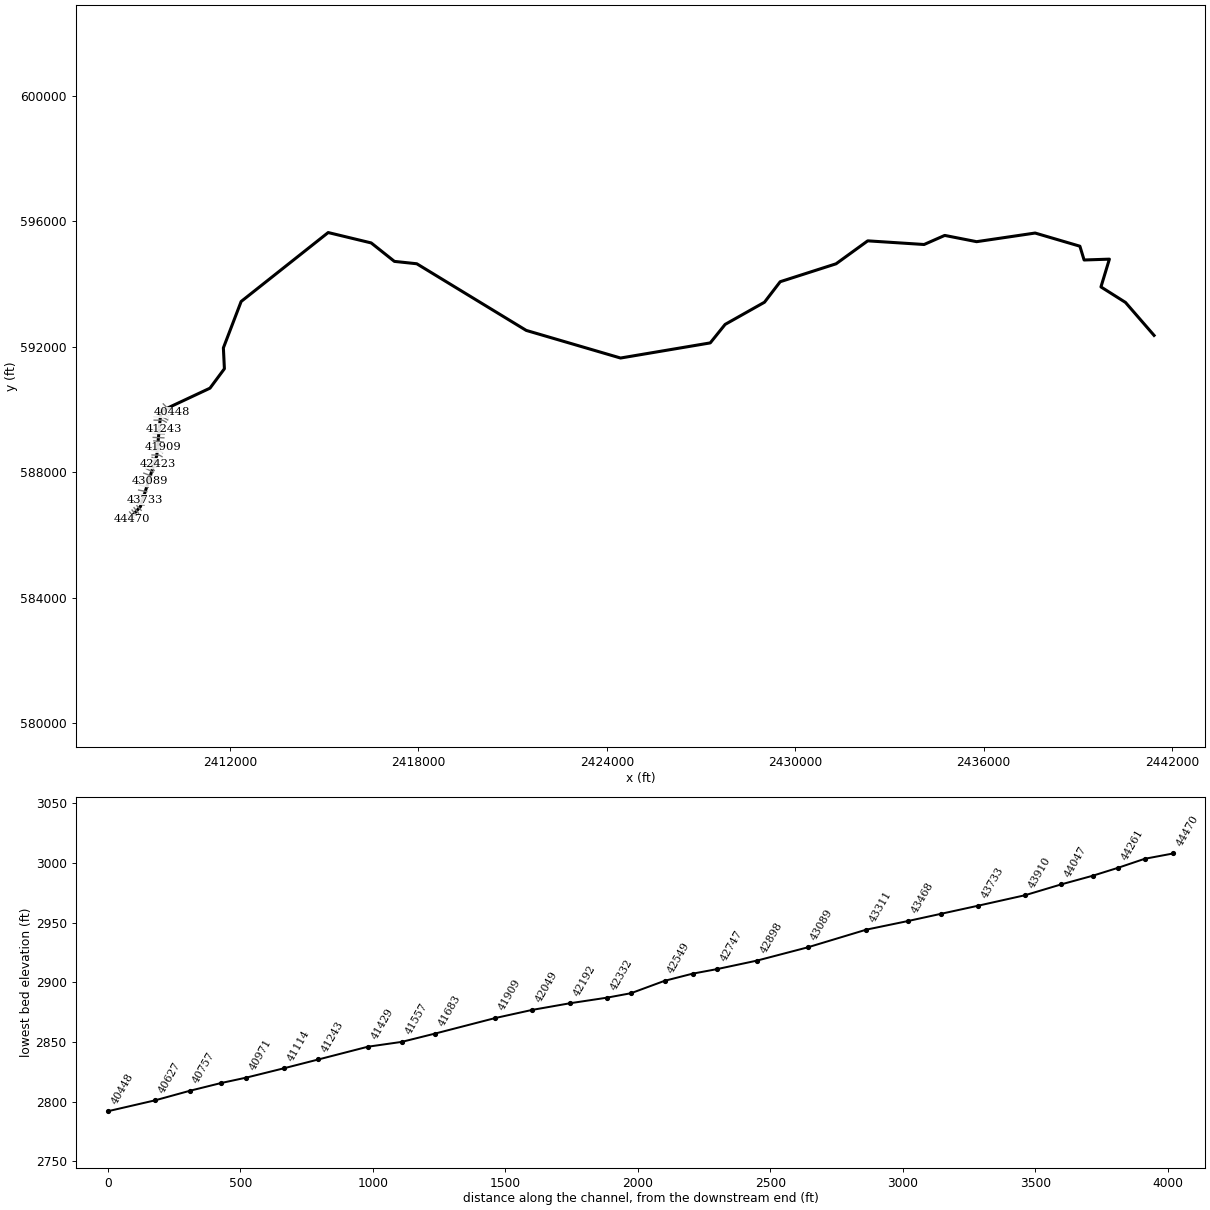
--- SMITHCK.prj (project) ---

Proj Title=SMITHCK
Current Plan=p01
Default Exp/Contr=0,0
English Units
Geom File=g01
Flow File=f01
Plan File=p01
BEGIN DESCRIPTION:
Stream Name: Smith Creek
Flood Zone: Approximate
Pendleton County, West Virginia
HEC-RAS Version: 5.0.7
Hydrology Method:
Regression
Model Notes:
NA
END DESCRIPTION:
DSS File=dss
DSS Export Rating Curves= 0
DSS Export Rating Curve Sorted= 0
DSS Export Volume Flow Curves= 0
DXF OffsetX= 0
DXF OffsetY= 0
DXF ScaleX= 0
DXF ScaleY= 0

--- SMITHCK.p01 (plan) ---

Plan Title=Floodplain
Program Version=5.07
Short Identifier=Floodplain
Geom File=g01
Flow File=f01
Subcritical Flow
K Sum by GR= 0
Std Step Tol= 0.01
Critical Tol= 0.01
Num of Std Step Trials= 20
Max Error Tol= 0.3
Flow Tol Ratio= 0.001
Split Flow NTrial= 30
Split Flow Tol= 0.02
Split Flow Ratio= 0.02
Log Output Level= 0
Friction Slope Method= 1
Unsteady Friction Slope Method= 2
Unsteady Bridges Friction Slope Method= 1
Parabolic Critical Depth
Global Vel Dist= 0 , 0 , 0
Global Log Level= 0
CheckData=True
Encroach Param=-1 ,0,0, 0
Computation Interval=0.1SEC
Output Interval=1MIN
Instantaneous Interval=Max Profile
Mapping Interval=1HOUR
Computation Time Step Use Courant=        0
Computation Time Step Use Time Series=    0
Computation Time Step Count To Double=0
Computation Time Step Max Doubling=0
Computation Time Step Max Halving=0
Computation Time Step Residence Courant=0
Run HTab= 0
Run UNet= 0
Run Sediment= 0
Run PostProcess= 0
Run WQNet= 0
Run RASMapper= 0
UNET Theta= 0
UNET Theta Warmup= 0
UNET ZTol= 0
UNET ZSATol= 0
UNET MxIter= 0
UNET Max Iter WO Improvement= 0
UNET MaxInSteps= 0
UNET DtIC= 0
UNET DtMin= 0
UNET MaxCRTS= 0
UNET WFStab= 0
UNET SFStab= 0
UNET WFX= 1
UNET SFX= 1
UNET 1D Methodology=Finite Difference
UNET DSS MLevel= 1
UNET Pardiso=0
UNET DZMax Abort= 0
UNET Use Existing IB Tables= 0
UNET Froude Reduction=False
UNET Froude Limit= 0
UNET Froude Power= 0
UNET D1 Cores= 0
UNET D2 Coriolis=0
UNET D2 Cores= 0
UNET D2 Theta= 1
UNET D2 Theta Warmup= 1
UNET D2 Z Tol= 0.01
UNET D2 Volume Tol= 0.01
UNET D2 Max Iterations= 20
UNET D2 Equation= 0
UNET D2 RampUpFraction=0.1
UNET D2 TimeSlices= 1
UNET D2 BCVolumeCheck=0
UNET D1D2 MaxIter= 0
UNET D1D2 ZTol=0.01
UNET D1D2 QTol=0.1
UNET D1D2 MinQTol=1
DSS File=dss
Write IC File= 0
Write IC File at Fixed DateTime=0
Write IC File at Sim End=0
Echo Input=False
Echo Parameters=False
Echo Output=False
Write Detailed= 0
HDF Write Warmup=0
HDF Write Time Slices=0
HDF Flush=0
HDF Face Node Velocities=0
HDF Compression= 1
HDF Chunk Size= 1
HDF Spatial Parts= 1
HDF Use Max Rows=0
HDF Fixed Rows= 1
Calibration Method= 0
Calibration Iterations= 20
Calibration Max Change=0.05
Calibration Tolerance=0.2
Calibration Maximum=1.5
Calibration Minimum=0.5
Calibration Optimization Method= 1
WQ AD Non Conservative
WQ ULTIMATE=-1
WQ Max Comp Step=1HOUR
WQ Output Interval=15MIN
WQ Output Selected Increments= 0
WQ Output face flow=0
WQ Output face velocity=0
WQ Output face area=0
WQ Output face dispersion=0
WQ Output cell volume=0
WQ Output cell surface area=0
WQ Output cell continuity=0
WQ Output cumulative cell continuity=0
WQ Output face conc=0
WQ Output face dconc_dx=0
WQ Output face courant=0
WQ Output face peclet=0
WQ Output face adv mass=0
WQ Output face disp mass=0
WQ Output cell mass=0
WQ Output cell source sink temp=0
WQ Output nsm pathways=0
WQ Output nsm derived pathways=0
WQ Output MaxMinRange=-1
WQ Daily Max Min Mean=-1
WQ Daily Range=0
WQ Daily Time=0
WQ Create Restart=0
WQ Fixed Restart=0
WQ System Summary=0
WQ Write To DSS=0
WQ Use Fixed Temperature=0
Sorting and Armoring Iterations= 10
XS Update Threshold= 0.02
Bed Roughness Predictor= 0
Hydraulics Update Threshold= 0.02
Energy Slope Method= 1
Volume Change Method= 1
Sediment Retention Method= 0
XS Weighting Method= 0
Number of US Weighted Cross Sections= 1
Number of DS Weighted Cross Sections= 1
Upstream XS Weight=0
Main XS Weight=1
Downstream XS Weight=0
Number of DS XS's Weighted with US Boundary= 1
Upstream Boundary Weight= 1
Weight of XSs Associated with US Boundary= 0
Number of US XS's Weighted with DS Boundary= 1
Downstream Boundary Weight= 0.5
Weight of XSs Associated with DS Boundary= 0.5
Percentile Method= 0
Sediment Output Level= 3
Mass or Volume Output= 0
Output Increment Type= 1
Profile and TS Output Increment= 1
XS Output Flag= 0
XS Output Increment= 10
Write Gradation File= 0
Read Gradation Hotstart= 0
Write HDF5 File= 1
Write Binary Output= 1
Write DSS Sediment File= 0
SV Curve= 0
Specific Gage Flag= 0

--- SMITHCK.f01 (steady flow) ---

Flow Title=Flows
Program Version=5.07
Number of Profiles= 6
Profile Names=P100yr,P10yr,P25yr,P50yr,P500yr,P101yr
River Rch & RM=SMITHCK,Main            ,44470
     587     274     388     484     860     714
River Rch & RM=SMITHCK,Main            ,43089
     653     305     431     539     958     794
River Rch & RM=SMITHCK,Main            ,40072
    1003     465     660     826    1478    1220
River Rch & RM=SMITHCK,Main            ,37792
    1202     556     790     990    1776    1463
River Rch & RM=SMITHCK,Main            ,35109
    1340     619     880    1103    1982    1631
River Rch & RM=SMITHCK,Main            ,33627
    1548     713    1015    1273    2292    1883
River Rch & RM=SMITHCK,Main            ,30283
    2369    1085    1548    1946    3524    2883
River Rch & RM=SMITHCK,Main            ,26947
    2637    1205    1722    2165    3927    3209
River Rch & RM=SMITHCK,Main            ,23832
    3270    1490    2131    2683    4881    3979
River Rch & RM=SMITHCK,Main            ,17045
    3693    1679    2404    3029    5519    4494
River Rch & RM=SMITHCK,Main            ,13660
    4103    1863    2669    3364    6140    4994
Boundary for River Rch & Prof#=SMITHCK,Main            , 1
Up Type= 0
Dn Type= 3
Dn Slope=0.015822
Boundary for River Rch & Prof#=SMITHCK,Main            , 2
Up Type= 0
Dn Type= 3
Dn Slope=0.015822
Boundary for River Rch & Prof#=SMITHCK,Main            , 3
Up Type= 0
Dn Type= 3
Dn Slope=0.015822
Boundary for River Rch & Prof#=SMITHCK,Main            , 4
Up Type= 0
Dn Type= 3
Dn Slope=0.015822
Boundary for River Rch & Prof#=SMITHCK,Main            , 5
Up Type= 0
Dn Type= 3
Dn Slope=0.015822
Boundary for River Rch & Prof#=SMITHCK,Main            , 6
Up Type= 0
Dn Type= 3
Dn Slope=0.015822
DSS Import GetInterval= 0
DSS Import GetPeak= 0
DSS Import FillOption= 0

--- SMITHCK.g01 (geometry) ---

Geom Title=Geometry
Program Version=5.07

River Reach=SMITHCK         ,Main
Reach XY= 30
     2408804.921      586531.1912409141.90100002586908.819999993
2409664.22000003588536.8350000082409794.96700004589951.877000019
2411358.59098393590684.914846763     2411817.919      591303.978
2411785.64399999591968.8460000012412351.46600002593447.876000002
2415124.17899999595645.1270000192416494.92700002 595313.92400001
2417233.37600002 594725.760000022417946.06500003594650.180999994
2421432.46599999592525.8620000182424437.10600001591645.591000006
2427294.95200002592127.9420000022427768.28799999592717.177000001
2429022.04800001593424.2660000032429522.55600002594077.958000019
2431302.59700003594649.2290000022432310.74800003595380.560000002
2434106.23500001595264.1450000112434763.45000002595553.613999993
2435779.03299999595354.078000009     2437643.067595629.384000003
2439069.09900001595209.6900000132439203.14199999594770.232999995
2440008.90500003594797.3400000182439739.99000001593911.931999996
     2440521.609593417.8200000082441432.16735005592366.754877493

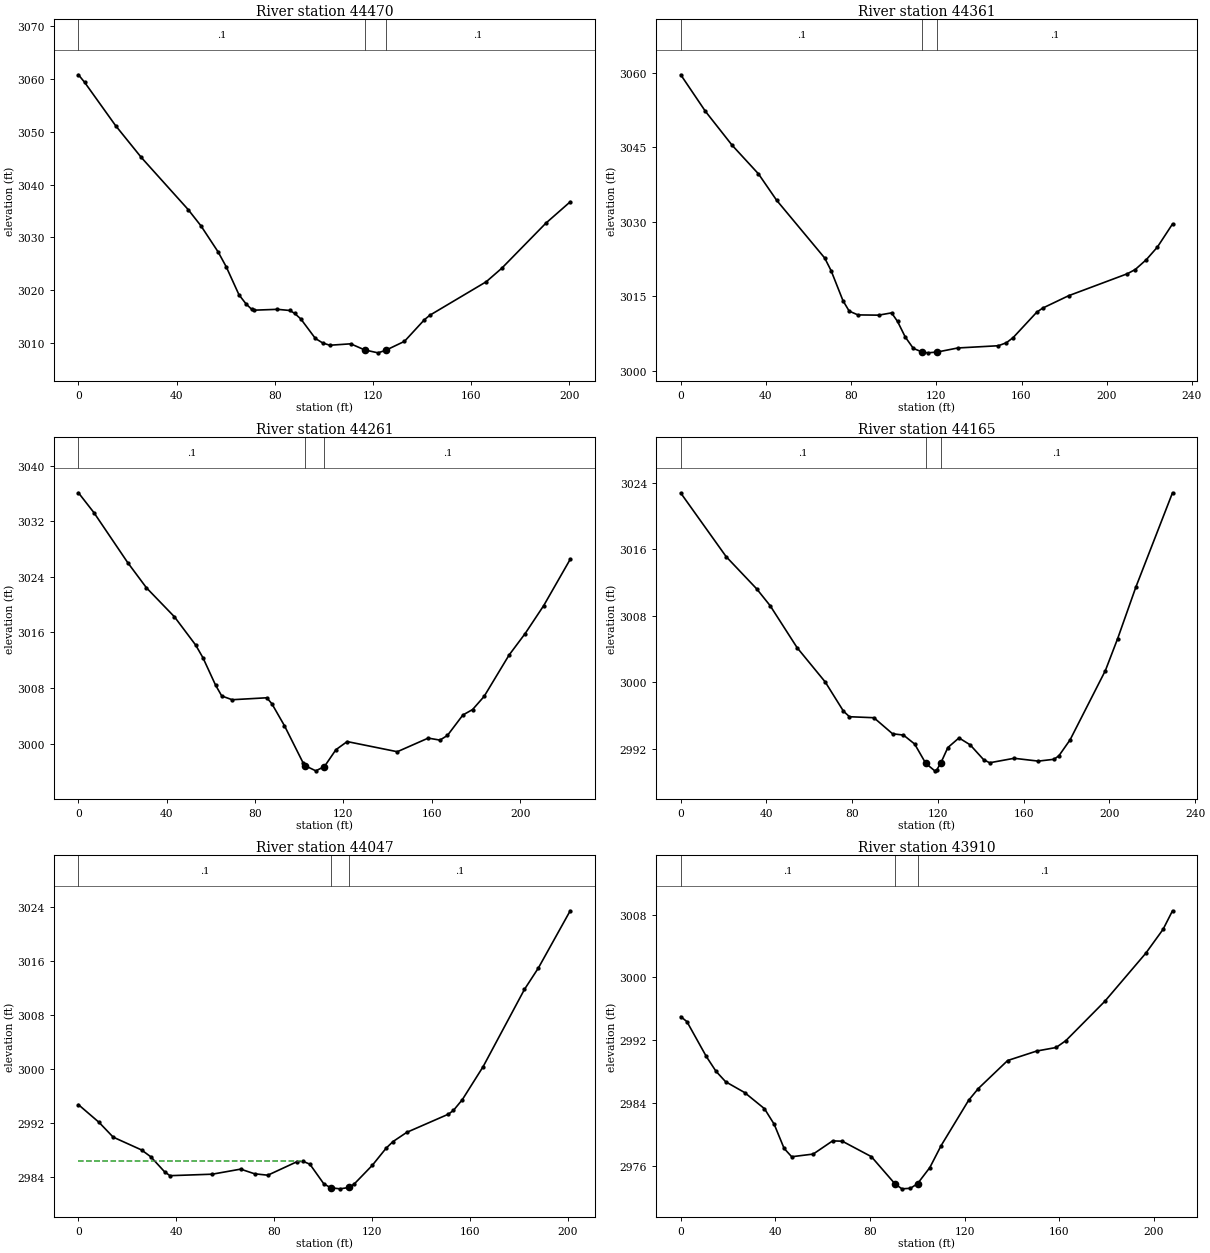
Type RM Length L Ch R = 1 ,44470   ,110.1,108.4,107.3
XS GIS Cut Line= 2
2408723.54425983586637.0246906942408878.16468401586509.690223724
#Sta/Elev= 30
       0 3060.81     2.5 3059.39    15.1 3051.19    25.6 3045.14    44.7 3035.25
    49.9 3032.17    56.9 3027.22    60.2  3024.4    65.4 3019.09    68.3 3017.35
    70.6 3016.33    71.7 3016.18      81 3016.34    86.1 3016.12    88.1 3015.56
    90.6  3014.5    96.5 3010.82    99.5 3009.96   102.4 3009.53   110.9  3009.8
   116.6 3008.64     122 3008.09   125.1 3008.56   132.8 3010.27   140.9 3014.36
   143.1 3015.21   166.1 3021.57   172.4 3024.12   190.4 3032.68   200.3 3036.72
#Mann= 3 ,-1 , 0
       0      .1       0   116.6    .045       0   125.1      .1       0
Bank Sta=116.6,125.1
XS Rating Curve= 0 ,0
Exp/Cntr(USF)=0,0
Exp/Cntr=0.3,0.1

Type RM Length L Ch R = 1 ,44361   ,99.6,99.8,99.6
XS GIS Cut Line= 2
2408798.58064215586739.3470302232408946.37957703586561.988308372
#Sta/Elev= 30
       0 3059.58    11.6 3052.21    24.1  3045.4    36.5 3039.62      45 3034.32
    67.6 3022.67    70.6 3020.13    76.2 3014.06    79.1 3011.98    83.2 3011.22
    92.9 3011.17      99 3011.63   101.8  3009.9   105.4 3006.78   109.2 3004.48
  113.383003.737     116 3003.58  120.493003.748   130.1 3004.56   149.1 3005.01
   152.9 3005.61   156.1 3006.66   167.1 3011.74   169.9 3012.58   182.1 3015.08
   209.7 3019.51   213.4 3020.36   218.6 3022.34   223.8 3024.88   230.9 3029.53
#Mann= 3 ,-1 , 0
       0      .1       0  113.38    .045       0  120.49      .1       0
Bank Sta=113.38,120.49
XS Rating Curve= 0 ,0
Exp/Cntr(USF)=0,0
Exp/Cntr=0.3,0.1

Type RM Length L Ch R = 1 ,44261   ,96.4,96.5,96.4
XS GIS Cut Line= 2
2408875.89085424586800.7404339412409019.14212958586630.203201392
#Sta/Elev= 30
       0 3036.09       7 3033.24    22.3 3026.05    30.8 3022.42    43.5 3018.24
    53.1 3014.18    56.4 3012.35    62.1 3008.42    64.9 3006.86    69.6 3006.32
    85.3  3006.6    87.6 3005.74    93.3 3002.58   101.8  2997.2  102.812996.808
   107.5 2996.09  111.412996.714   116.6 2999.13   121.7  3000.3   144.4 2998.84
   158.4  3000.8   163.7 3000.51   167.1 3001.18   174.1 3004.12   178.5 3004.91
   183.7 3006.79     195 3012.74   202.3 3015.84   210.7 3019.86   222.7 3026.52
#Mann= 3 ,-1 , 0
       0      .1       0  102.81    .045       0  111.41      .1       0
Bank Sta=102.81,111.41
XS Rating Curve= 0 ,0
Exp/Cntr(USF)=0,0
Exp/Cntr=0.3,0.1

Type RM Length L Ch R = 1 ,44165   ,117.1,117.8,118.4
XS GIS Cut Line= 2
2408939.55808773586875.7768162632409085.08319283586698.418094411
#Sta/Elev= 30
       0 3022.79    21.2 3015.13    35.4 3011.27    41.7 3009.24    54.3 3004.18
    67.4 3000.06    75.9 2996.55    78.7 2995.88    90.1 2995.76    98.8 2993.83
   103.9 2993.67   109.1  2992.6  114.312990.267   118.5 2989.37   119.5 2989.51
  121.412990.366   124.6 2992.17   129.8 2993.33     135  2992.5   141.3 2990.71
   144.1 2990.34   155.5 2990.88   166.8 2990.54   174.1 2990.76   176.4 2991.18
   181.6 2993.09   198.1 3001.44   203.8 3005.27   212.3 3011.47   229.4 3022.82
#Mann= 3 ,-1 , 0
       0      .1       0  114.31    .045       0  121.41      .1       0
Bank Sta=114.31,121.41
XS Rating Curve= 0 ,0
Exp/Cntr(USF)=0,0
Exp/Cntr=0.3,0.1

Type RM Length L Ch R = 1 ,44047   ,131.4,137.3,141.7
XS GIS Cut Line= 2
2409028.23744865586939.4440497482409166.94106446586793.918944639
#Sta/Elev= 30
       0 2994.67     8.4 2992.06    14.2 2989.86    25.8 2987.96    29.6 2986.94
    35.2 2984.73    37.4 2984.15    54.7 2984.37    66.3 2985.12      72 2984.43
    77.4 2984.22    89.5 2986.25    91.8 2986.28    94.6 2985.85   100.3 2982.94
  103.122982.359   106.9  2982.2  110.622982.404   112.7 2982.91   120.1 2985.68
   125.8 2988.24   128.6 2989.21   134.2 2990.57   151.2 2993.26   153.3 2993.83
   156.9 2995.41   165.4  3000.3   182.3 3011.75     188 3014.93     201  3023.4
#Mann= 3 ,-1 , 0
       0      .1       0  103.12    .045       0  110.62      .1       0
#XS Ineff= 2 , 0
           91.39 2986.33
Permanent Ineff=
       F       F
Bank Sta=103.12,110.62
XS Rating Curve= 0 ,0
Exp/Cntr(USF)=0,0
Exp/Cntr=0.3,0.1

Type RM Length L Ch R = 1 ,43910   ,176,176.8,177.4
XS GIS Cut Line= 2
2409055.52340586   587005.3851132409257.89425515586957.634687886
#Sta/Elev= 30
       0    2995     2.6 2994.37    10.8 2989.93    14.9 2988.04      19  2986.7
      27 2985.33    35.4 2983.27    39.5 2981.29    43.7 2978.21    46.9 2977.15
      56 2977.49    64.2 2979.17    68.3 2979.13    80.6 2977.16   90.612973.681
    93.5 2973.06    97.1 2973.13  100.112973.722   105.3 2975.77   110.1 2978.58
   121.7 2984.34   125.8 2985.84   138.2 2989.41   150.5 2990.62   158.7 2991.07
   162.8 2991.94   179.3 2996.96   196.6 3003.08   203.9 3006.12   207.9 3008.49
#Mann= 3 ,-1 , 0
       0      .1       0   90.61    .045       0  100.11      .1       0
#XS Ineff= 2 , 0
           67.51 2977.42
Permanent Ineff=
       F       F
Bank Sta=90.61,100.11
XS Rating Curve= 0 ,0
Exp/Cntr(USF)=0,0
Exp/Cntr=0.3,0.1

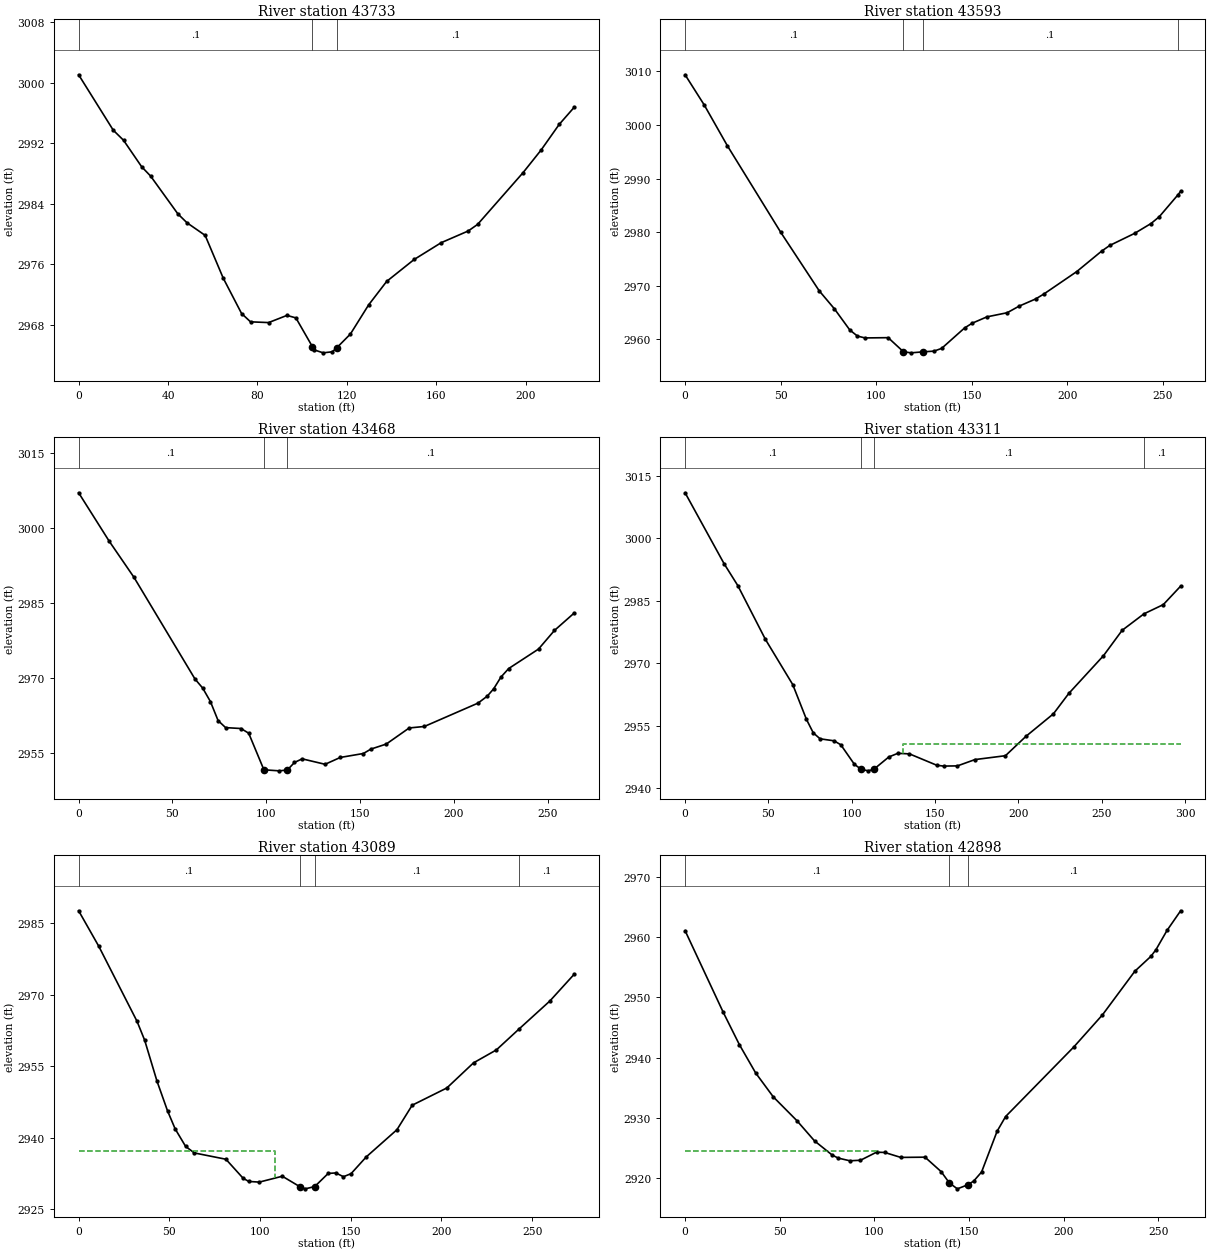
Type RM Length L Ch R = 1 ,43733   ,137,140,142
XS GIS Cut Line= 2
2409078.26170353587173.6485157822409296.54936119587134.993409737
#Sta/Elev= 30
       0 3001.05    15.5 2993.72    20.1 2992.39    28.2 2988.89    32.2 2987.66
    44.4 2982.66    48.5 2981.48    56.6 2979.82    64.7 2974.16    72.9 2969.49
    76.9 2968.39      85 2968.29    93.2 2969.24    97.2 2968.91  104.612965.095
   105.3 2964.69   109.4 2964.29   113.5 2964.43  115.592964.988   121.6 2966.78
   129.7 2970.61   137.8 2973.73   150.1 2976.63   162.2 2978.85   174.3  2980.4
   178.5 2981.27   198.8  2988.1   206.9  2991.1     215 2994.49   221.7 2996.75
#Mann= 3 ,-1 , 0
       0      .1       0  104.61    .045       0  115.59      .1       0
Bank Sta=104.61,115.59
XS Rating Curve= 0 ,0
Exp/Cntr(USF)=0,0
Exp/Cntr=0.3,0.1

Type RM Length L Ch R = 1 ,43593   ,128.6,124.8,122.8
XS GIS Cut Line= 3
2409075.98787376 587285.066174382409244.25127655587296.435323217
2409328.38297794587262.327876707
#Sta/Elev= 30
       0 3009.36      10 3003.74    22.1 2996.14    50.1 2979.96    70.2 2969.07
    78.2 2965.69    86.2 2961.77    90.2 2960.63    94.2 2960.28   106.3 2960.33
  114.312957.699   118.3  2957.5  124.41 2957.68   130.3 2957.82   134.3 2958.33
   146.3 2962.14   150.3 2963.03     158 2964.21   168.6 2964.98   174.8  2966.2
   183.5 2967.55   187.8 2968.47     205 2972.65     218 2976.46   222.3 2977.53
   235.3 2979.78   243.9 2981.62   248.2 2982.88  257.772986.876   259.4 2987.61
#Mann= 4 ,-1 , 0
       0      .1       0  114.31    .045       0  124.41      .1       0
  257.77      .1       0
Bank Sta=114.31,124.41
XS Rating Curve= 0 ,0
Exp/Cntr(USF)=0,0
Exp/Cntr=0.3,0.1

Type RM Length L Ch R = 1 ,43468   ,157.6,157.6,157.1
XS GIS Cut Line= 2
2409085.08319283587437.4127687912409344.29978631 587387.38851391
#Sta/Elev= 30
       0 3007.09    16.2 2997.45    29.5 2990.16      62 2969.81    66.1    2968
    70.2 2965.31    74.3  2961.5    78.3 2960.09    86.5 2959.91    90.6 2958.97
    98.7 2951.65   106.8 2951.44  111.18  2951.6     115 2953.12   119.1 2953.84
   131.3 2952.75   139.4 2954.12   151.7 2954.91   155.7 2955.79   163.9  2956.8
   176.1 2960.02   184.2 2960.32   212.8    2965   217.7 2966.39   221.1 2967.85
     225 2970.21   229.1 2971.91     245 2975.81   253.5 2979.54     264 2983.02
#Mann= 3 ,-1 , 0
       0      .1       0    98.7    .045       0  111.18      .1       0
Bank Sta=98.7,111.18
XS Rating Curve= 0 ,0
Exp/Cntr(USF)=0,0
Exp/Cntr=0.3,0.1

Type RM Length L Ch R = 1 ,43311   ,222.4,222,221.2
XS GIS Cut Line= 2
2409103.27383097 587598.854682272409392.05021142587528.365959484
#Sta/Elev= 30
       0 3010.91    23.4 2993.89    31.6 2988.66    48.2 2975.73    64.6 2964.88
    72.8 2956.55    76.9 2953.31      81 2951.88    89.3 2951.41    93.4 2950.46
   101.6 2945.75  105.682944.556   109.9  2944.2  113.282944.588   122.2 2947.52
   127.6  2948.4   134.6 2948.27     151 2945.54   155.1 2945.34   163.4 2945.39
   173.9  2946.9   192.2 2947.83   204.5 2952.48     221 2957.89   230.2 2962.77
     251 2971.82   262.2 2977.91   275.32981.868   286.9 2984.08   297.3 2988.51
#Mann= 4 ,-1 , 0
       0      .1       0  105.68    .045       0  113.28      .1       0
   275.3      .1       0
#XS Ineff= 2 , 0
                          130.71         2950.68
Permanent Ineff=
       F       F
Bank Sta=105.68,113.28
XS Rating Curve= 0 ,0
Exp/Cntr(USF)=0,0
Exp/Cntr=0.3,0.1

Type RM Length L Ch R = 1 ,43089   ,190.5,190.8,190.3
XS GIS Cut Line= 2
2409171.48872399587803.4993613292409430.70531747587717.093830171
#Sta/Elev= 30
       0 2987.57    11.1 2980.14    32.2 2964.41    36.4 2960.46    43.2 2951.88
      49 2945.67    53.2 2941.89      59  2938.2    63.8 2936.84    81.2 2935.52
    90.7 2931.53    93.8 2930.87    99.6 2930.73   112.3 2931.96  121.822929.803
   124.9 2929.32  130.152929.795   137.6 2932.55   141.8 2932.65     146 2931.86
   150.2  2932.5   158.6 2936.02   175.5 2941.71   183.9 2946.84     203 2950.45
   217.7 2955.71   230.3 2958.42  243.012962.875   259.8 2968.67   273.2 2974.27
#Mann= 4 ,-1 , 0
       0      .1       0  121.82    .045       0  130.15      .1       0
  243.01      .1       0
#XS Ineff= 2 , 0
          108.44 2937.17
Permanent Ineff=
       F       F
Bank Sta=121.82,130.15
XS Rating Curve= 0 ,0
Exp/Cntr(USF)=0,0
Exp/Cntr=0.3,0.1

Type RM Length L Ch R = 1 ,42898   ,152,150.8,149.6
XS GIS Cut Line= 2
2409251.07276585587976.3104236462409496.64638072587885.357232953
#Sta/Elev= 30
       0 2961.05    20.2 2947.49    28.7 2942.15    37.3 2937.46    46.6  2933.5
    59.1 2929.55    68.4  2926.2    77.7 2923.86    80.9 2923.35    87.1  2922.9
    92.7 2922.99   101.2 2924.33   105.5 2924.28     114 2923.46   126.8  2923.5
   135.3 2921.11  139.692919.221   143.9 2918.25  149.292918.908   152.5 2919.53
   156.7 2921.04   164.9  2927.8   169.4 2930.24   205.4 2941.76   220.6  2947.1
   237.7 2954.33   246.2  2956.8   248.9 2957.92   254.7 2961.09   261.9 2964.35
#Mann= 3 ,-1 , 0
       0      .1       0  139.69    .045       0  149.29      .1       0
#XS Ineff= 2 , 0
          102.41 2924.58
Permanent Ineff=
       F       F
Bank Sta=139.69,149.29
XS Rating Curve= 0 ,0
Exp/Cntr(USF)=0,0
Exp/Cntr=0.3,0.1

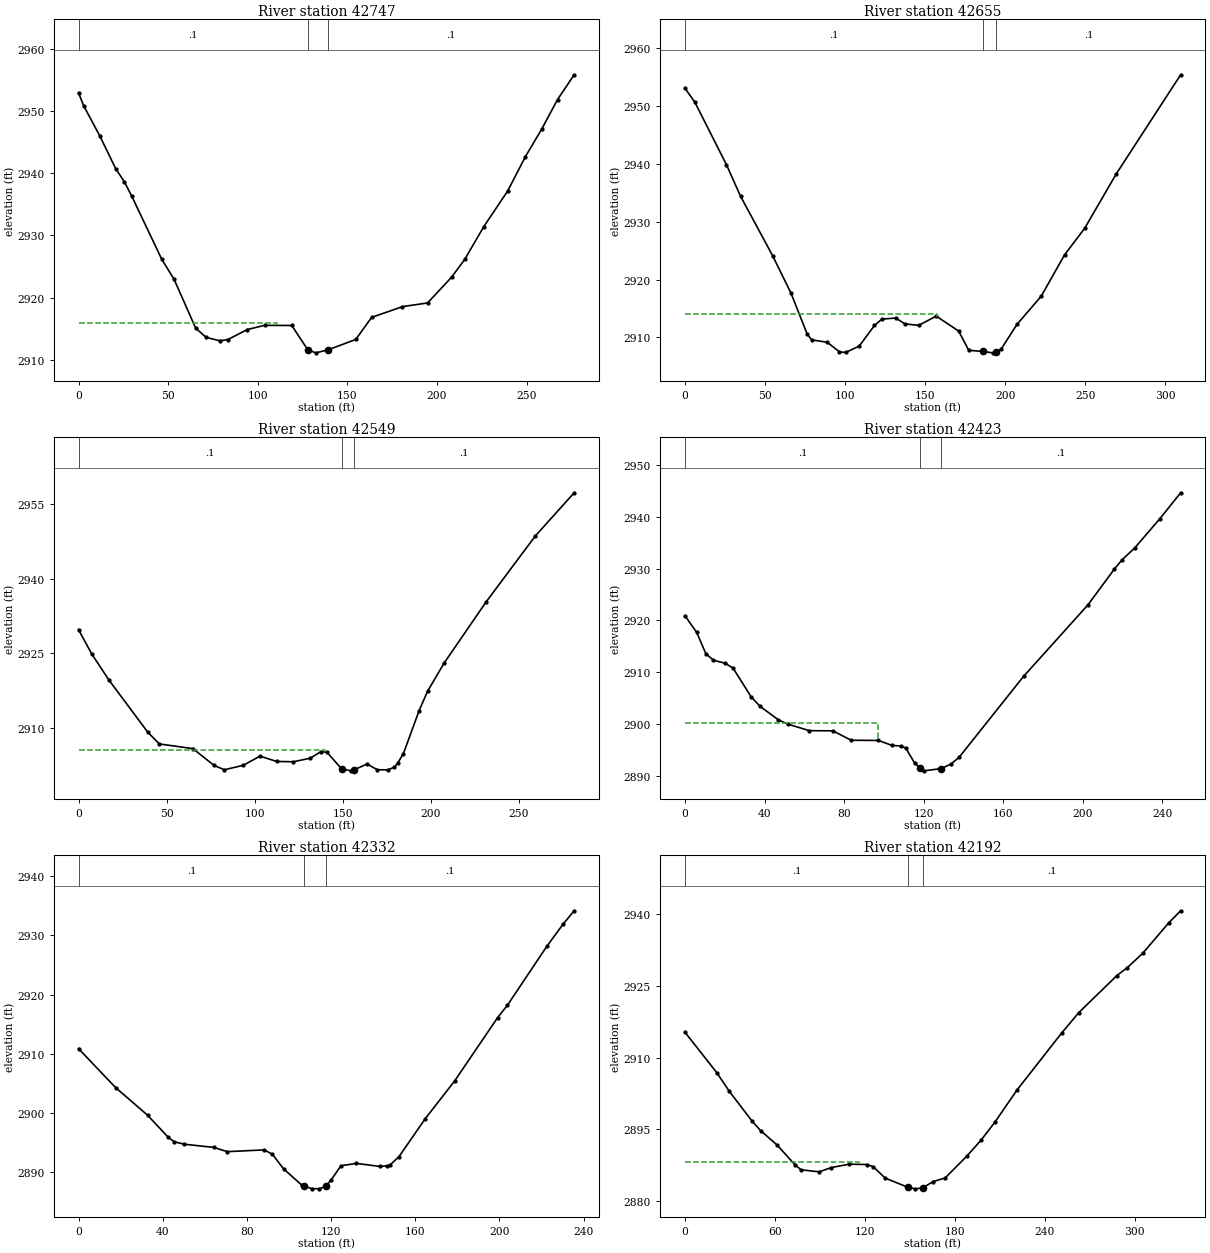
Type RM Length L Ch R = 1 ,42747   ,95.4,92.1,90.7
XS GIS Cut Line= 2
 2409303.3708505588130.9308478242409551.21829513588008.144040388
#Sta/Elev= 30
       0 2952.96     2.9 2950.85    11.8 2946.06    20.8 2940.72    25.6 2938.63
    29.7 2936.33    46.5 2926.14    53.3 2922.97    65.4 2915.08    71.3  2913.6
    78.8 2913.06    83.3 2913.25    94.2 2914.87   103.8 2915.54     119 2915.52
   127.9 2911.63   132.4 2911.12     139 2911.58   154.7 2913.27   163.6 2916.83
   180.8 2918.55   194.8 2919.15   208.2 2923.29   215.5 2926.14   226.1 2931.39
   239.5 2937.16   249.4 2942.69   258.4 2947.06   267.3 2951.86   276.6 2955.85
#Mann= 3 ,-1 , 0
       0      .1       0   127.9    .045       0     139      .1       0
#XS Ineff= 2 , 0
          110.94  2915.9
Permanent Ineff=
       F       F
Bank Sta=127.9,139
XS Rating Curve= 0 ,0
Exp/Cntr(USF)=0,0
Exp/Cntr=0.3,0.1

Type RM Length L Ch R = 1 ,42655   ,105.7,106,107.5
XS GIS Cut Line= 2
2409337.47829701588251.4438254922409583.05191188588062.715954804
#Sta/Elev= 30
       0 2953.11     6.2 2950.69    25.9 2939.89    34.7 2934.43    54.7 2924.16
    66.2 2917.67    76.3  2910.6    79.1 2909.56    88.9 2909.14    96.5 2907.49
   100.3 2907.37   108.9 2908.48   118.4 2912.05   123.1 2913.16   131.7 2913.33
   137.4 2912.33     146 2912.06     157 2913.67     171 2911.08   177.3 2907.75
  185.91 2907.56   192.3 2907.31  194.412907.541   197.4 2907.89   207.4 2912.22
   222.6 2917.12   237.2 2924.29   249.7 2928.85   269.4 2938.26   309.7 2955.45
#Mann= 3 ,-1 , 0
       0      .1       0  185.91    .045       0  194.41      .1       0
#XS Ineff= 2 , 0
          157.44 2914.04
Permanent Ineff=
       F       F
Bank Sta=185.91,194.41
XS Rating Curve= 0 ,0
Exp/Cntr(USF)=0,0
Exp/Cntr=0.3,0.1

Type RM Length L Ch R = 1 ,42549   ,125.2,126.4,125.9
XS GIS Cut Line= 2
2409403.41936026588315.1110589772409639.89765606588162.764464566
#Sta/Elev= 30
       0 2929.76     7.5 2924.85    17.3 2919.57    39.4 2909.03    45.9  2906.7
    64.9 2905.76      77 2902.36    82.8  2901.5    93.4 2902.38     103 2904.24
   112.5 2903.17     122 2903.11   131.5 2903.83   137.7 2905.17     141 2905.03
   149.3 2901.68   154.8 2901.28   156.1 2901.46   163.8 2902.65   169.6  2901.5
   175.4 2901.48   179.1 2901.97   181.1 2902.82   184.4 2904.76   193.3 2913.42
   198.1 2917.33   207.6 2923.07   231.4 2935.38   259.3 2948.66   281.3 2957.35
#Mann= 3 ,-1 , 0
       0      .1       0   149.3    .045       0   156.1      .1       0
#XS Ineff= 2 , 0
          139.68  2905.4
Permanent Ineff=
       F       F
Bank Sta=149.3,156.1
XS Rating Curve= 0 ,0
Exp/Cntr(USF)=0,0
Exp/Cntr=0.3,0.1

Type RM Length L Ch R = 1 ,42423   ,91,90.5,90.5
XS GIS Cut Line= 2
2409464.81276398588401.5165901352409683.10042164588281.003612467
#Sta/Elev= 30
       0 2920.89     5.9 2917.67    10.5 2913.56    14.3  2912.3    20.2 2911.72
    24.2 2910.77    33.3 2905.21    37.8 2903.38      47 2900.78    51.6 2899.97
    62.6 2898.69    74.4 2898.66    83.6 2896.84    97.3  2896.8     104 2895.86
   108.5 2895.72     111 2895.36   115.5 2892.45  118.452891.434   120.1 2890.93
  128.822891.361   133.8 2892.24   137.9 2893.56   170.3 2909.18   202.7    2923
     216 2929.93   219.9 2931.72   226.2 2933.99   238.9 2939.66   249.3 2944.65
#Mann= 3 ,-1 , 0
       0      .1       0  118.45    .045       0  128.82      .1       0
#XS Ineff= 2 , 0
           96.96 2900.08
Permanent Ineff=
       F       F
Bank Sta=118.45,128.82
XS Rating Curve= 0 ,0
Exp/Cntr(USF)=0,0
Exp/Cntr=0.3,0.1

Type RM Length L Ch R = 1 ,42332   ,133.6,139.5,143.7
XS GIS Cut Line= 2
2409514.83701886588481.1006319912409717.20786815588360.587654323
#Sta/Elev= 30
       0 2910.89    17.6 2904.31    32.8 2899.64    42.7 2895.88    45.5 2895.15
    50.2 2894.74    64.2  2894.2    70.7 2893.48    88.2 2893.78    92.1 2893.05
    97.4 2890.59     106 2887.85  107.222887.687   110.7 2887.24   114.5  2887.2
  117.422887.648     120 2888.69   124.7  2891.1     132  2891.5   143.3 2890.98
   146.6 2891.09   147.9  2891.2   152.2  2892.6   164.7 2899.03   178.7 2905.42
   199.1 2916.11   203.8 2918.22   222.5 2928.16   230.3 2931.94   235.5 2934.17
#Mann= 3 ,-1 , 0
       0      .1       0  107.22    .045       0  117.42      .1       0
Bank Sta=107.22,117.42
XS Rating Curve= 0 ,0
Exp/Cntr(USF)=0,0
Exp/Cntr=0.3,0.1

Type RM Length L Ch R = 1 ,42192   ,143.2,143.3,143.2
XS GIS Cut Line= 3
2409512.56318909588556.1370143132409751.31531466588547.041695243
2409830.89935652588501.565099897
#Sta/Elev= 30
       0 2915.32    21.3 2906.82    29.4 2903.02    44.6 2896.78    50.4 2894.73
    61.4 2891.72    73.4 2887.55    77.4 2886.52    89.5 2886.09    97.5 2886.98
   109.5 2887.69   121.5 2887.62   125.5 2887.18   133.5 2884.79  148.692882.852
   153.5 2882.53  158.592882.728   165.5 2884.05   173.5  2884.8   187.8 2889.32
   197.5 2892.73   206.6 2896.44   221.5 2903.24   251.2 2915.14   262.7 2919.44
     288 2927.16     295 2928.84   305.2 2931.81   322.8 2938.27   330.6 2940.75
#Mann= 3 ,-1 , 0
       0      .1       0  148.69    .045       0  158.59      .1       0
#XS Ineff= 2 , 0
          116.01 2888.12
Permanent Ineff=
       F       F
Bank Sta=148.69,158.59
XS Rating Curve= 0 ,0
Exp/Cntr(USF)=0,0
Exp/Cntr=0.3,0.1

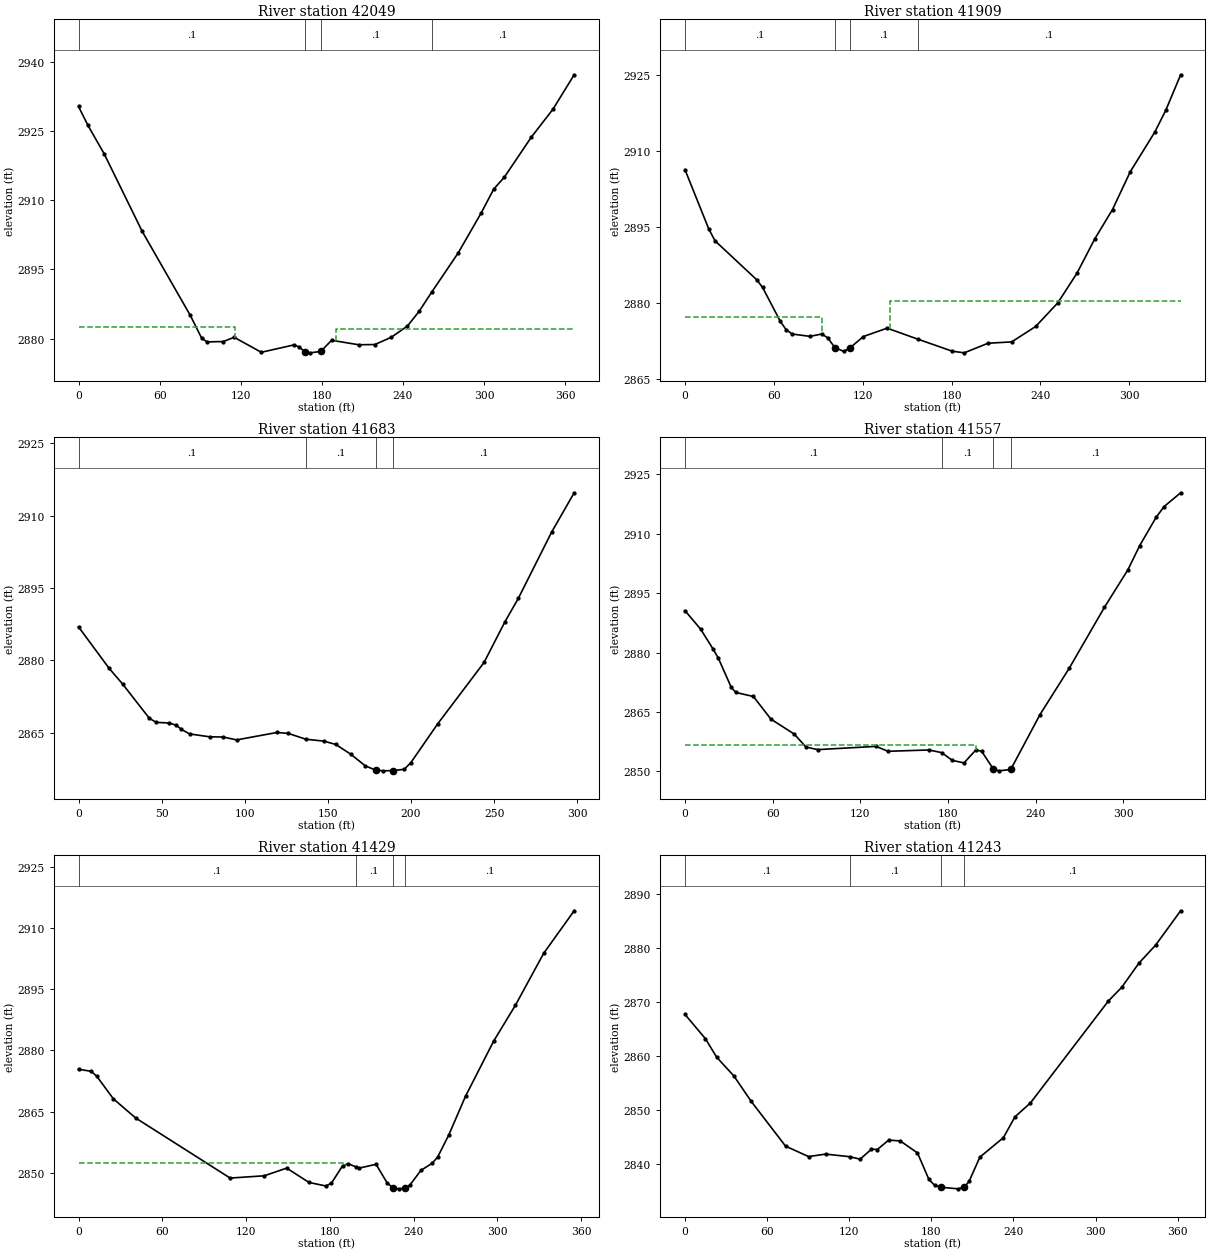
Type RM Length L Ch R = 1 ,42049   ,137.7,139.6,138.7
XS GIS Cut Line= 3
2409498.92021049588699.3882896542409749.04148489588688.019140817
2409849.08999465588628.899566867
#Sta/Elev= 30
       0 2930.31       7  2926.2    19.1 2919.98    47.1 2903.24    82.7 2885.02
    91.1 2880.09    95.1 2879.29   107.1 2879.37   115.1 2880.29   135.2 2877.04
   159.2 2878.63   163.2  2878.2   167.2 2877.19   171.2 2876.92   179.2 2877.22
   179.2 2877.23   187.2 2879.64   207.2 2878.67   219.2 2878.72   231.3 2880.29
   243.3 2882.73     252 2885.94   261.12890.019   280.8 2898.56   297.9 2907.27
   307.1 2912.41   314.9 2914.96     335  2923.7   350.9 2929.71   366.6 2937.18
#Mann= 4 ,-1 , 0
       0      .1       0   167.2    .045       0   179.2      .1       0
   261.1      .1       0
#XS Ineff= 2 , 0
          115.87 2882.57  190.64         2882.14
Permanent Ineff=
       F       F
Bank Sta=167.2,179.2
XS Rating Curve= 0 ,0
Exp/Cntr(USF)=0,0
Exp/Cntr=0.3,0.1

Type RM Length L Ch R = 1 ,41909   ,226.7,226.2,225.4
XS GIS Cut Line= 2
2409521.65850816588819.9012673222409855.91148396588801.710629183
#Sta/Elev= 30
       0 2906.23    16.1  2894.5    20.3 2892.19    48.4 2884.52    52.4    2883
    64.4 2876.28    68.4 2874.63    72.4  2873.8    84.4 2873.34    92.4 2873.81
    96.4 2873.05  101.212871.128   107.3 2870.36  111.632871.125   120.5 2873.31
   136.5 2874.96  157.112872.802   180.5 2870.41   188.6 2870.09   204.6 2871.98
   220.6 2872.25   236.8 2875.29   251.7 2879.93   264.7  2885.8   276.7 2892.56
   288.7 2898.37   300.7 2905.82   317.3 2913.67   324.7 2917.96   334.7 2924.95
#Mann= 4 ,-1 , 0
       0      .1       0  101.21    .045       0  111.63      .1       0
  157.11      .1       0
#XS Ineff= 2 , 0
           92.32 2877.22  138.21         2880.29
Permanent Ineff=
       F       F
Bank Sta=101.21,111.63
XS Rating Curve= 0 ,0
Exp/Cntr(USF)=0,0
Exp/Cntr=0.3,0.1

Type RM Length L Ch R = 1 ,41683   ,125,126.1,127
XS GIS Cut Line= 2
2409571.68276304589006.3553082422409867.28063279588967.700202198
#Sta/Elev= 30
       0 2886.96    18.4 2878.37    26.5 2875.12    42.6 2868.01    46.7 2867.17
    54.7 2867.03    58.8 2866.57    61.9 2865.71    66.8 2864.77    78.9 2864.17
      87 2864.13    95.1 2863.53   119.3 2865.07   126.1 2864.88  136.762863.672
   147.5 2863.28   154.7 2862.59   163.6  2860.6   172.5 2858.15  178.712857.269
   183.2 2857.12  189.21 2857.17   195.9 2857.44   199.9 2858.83   216.1  2866.9
   243.9 2879.58   256.4 2887.97   264.5 2892.86   284.6 2906.63   298.1 2914.75
#Mann= 4 ,-1 , 0
       0      .1       0  136.76      .1       0  178.71    .045       0
  189.21      .1       0
Bank Sta=178.71,189.21
XS Rating Curve= 0 ,0
Exp/Cntr(USF)=0,0
Exp/Cntr=0.3,0.1

Type RM Length L Ch R = 1 ,41557   ,127.9,128.1,127.8
XS GIS Cut Line= 2
2409551.21829514589115.4991370742409890.01893047 589101.85615847
#Sta/Elev= 30
       0  2890.6    10.7 2885.94    19.2 2880.92    22.8 2878.61    31.7  2871.2
    34.8 2869.94    46.8 2868.92    58.8  2863.2    74.8 2859.41    82.8 2856.15
    90.8  2855.5   130.8 2856.32   138.8 2855.08   166.9 2855.41  175.642854.739
   182.9 2852.78   190.9 2852.14   198.9 2855.37   202.9 2855.13  210.982850.584
   214.9 2850.14  222.882850.488   242.9 2864.36   262.9 2876.07   286.9 2891.41
     303 2900.91   311.1 2907.04   322.3 2914.16   327.8  2916.9   339.1 2920.38
#Mann= 4 ,-1 , 0
       0      .1       0  175.64      .1       0  210.98    .045       0
  222.88      .1       0
#XS Ineff= 2 , 0
          199.37 2856.75
Permanent Ineff=
       F       F
Bank Sta=210.98,222.88
XS Rating Curve= 0 ,0
Exp/Cntr(USF)=0,0
Exp/Cntr=0.3,0.1

Type RM Length L Ch R = 1 ,41429   ,181.7,186.2,189.2
XS GIS Cut Line= 2
2409548.94446537589242.8336040442409903.66190907 589229.19062544
#Sta/Elev= 30
       0  2875.4       9 2874.89      13 2873.71      25 2868.13      41 2863.43
   108.6 2848.72   133.1 2849.28   149.1 2851.16   165.1 2847.64   177.1 2846.79
   181.1 2847.45   189.1 2851.71   193.1 2852.24  198.472851.489   201.1 2851.16
   213.1  2852.1   221.2 2847.45  225.192846.393   229.2 2846.08  234.082846.258
   237.2 2846.94   245.2 2850.59   253.2 2852.33   257.2 2853.85   265.2 2859.29
   277.2 2868.79   297.4 2882.33   312.9 2891.07   333.2 2903.83     355 2914.24
#Mann= 4 ,-1 , 0
       0      .1       0  198.47      .1       0  225.19    .045       0
  234.08      .1       0
#XS Ineff= 2 , 0
          191.21 2852.48
Permanent Ineff=
       F       F
Bank Sta=225.19,234.08
XS Rating Curve= 0 ,0
Exp/Cntr(USF)=0,0
Exp/Cntr=0.3,0.1

Type RM Length L Ch R = 1 ,41243   ,131.4,128.7,125.3
XS GIS Cut Line= 3
2409555.76595467 589347.429773342409796.79191001589422.466155662
2409903.66190907589397.454028222
#Sta/Elev= 30
       0 2867.66    14.9 2863.18    23.2 2859.74    35.8 2856.27    48.4 2851.59
    73.5 2843.32    90.3 2841.39   102.8 2841.85  120.32 2841.37     128 2840.91
   136.3 2842.77   140.5 2842.69   148.9 2844.44   157.3 2844.28   169.9 2842.07
   178.2 2837.19   182.4 2836.09   186.8 2835.73   199.6 2835.43  204.11 2835.73
   207.6 2836.81   215.5 2841.29   232.7 2844.89   241.1 2848.73   252.4 2851.29
   309.4 2870.14   319.2 2872.68   331.7 2877.13     344 2880.49   362.2 2886.81
#Mann= 4 ,-1 , 0
       0      .1       0  120.32      .1       0   186.8    .045       0
  204.11      .1       0
Bank Sta=186.8,204.11
XS Rating Curve= 0 ,0
Exp/Cntr(USF)=0,0
Exp/Cntr=0.3,0.1

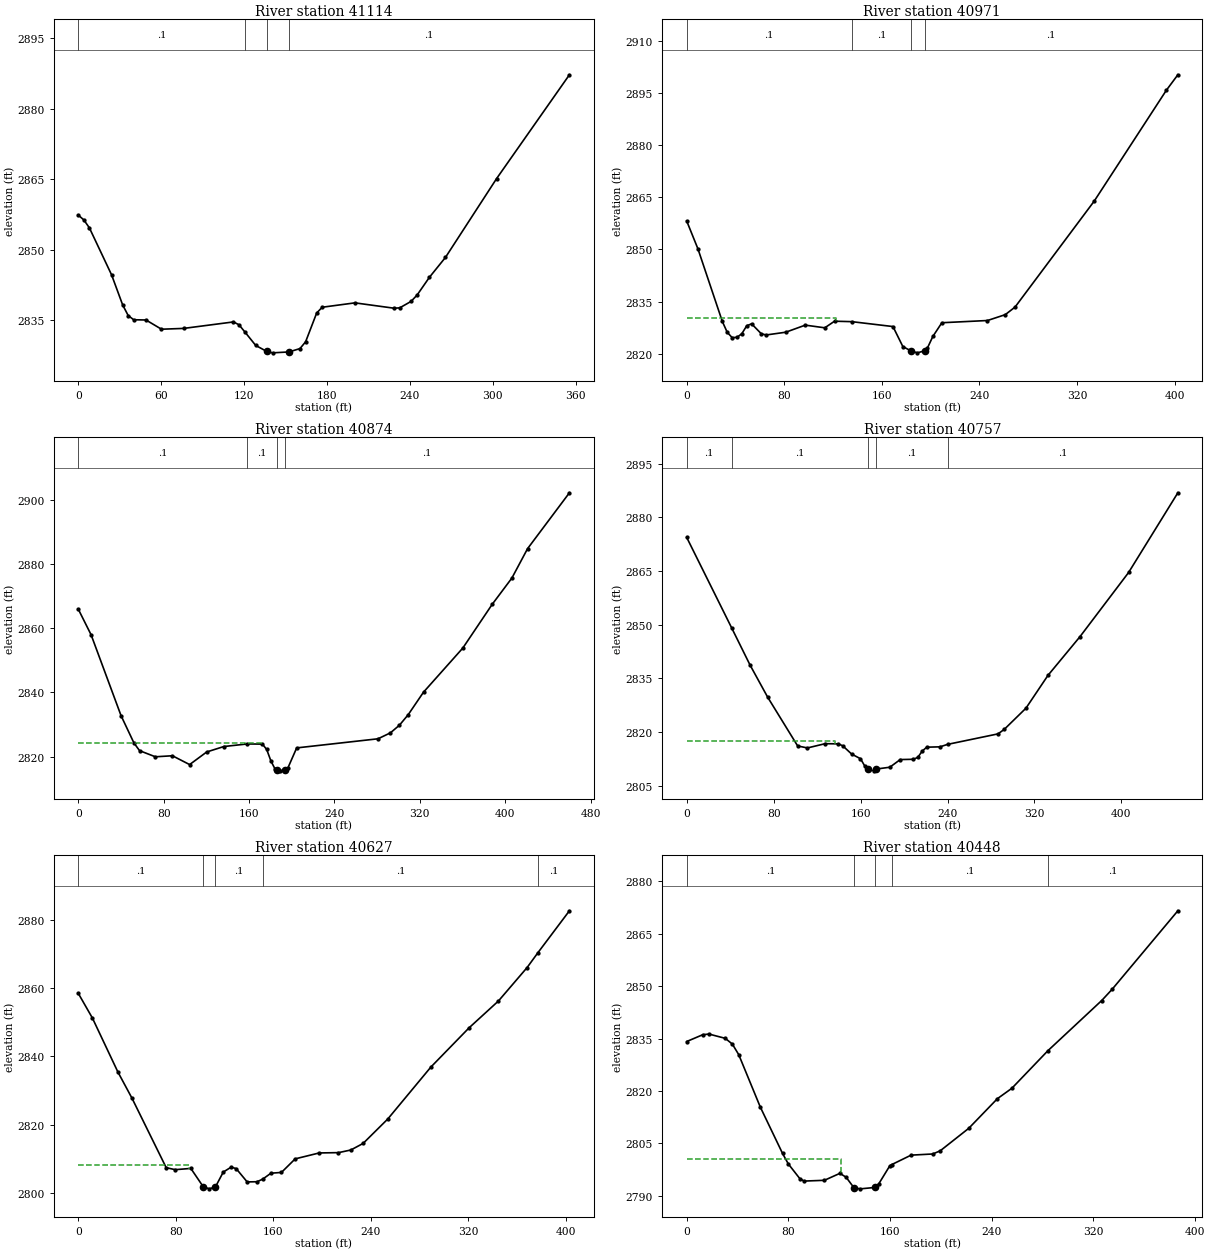
Type RM Length L Ch R = 1 ,41114   ,145,143,140.9
XS GIS Cut Line= 3
2409573.95659281589520.2408356572409812.70871838589538.431473795
2409917.30488767589488.407218914
#Sta/Elev= 30
       0 2857.38       4 2856.36       8 2854.69    24.1 2844.68    32.1  2838.3
    36.1 2836.04    40.1 2835.14      49 2835.09    60.2 2833.13    76.2  2833.3
   112.3 2834.68   116.3 2834.07  120.752832.473   128.4 2829.68  136.392828.411
   140.6 2828.11  152.39  2828.3   160.4 2829.01   164.5 2830.46   172.5 2836.57
   176.5  2837.8   200.2 2838.73   228.6 2837.59   232.6 2837.67   240.8 2839.04
   245.2  2840.4   254.1 2844.17   265.7 2848.39   302.7 2865.14   355.4  2887.2
#Mann= 4 ,-1 , 0
       0      .1       0  120.75      .1       0  136.39    .045       0
  152.39      .1       0
Bank Sta=136.39,152.39
XS Rating Curve= 0 ,0
Exp/Cntr(USF)=0,0
Exp/Cntr=0.3,0.1

Type RM Length L Ch R = 1 ,40971   ,97.6,97.3,97
XS GIS Cut Line= 3
2409580.77808211589665.7659407652409858.18531372589661.218281231
2409967.32914255589599.824877513
#Sta/Elev= 30
       0 2858.18     9.2 2850.17    29.2 2829.26    33.2 2826.15    37.2 2824.62
    41.2 2824.69    45.2 2825.75    49.2 2828.03    53.2 2828.59    61.2  2825.7
    65.2 2825.38    81.2 2826.17    97.2 2828.21   113.2 2827.44   121.2 2829.34
  135.352829.211   169.1  2827.8   177.2 2822.04  183.892820.782   189.2 2820.23
  195.022820.817   197.2  2821.5   201.8 2824.95   209.2  2828.9   246.6 2829.54
   261.2 2831.23   269.2 2833.41   334.2 2863.97   393.3 2895.87   402.7 2900.31
#Mann= 4 ,-1 , 0
       0      .1       0  135.35      .1       0  183.89    .045       0
  195.02      .1       0
#XS Ineff= 2 , 0
          122.32  2830.2
Permanent Ineff=
       F       F
Bank Sta=183.89,195.02
XS Rating Curve= 0 ,0
Exp/Cntr(USF)=0,0
Exp/Cntr=0.3,0.1

Type RM Length L Ch R = 1 ,40874   ,118.1,117,116.2
XS GIS Cut Line= 3
2409573.95659281 589772.635939832409876.37595186589749.897642156
 2410012.8057379589672.587430067
#Sta/Elev= 30
       0 2865.97      12 2857.99    40.1 2832.75    52.1 2824.29    57.4 2821.87
    72.2 2819.96    88.2 2820.28   104.3 2817.53   120.3 2821.46   136.4 2823.16
  158.362823.963   172.5 2823.91   176.5 2822.24   180.5 2818.62   184.5 2816.04
  185.692815.907   188.5 2815.58  193.492815.878   196.5 2816.59   204.6 2822.73
   280.8 2825.57   292.4 2827.42   300.8 2829.79     309 2833.05   323.4  2840.1
   360.2 2853.84   387.8  2867.5   406.2 2875.67   420.9 2884.84   460.1 2902.25
#Mann= 4 ,-1 , 0
       0      .1       0  158.36      .1       0  185.69    .045       0
  193.49      .1       0
#XS Ineff= 2 , 0
          171.36 2824.24
Permanent Ineff=
       F       F
Bank Sta=185.69,193.49
XS Rating Curve= 0 ,0
Exp/Cntr(USF)=0,0
Exp/Cntr=0.3,0.1

Type RM Length L Ch R = 1 ,40757   ,134.2,129.6,125.3
XS GIS Cut Line= 3
2409612.61169885589904.518066334 2409887.7451007589854.493811453
2410026.44871651589752.171471924
#Sta/Elev= 30
       0 2874.35   41.432849.032    58.3 2838.68    74.5 2829.71   102.1 2816.08
   111.1 2815.53   127.4 2816.72   139.6 2816.67   143.6 2816.12   151.8 2813.81
   159.9 2812.52   163.8 2810.51  166.69 2809.65   172.1 2809.13   174.4 2809.63
   186.9 2810.14   196.5 2812.28   208.7 2812.36   212.7 2812.91   216.8 2814.68
   220.9 2815.74   233.1 2815.84   240.1 2816.53   286.5 2819.46   292.3 2820.74
   312.2 2826.64   332.5 2835.83   361.9 2846.62   406.7 2864.58     452 2886.84
#Mann= 5 ,-1 , 0
       0      .1       0   41.43      .1       0  166.69    .045       0
   174.4      .1       0   240.1      .1       0
#XS Ineff= 2 , 0
          136.41  2817.4
Permanent Ineff=
       F       F
Bank Sta=166.69,174.4
XS Rating Curve= 0 ,0
Exp/Cntr(USF)=0,0
Exp/Cntr=0.3,0.1

Type RM Length L Ch R = 1 ,40627   ,177.7,179.1,176.7
XS GIS Cut Line= 2
2409744.76588859590051.5403086492410064.01158793589805.966693779
#Sta/Elev= 30
       0 2858.45    11.6 2851.21    32.5 2835.41      44 2827.78    72.1 2807.41
    79.5 2806.82    92.3 2807.19  102.392801.874   107.4 2801.21  112.492801.776
   118.9 2806.12   125.4 2807.57   129.5 2807.13   138.5 2803.24   146.6 2803.29
  151.292804.059     158 2805.79   166.6 2806.01   177.9 2809.99   197.6 2811.72
   213.4 2811.81   223.5 2812.58   233.6 2814.51   253.8 2821.65   289.2 2836.88
   320.6 2848.39   344.6 2856.22   368.1 2866.01  377.022870.385   402.8 2882.63
#Mann= 5 ,-1 , 0
       0      .1       0  102.39    .045       0  112.49      .1       0
  151.29      .1       0  377.02      .1       0
#XS Ineff= 2 , 0
           90.76  2808.2
Permanent Ineff=
       F       F
Bank Sta=102.39,112.49
XS Rating Curve= 0 ,0
Exp/Cntr(USF)=0,0
Exp/Cntr=0.3,0.1

Type RM Length L Ch R = 1 ,40448   ,153.9,148.9,145.6
XS GIS Cut Line= 2
2409869.59914282590184.5593500372410141.77656597589910.335480099
#Sta/Elev= 30
       0 2834.17    12.6 2836.11    17.5  2836.3    30.3 2835.08    35.9 2833.43
    40.9 2830.42    57.9  2815.4    75.4 2802.14    79.9 2799.16      89 2794.93
    92.3 2794.24   108.3 2794.46   120.5 2796.45   125.4 2795.34  131.692792.272
   136.7 2792.02  148.092792.419   151.2 2793.52   159.7 2798.57  161.342798.966
   176.5 2801.66   193.5 2801.99   199.4 2802.89   221.9 2809.34   244.4 2817.81
   255.8 2820.79  284.112831.523   326.5  2845.9   334.6 2849.07   386.4 2871.57
#Mann= 5 ,-1 , 0
       0      .1       0  131.69    .045       0  148.09      .1       0
  161.34      .1       0  284.11      .1       0
#XS Ineff= 2 , 0
          121.26 2800.48
Permanent Ineff=
       F       F
Bank Sta=131.69,148.09
XS Rating Curve= 0 ,0
Exp/Cntr(USF)=0,0
Exp/Cntr=0.3,0.1