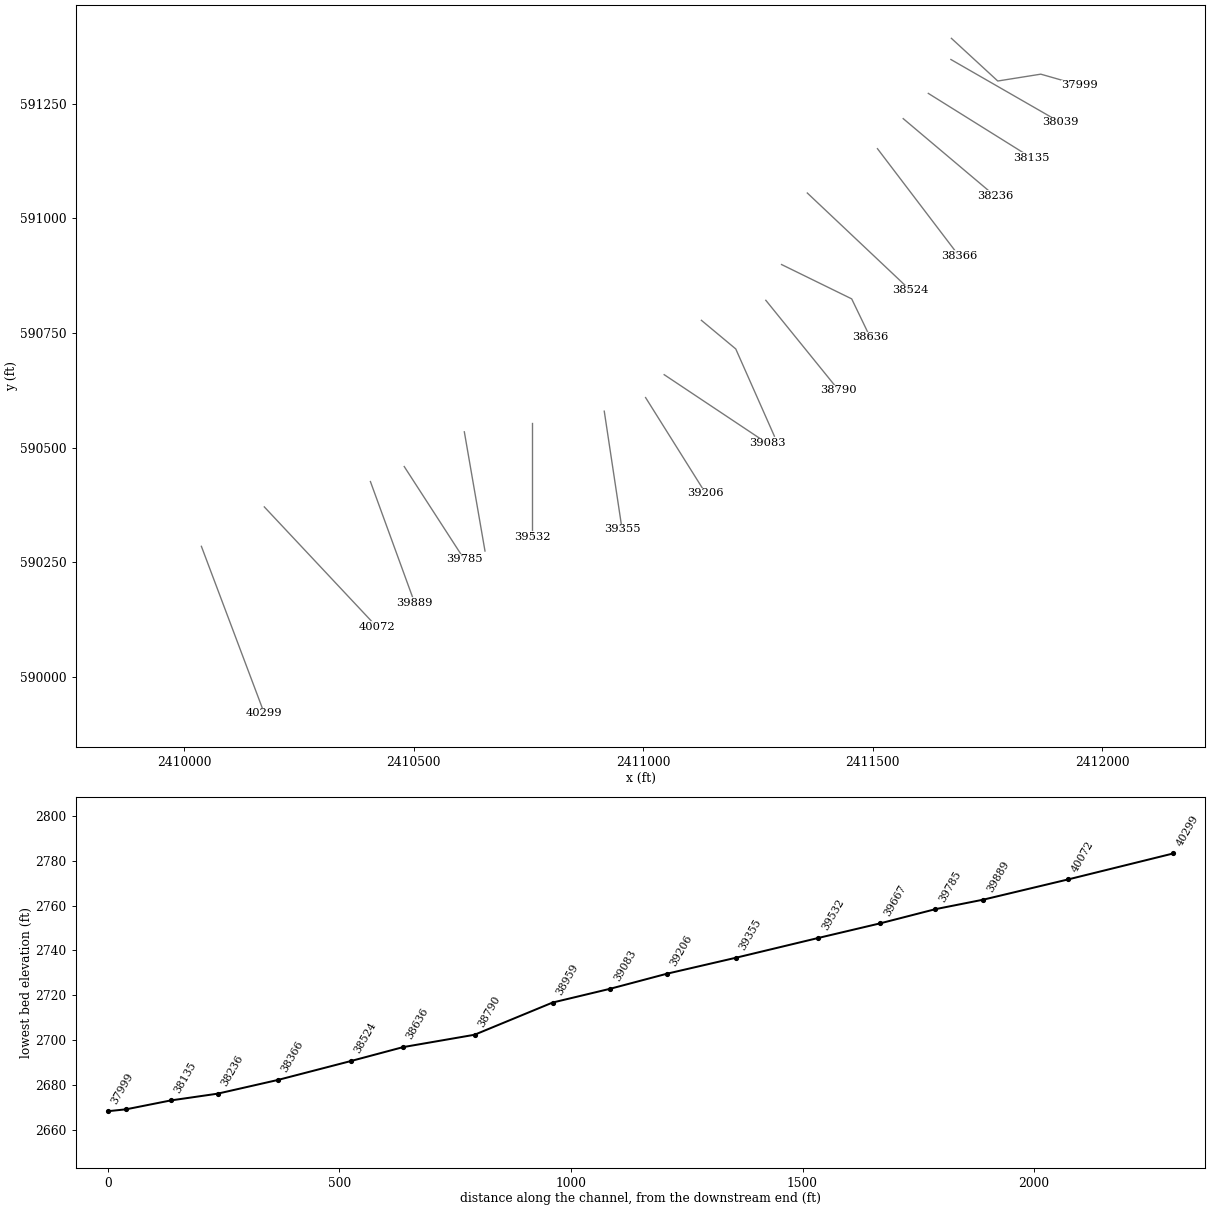
HEC-RAS study SMITHCK.prj: SMITHCK

--- SMITHCK.g01 (geometry) --- (continued)

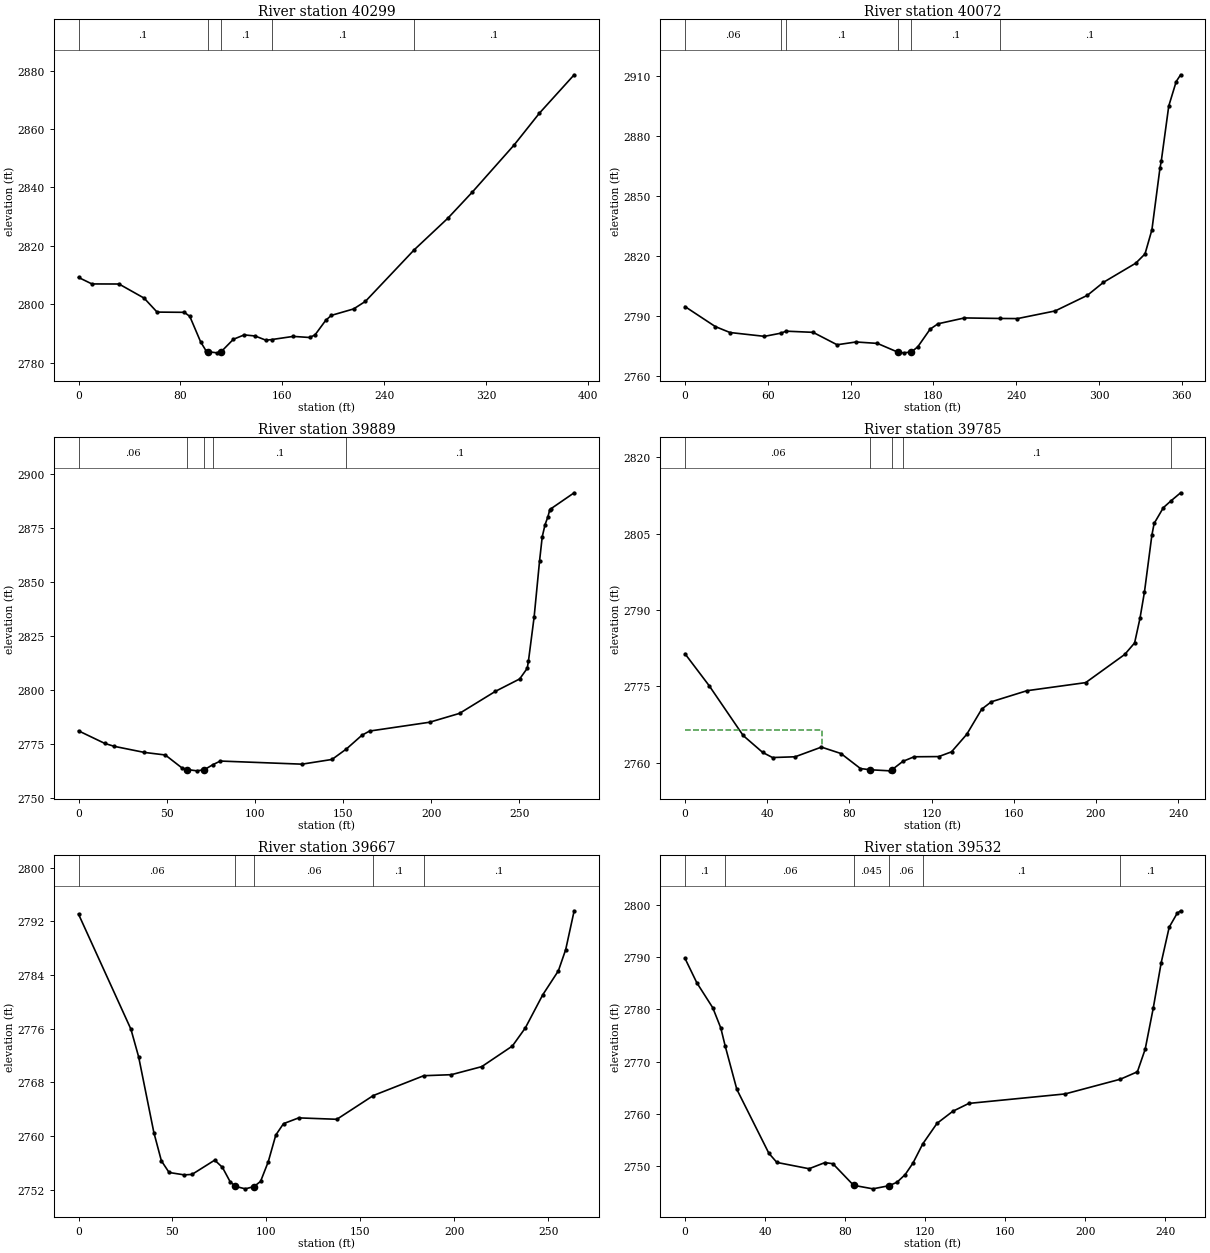
Type RM Length L Ch R = 1 ,40299   ,221.8,226.9,229.5
XS GIS Cut Line= 2
2410037.40777965590284.8352427762410174.51971462589920.567714051
#Sta/Elev= 30
       0 2809.17    10.5 2806.94    31.8 2806.91    51.5 2802.08    61.7 2797.29
    83.1 2797.21    87.4 2795.81    95.9 2787.08   100.2 2783.99   101.62783.718
   108.8 2783.33  111.912783.671   121.6 2787.97   130.1 2789.48   138.7  2789.1
   147.2 2787.65  151.582787.872   168.6 2788.96   181.4 2788.59   185.7 2789.47
   194.1 2794.46   198.5 2796.16     216 2798.37   225.3 2800.97  263.592818.627
   290.1 2829.49   309.2 2838.39     342 2854.52   361.9 2865.44   389.2  2878.6
#Mann= 5 ,-1 , 0
       0      .1       0   101.6    .045       0  111.91      .1       0
  151.58      .1       0  263.59      .1       0
Bank Sta=101.6,111.91
XS Rating Curve= 0 ,0
Exp/Cntr(USF)=0,0
Exp/Cntr=0.3,0.1

Type RM Length L Ch R = 1 ,40072   ,187.5,183.3,179.7
XS GIS Cut Line= 2
2410174.51971462590370.7860079812410420.09332949590108.840818786
#Sta/Elev= 30
       0 2794.83      22 2784.84    32.6 2781.88    57.6 2779.97   69.672781.581
   73.212782.553    92.8 2781.97   110.2 2775.77   123.9 2777.16   139.4 2776.45
  154.48    2772   158.7 2771.74  164.082772.185   168.7 2774.78   177.6 2783.55
   183.3 2786.23   202.5 2789.16  228.032788.896   240.9 2788.83   268.2 2792.65
   291.5 2800.42   303.2 2806.93   326.6 2816.48   333.3  2821.1   338.3 2833.17
   344.1 2863.78   345.1 2867.54   350.5 2894.91   355.9 2907.12   359.1 2910.48
#Mann= 6 ,-1 , 0
       0     .06       0   69.67      .1       0   73.21      .1       0
  154.48    .045       0  164.08      .1       0  228.03      .1       0
Bank Sta=154.48,164.08
XS Rating Curve= 0 ,0
Exp/Cntr(USF)=0,0
Exp/Cntr=0.3,0.1

Type RM Length L Ch R = 1 ,39889   ,101.8,103.7,106.6
XS GIS Cut Line= 2
2410405.76820195590426.0400713272410501.95120111590162.048435341
#Sta/Elev= 30
       0 2781.21    14.9 2775.38    20.2 2774.04    37.3 2771.22    49.2 2770.03
    58.5 2764.13   61.692763.293    67.1 2762.69   71.292763.198   76.162765.537
    80.4 2767.22   126.7 2765.78   143.7 2767.96  151.872772.807   160.7 2779.18
     165  2781.1     199 2785.18     216 2789.28   236.4 2799.51   250.1 2805.22
   254.4 2810.15   255.1 2813.63   258.3 2833.88   261.4    2860   262.9 2871.04
   264.5 2876.65   266.1 2880.25   267.1  2883.3   267.6 2883.87     281 2891.39
#Mann= 5 ,-1 , 0
       0     .06       0   61.69    .045       0   71.29     .06       0
   76.16      .1       0  151.87      .1       0
Bank Sta=61.69,71.29
XS Rating Curve= 0 ,0
Exp/Cntr(USF)=0,0
Exp/Cntr=0.3,0.1

Type RM Length L Ch R = 1 ,39785   ,123,118.8,115.1
XS GIS Cut Line= 2
2410479.44028641590458.7832199762410610.41288101590256.184987708
#Sta/Elev= 30
       0 2781.42    11.8 2775.13    28.3 2765.37    37.8 2762.05    42.6 2761.04
    53.6 2761.19    66.4 2763.09    75.9 2761.83    85.4 2758.88   90.22 2758.64
    99.7 2758.43   100.82758.666  106.042760.291   111.5 2761.19   123.5 2761.23
   129.7 2762.16   137.1 2765.59   144.4 2770.54   149.1 2771.99   166.4 2774.16
     195 2775.75     214 2781.28   218.8 2783.54   221.4 2788.34   223.6 2793.55
   227.2 2804.68   228.3    2807   232.8  2810.1  236.692811.499   241.2 2813.02
#Mann= 5 ,-1 , 0
       0     .06       0   90.22    .045       0   100.8     .06       0
  106.04      .1       0  236.69      .1       0
#XS Ineff= 2 , 0
           66.66 2766.46
Permanent Ineff=
       F       F
Bank Sta=90.22,100.8
XS Rating Curve= 0 ,0
Exp/Cntr(USF)=0,0
Exp/Cntr=0.3,0.1

Type RM Length L Ch R = 1 ,39667   ,136,134.3,131.8
XS GIS Cut Line= 2
2410610.41288101590534.5017512282410655.43471041590274.603008823
#Sta/Elev= 30
       0 2793.08    27.9 2775.92      32  2771.8    40.1 2760.52    44.1  2756.3
    48.2 2754.56    56.3  2754.2    60.4 2754.27    72.5  2756.4    76.6 2755.32
    80.7 2753.18   83.552752.482    88.8 2752.12   93.392752.458    96.9 2753.23
     101 2756.17     105 2760.14   109.1 2761.84   117.2  2762.7   137.5 2762.49
   156.92766.031  183.742768.988   198.4 2769.14   214.6 2770.34   230.9 2773.41
   237.8 2776.11   247.1 2781.06   255.4 2784.63   259.3  2787.8   263.8 2793.58
#Mann= 5 ,-1 , 0
       0     .06       0   83.55    .045       0   93.39     .06       0
   156.9      .1       0  183.74      .1       0
Bank Sta=83.55,93.39
XS Rating Curve= 0 ,0
Exp/Cntr(USF)=0,0
Exp/Cntr=0.3,0.1

Type RM Length L Ch R = 1 ,39532   ,175.4,177.1,179.4
XS GIS Cut Line= 2
2410757.75704993590552.9197723432410757.75704993590305.299710682
#Sta/Elev= 30
       0 2789.81     5.9 2785.13    13.9 2780.31    17.9 2776.43   20.092772.975
    25.9 2764.66    41.9 2752.39    45.9 2750.63      62 2749.42    69.9  2750.6
    73.9 2750.38   84.232746.237    93.9 2745.56  101.912746.162   105.9 2746.82
     110  2748.3   113.9 2750.51  118.792754.197   125.9 2758.13   133.8 2760.45
   141.8 2761.96   189.9 2763.78  217.492766.606     226 2768.03   229.9 2772.38
   233.9 2780.21   237.9 2788.99   241.9  2795.8   245.9 2798.48   247.6 2798.94
#Mann= 6 ,-1 , 0
       0      .1       0   20.09     .06       0   84.23    .045       0
  101.91     .06       0  118.79      .1       0  217.49      .1       0
Bank Sta=84.23,101.91
XS Rating Curve= 0 ,0
Exp/Cntr(USF)=0,0
Exp/Cntr=0.3,0.1

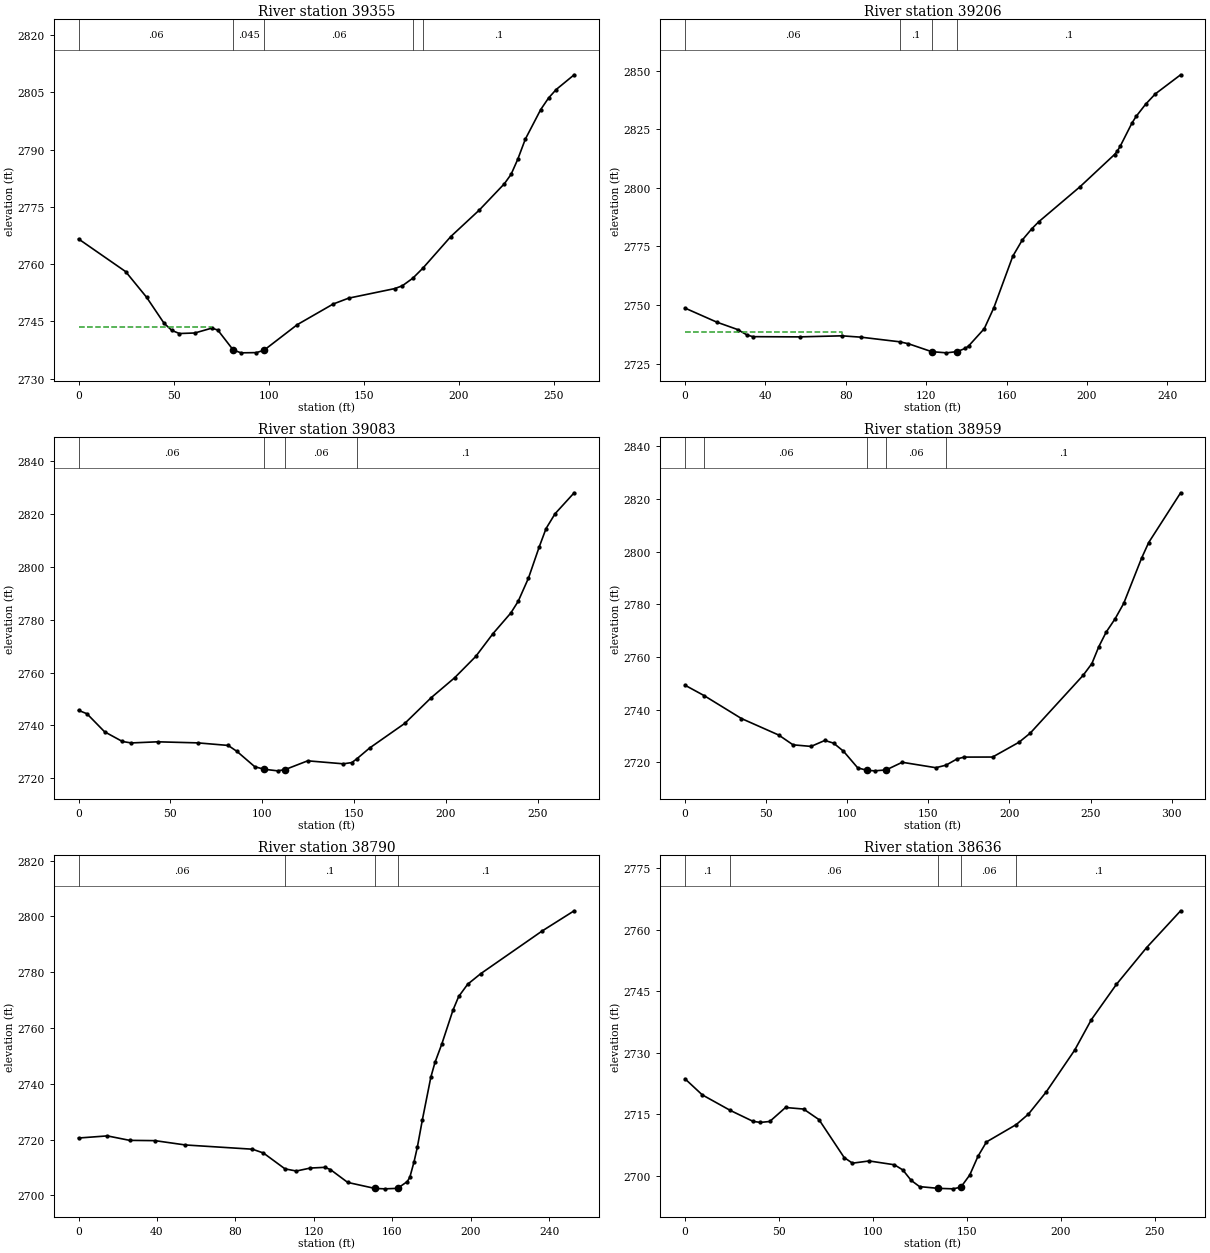
Type RM Length L Ch R = 1 ,39355   ,143.8,149.3,152.5
XS GIS Cut Line= 2
2410915.33345281590579.5235806212410954.21594183590321.671285007
#Sta/Elev= 30
       0  2766.6    24.8 2758.04    35.8 2751.33      45 2744.52    49.1 2742.63
    53.1 2741.82    61.2 2741.96    70.2 2743.24    73.3 2742.72   81.392737.516
    85.5 2736.76    93.6 2736.82   97.592737.438   115.1 2744.14     134 2749.55
   142.1 2751.08   166.4 2753.59   170.4 2754.33  175.922756.319  181.212758.948
   195.9 2767.23   210.9 2774.17   224.1 2781.07   227.6 2783.51   231.1 2787.44
   235.1 2792.74   243.2 2800.49   247.3  2803.5   251.3 2805.72   260.8  2809.6
#Mann= 5 ,-1 , 0
       0     .06       0   81.39    .045       0   97.59     .06       0
  175.92      .1       0  181.21      .1       0
#XS Ineff= 2 , 0
           69.67 2743.44
Permanent Ineff=
       F       F
Bank Sta=81.39,97.59
XS Rating Curve= 0 ,0
Exp/Cntr(USF)=0,0
Exp/Cntr=0.3,0.1

Type RM Length L Ch R = 1 ,39206   ,117,122.7,126.9
XS GIS Cut Line= 2
2411005.39208331590609.2075080962411136.39462135 590400.22726885
#Sta/Elev= 30
       0 2748.71    15.8 2742.72    26.2 2739.55    30.9 2737.21    33.8 2736.51
      57 2736.42    78.1 2736.87    87.6 2736.29  106.872734.317   111.2 2733.48
  122.722730.117   130.1 2729.61  135.43 2730.15   139.5 2731.53   141.2 2732.62
   148.9 2739.91   153.7 2748.92   163.1 2770.85   167.8 2777.73   172.5  2782.5
     176 2785.54   196.6 2800.53   213.7 2814.23     215 2815.53   216.6 2817.87
   222.4 2827.68   224.5 2830.54   229.2 2835.71     234  2840.1   246.6 2848.26
#Mann= 4 ,-1 , 0
       0     .06       0  106.87      .1       0  122.72    .045       0
  135.43      .1       0
#XS Ineff= 2 , 0
           78.07 2738.48
Permanent Ineff=
       F       F
Bank Sta=122.72,135.43
XS Rating Curve= 0 ,0
Exp/Cntr(USF)=0,0
Exp/Cntr=0.3,0.1

Type RM Length L Ch R = 1 ,39083   ,131.3,124.4,119.1
XS GIS Cut Line= 2
2411045.94048794590659.1132368722411270.51626743590509.396050546
#Sta/Elev= 30
       0 2745.72     4.6 2744.43    14.2 2737.62    23.9 2733.96    28.7 2733.41
    43.1 2733.84    65.1 2733.43    81.5 2732.47    86.3 2730.21      96 2724.42
   101.2 2723.47   108.4 2722.88   112.5 2723.36   124.8 2726.66   144.2 2725.53
   148.8    2726  151.422727.338   158.5 2731.49   177.7 2740.81   192.1 2750.53
   204.8 2758.01   216.3 2766.06   225.7 2774.68   235.4 2782.46   239.4 2786.85
     245 2795.61   250.9 2807.47   254.6 2814.35   259.5 2819.93   269.9 2827.84
#Mann= 4 ,-1 , 0
       0     .06       0   101.2    .045       0   112.5     .06       0
  151.42      .1       0
Bank Sta=101.2,112.5
XS Rating Curve= 0 ,0
Exp/Cntr(USF)=0,0
Exp/Cntr=0.3,0.1

Type RM Length L Ch R = 1 ,38959   ,165.2,168.5,170.3
XS GIS Cut Line= 3
 2411127.0372972590777.6393427132411201.89589037590715.257181744
2411286.11180768590524.991590788
#Sta/Elev= 30
       0 2749.25   11.692745.336    34.8 2736.59    57.8 2730.31    66.6  2726.6
    77.7    2726    86.2 2728.26    91.6 2727.24    97.7 2724.17   106.5 2717.83
  112.312716.912   116.9 2716.72  124.012717.073   133.9 2719.97   154.6 2717.91
  160.91 2718.88   167.7 2721.25   172.1 2721.94   189.6 2721.96   205.9 2727.59
   212.8 2731.04   245.4    2753   250.8 2757.47   255.1 2763.93   259.6 2769.41
   265.1 2774.46   270.4 2780.31   281.4 2797.45   285.8 2803.43   305.5 2822.34
#Mann= 5 ,-1 , 0
       0      .1       0   11.69     .06       0  112.31    .045       0
  124.01     .06       0  160.91      .1       0
Bank Sta=112.31,124.01
XS Rating Curve= 0 ,0
Exp/Cntr(USF)=0,0
Exp/Cntr=0.3,0.1

Type RM Length L Ch R = 1 ,38790   ,148.4,154.1,158
XS GIS Cut Line= 2
2411267.39715938590821.3068553912411426.47166986590624.803048339
#Sta/Elev= 30
       0 2720.56    14.7 2721.32    26.1 2719.72      39 2719.62    54.5 2718.07
    88.7 2716.55    94.3 2715.19  105.332709.492   111.1 2708.73   118.2 2709.79
   125.6 2710.05   128.5 2709.24   137.3 2704.64  151.21 2702.48   156.3 2702.34
  162.712702.514   167.7 2704.95     169 2706.53   171.1 2711.95   172.8 2717.22
   175.4 2727.16   179.7 2742.38   181.8 2747.64   185.3 2754.28     191 2766.42
   193.9  2771.3   198.5 2775.71   205.2 2779.51   236.5  2794.8   252.8 2802.03
#Mann= 4 ,-1 , 0
       0     .06       0  105.33      .1       0  151.21    .045       0
  162.71      .1       0
Bank Sta=151.21,162.71
XS Rating Curve= 0 ,0
Exp/Cntr(USF)=0,0
Exp/Cntr=0.3,0.1

Type RM Length L Ch R = 1 ,38636   ,116.5,112.4,109.6
XS GIS Cut Line= 3
2411301.70734792590899.2845566022411454.54364229 590824.42596344
2411495.09204692590740.210046131
#Sta/Elev= 30
       0 2723.67     9.2 2719.75   24.142715.951    36.2 2713.29    40.1 2713.03
    45.1 2713.26    53.5 2716.67    63.1 2716.29    71.3 2713.71    84.7 2704.46
    89.1 2703.09      98 2703.63   111.4  2702.7   115.9 2701.44   120.3 2698.91
   124.8 2697.37  134.78 2696.95   142.6 2696.83  146.772697.236   151.5  2700.2
   155.9 2704.78   160.4 2708.27  176.272712.514   182.7 2715.04   192.1 2720.41
   207.3 2730.64   216.2 2738.09   229.5 2746.68   245.6 2755.67   263.7 2764.65
#Mann= 5 ,-1 , 0
       0      .1       0   24.14     .06       0  134.78    .045       0
  146.77     .06       0  176.27      .1       0
Bank Sta=134.78,146.77
XS Rating Curve= 0 ,0
Exp/Cntr(USF)=0,0
Exp/Cntr=0.3,0.1

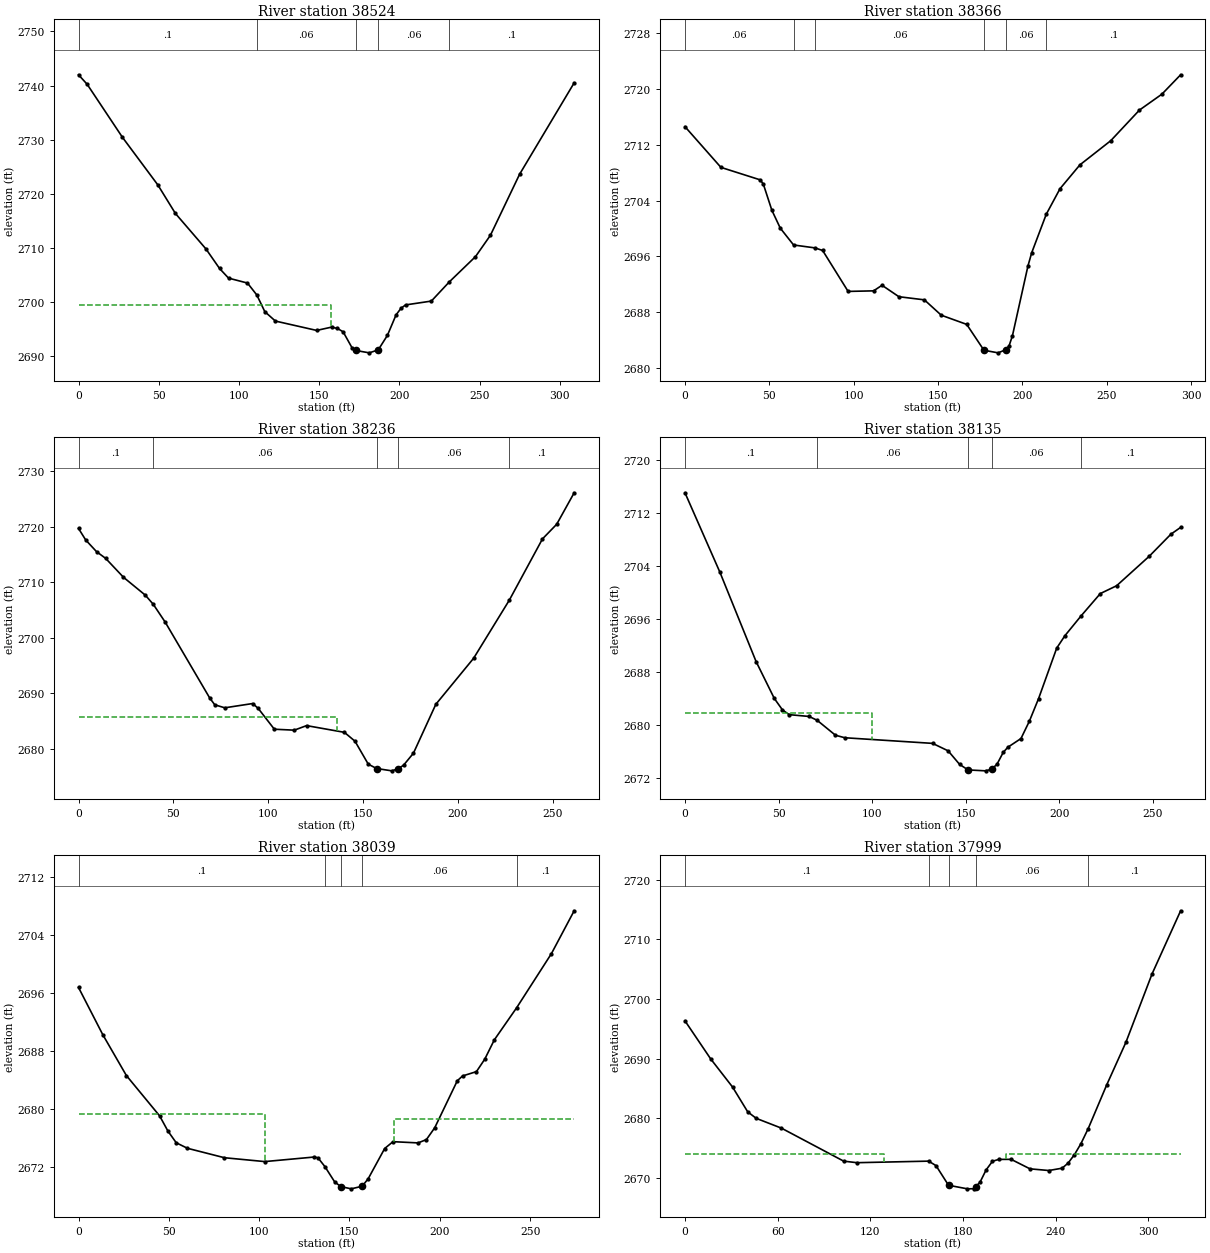
Type RM Length L Ch R = 1 ,38524   ,160.2,157.8,156.2
XS GIS Cut Line= 2
2411357.85129279591055.2399590252411582.42707228 590843.14061173
#Sta/Elev= 30
       0 2741.99     5.4 2740.23    27.4 2730.43    49.4 2721.66    60.4 2716.37
    79.4 2709.83    87.9 2706.21    93.5 2704.43   105.3 2703.52  111.122701.317
   116.1 2698.24   122.7  2696.5   148.4 2694.77   157.7 2695.38   161.4 2695.13
   164.9 2694.52   170.4  2691.6   172.7 2691.07   181.2 2690.63   186.8 2691.18
   192.5 2693.85   197.9 2697.64     201 2698.87   203.8 2699.48   219.9 2700.19
  231.14 2703.75   247.4  2708.4   256.7 2712.34   274.9 2723.62   308.9  2740.5
#Mann= 5 ,-1 , 0
       0      .1       0  111.12     .06       0   172.7    .045       0
   186.8     .06       0  231.14      .1       0
#XS Ineff= 2 , 0
          157.17 2699.39
Permanent Ineff=
       F       F
Bank Sta=172.7,186.8
XS Rating Curve= 0 ,0
Exp/Cntr(USF)=0,0
Exp/Cntr=0.3,0.1

Type RM Length L Ch R = 1 ,38366   ,127.4,130.4,133
XS GIS Cut Line= 2
2411510.68758716591151.9323085272411688.47674593590917.999204893
#Sta/Elev= 30
       0 2714.61    21.3 2708.77    44.7 2706.97    46.5 2706.33    51.5 2702.62
    56.5 2700.05   64.382697.639   77.112697.219    81.6 2696.85    96.7 2690.98
   111.8 2691.06   116.8 2691.86   126.8 2690.22   141.9 2689.77   151.9 2687.57
     167 2686.25  177.22 2682.54   185.6 2682.17  190.122682.614   192.1 2683.17
   194.1 2684.62   203.3 2694.63   205.5 2696.51  214.162702.051   222.3 2705.71
   234.1 2709.13   252.4  2712.6   269.4 2716.99   282.7 2719.27   293.8 2722.05
#Mann= 6 ,-1 , 0
       0     .06       0   64.38      .1       0   77.11     .06       0
  177.22    .045       0  190.12     .06       0  214.16      .1       0
Bank Sta=177.22,190.12
XS Rating Curve= 0 ,0
Exp/Cntr(USF)=0,0
Exp/Cntr=0.3,0.1

Type RM Length L Ch R = 1 ,38236   ,98.9,101.2,102.3
XS GIS Cut Line= 2
2411566.83153204591217.4335775442411766.45444714591049.001742928
#Sta/Elev= 30
       0 2719.71     3.8 2717.63     9.5 2715.53    14.3 2714.32    23.7 2710.91
    35.2 2707.69    39.42706.042    45.7 2702.82    69.1 2689.18    71.8 2687.93
    77.1 2687.39    91.8 2688.16    94.7 2687.28   103.2 2683.53   113.7 2683.36
   120.2 2684.18   140.1 2682.97   145.7 2681.37   152.7 2677.23  157.09 2676.45
   165.1 2676.03  168.492676.408   171.3 2677.05   176.5 2679.21   188.3 2688.02
   208.2 2696.31     2272706.776   244.5 2717.83     252 2720.47   261.2 2726.14
#Mann= 5 ,-1 , 0
       0      .1       0    39.4     .06       0  157.09    .045       0
  168.49     .06       0     227      .1       0
#XS Ineff= 2 , 0
           136.3 2685.72
Permanent Ineff=
       F       F
Bank Sta=157.09,168.49
XS Rating Curve= 0 ,0
Exp/Cntr(USF)=0,0
Exp/Cntr=0.3,0.1

Type RM Length L Ch R = 1 ,38135   ,95,96,96.1
XS GIS Cut Line= 2
 2411621.5276685591272.4710442832411846.10344799591132.111182102
#Sta/Elev= 30
       0 2715.03    18.7    2703      38 2689.52    47.7 2683.96    52.1 2682.21
    55.7  2681.5    66.3 2681.23    70.62680.649    80.4 2678.39    85.4 2678.01
   132.3 2677.16   140.6 2676.03   146.7 2673.99  151.222673.149   160.6 2673.01
  163.822673.253   166.7 2674.01     170 2675.79   172.5 2676.58   179.5 2677.89
     184 2680.52   188.9 2683.92   198.6 2691.56     203 2693.44   211.6 2696.42
   221.9  2699.8   230.6 2700.98     248 2705.43   259.6 2708.77   264.8  2709.8
#Mann= 5 ,-1 , 0
       0      .1       0    70.6     .06       0  151.22    .045       0
  163.82     .06       0   211.6      .1       0
#XS Ineff= 2 , 0
          100.11  2681.7
Permanent Ineff=
       F       F
Bank Sta=151.22,163.82
XS Rating Curve= 0 ,0
Exp/Cntr(USF)=0,0
Exp/Cntr=0.3,0.1

Type RM Length L Ch R = 1 ,38039   ,28.7,39.9,46.2
XS GIS Cut Line= 2
2411670.78410631 591346.347289922411908.63132855591209.541734368
#Sta/Elev= 30
       0 2696.77    13.4 2690.29    26.5 2684.65    44.9  2679.1    49.5 2677.01
    54.1  2675.4    60.3 2674.64    80.8 2673.34   103.1 2672.81   130.6 2673.44
   132.6 2673.32  136.412672.118   141.8 2670.02  145.192669.371     151 2669.06
  156.992669.418   160.3 2670.42   169.5 2674.61   174.1 2675.55     188 2675.38
   192.6 2675.84   197.2 2677.46   209.7 2683.93   212.6 2684.59   220.3 2685.19
   224.9  2686.9   230.2 2689.56  242.572693.982   261.8 2701.42   274.4 2707.32
#Mann= 5 ,-1 , 0
       0      .1       0  136.41     .06       0  145.19    .045       0
  156.99     .06       0  242.57      .1       0
#XS Ineff= 2 , 0
          103.16  2679.4  174.86          2678.7
Permanent Ineff=
       F       F
Bank Sta=145.19,156.99
XS Rating Curve= 0 ,0
Exp/Cntr(USF)=0,0
Exp/Cntr=0.5,0.3

Type RM Length L Ch R = 1 ,37999   ,57.7,56.8,58.3
XS GIS Cut Line= 4
2411671.82577296591392.5278454722411772.86743967591299.472289935
2411866.61743963591314.4028454722411951.68688412591290.097289935
#Sta/Elev= 30
       0 2696.33    16.6 2689.97    30.8 2685.24    40.6 2681.09    46.1    2680
    62.4 2678.36   102.7 2672.83   111.3 2672.57  157.732672.831   162.5 2672.07
  170.582668.788   182.8 2668.19   186.8 2668.21  188.182668.575   190.9 2669.27
   194.9 2671.36     199  2672.8     203 2673.12   211.1 2673.13   223.3 2671.54
   235.5 2671.26   244.1 2671.65     248 2672.51   252.1 2673.93   256.3 2675.77
     2612678.292   272.9 2685.57   285.4 2692.75   302.3 2704.19   320.8 2714.77
#Mann= 5 ,-1 , 0
       0      .1       0  157.73     .06       0  170.58    .045       0
  188.18     .06       0     261      .1       0
#XS Ineff= 2 , 0
          128.75    2674  208.08            2674
Permanent Ineff=
       F       F
Bank Sta=170.58,188.18
XS Rating Curve= 0 ,0
Exp/Cntr(USF)=0,0
Exp/Cntr=0.5,0.3