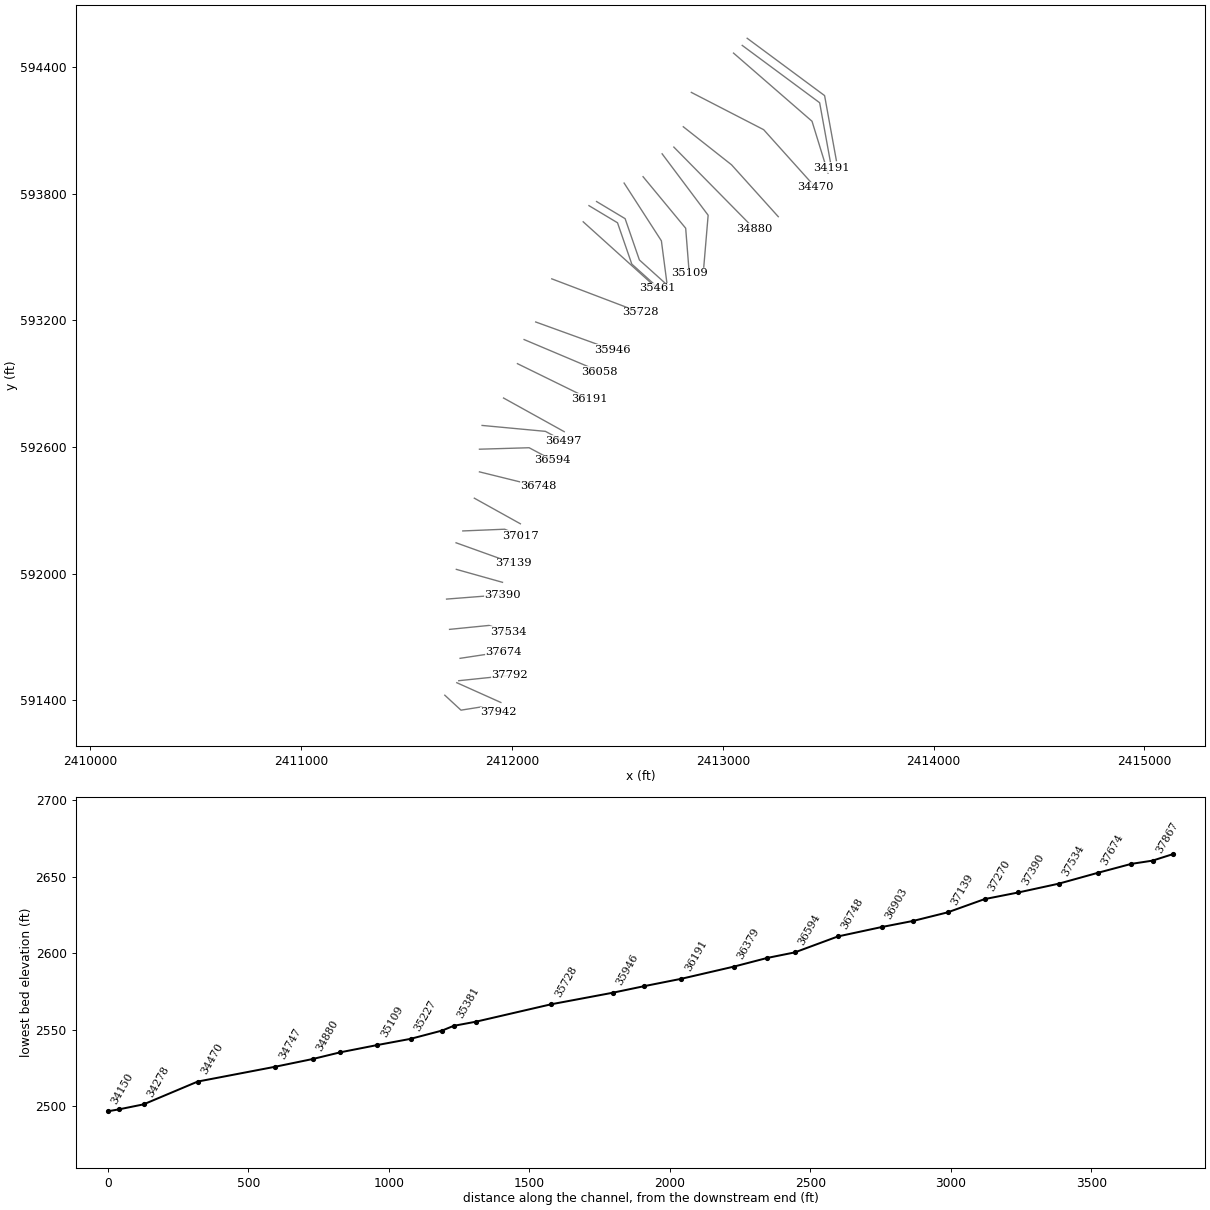
HEC-RAS study SMITHCK.prj: SMITHCK

--- SMITHCK.g01 (geometry) --- (continued)

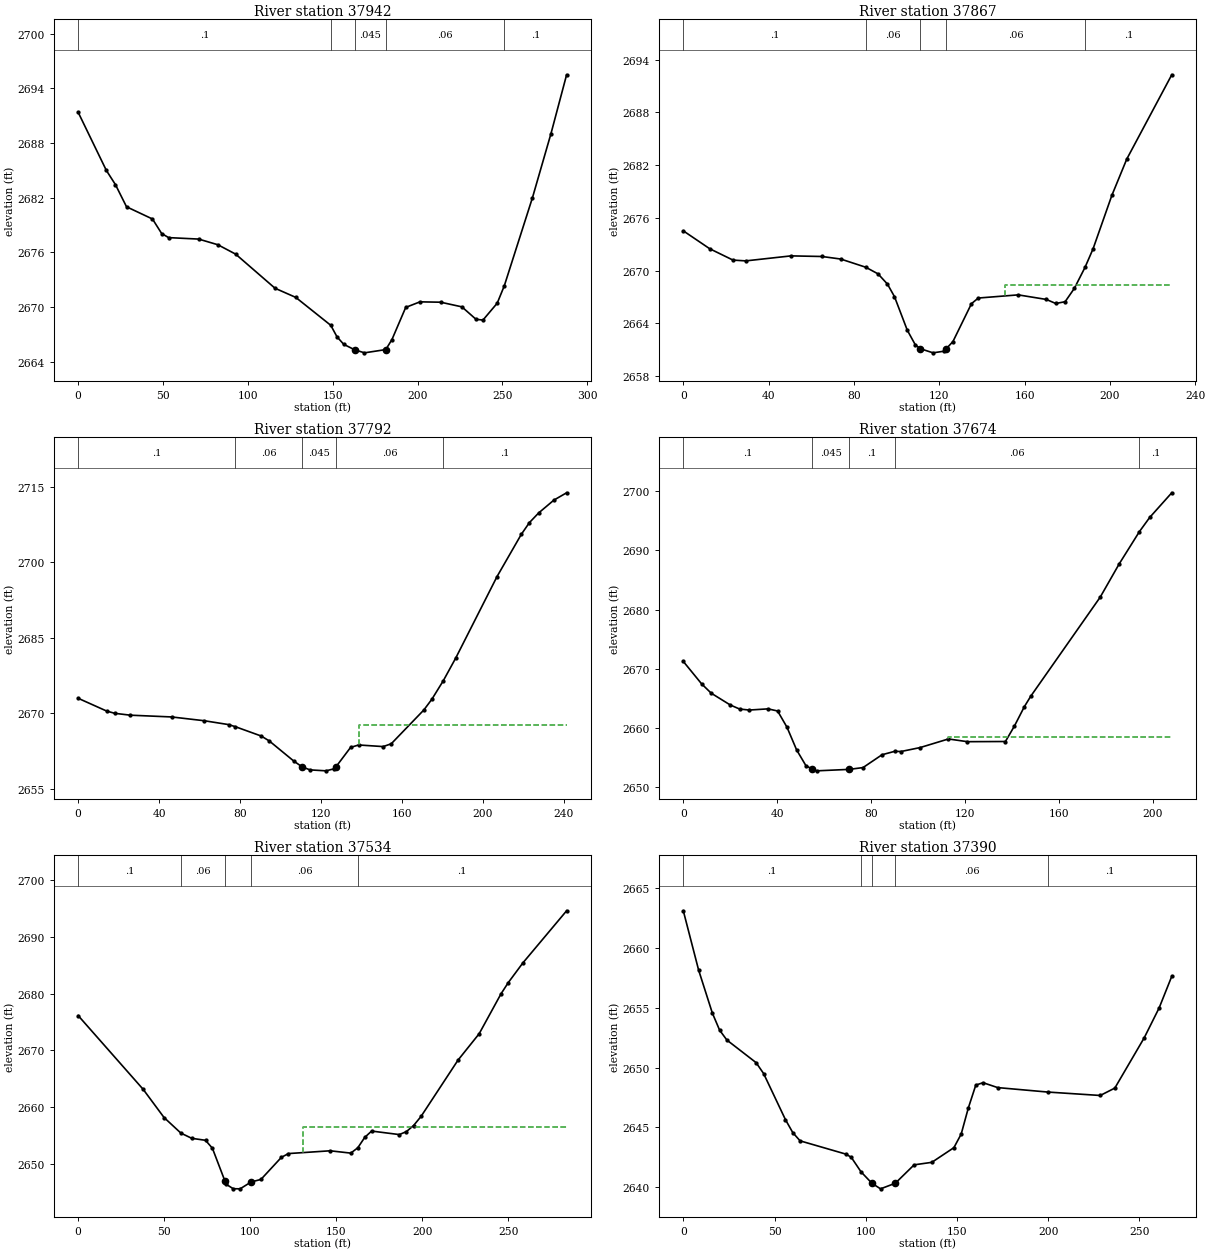
Type RM Length L Ch R = 1 ,37942   ,82.3,74.5,66.7
XS GIS Cut Line= 4
2411681.54799519591423.0834010262411758.28410634591352.250067713
2411852.03410629 591367.180623252411937.10355079591342.875067713
#Sta/Elev= 30
       0 2691.37    16.6    2685      22 2683.43    28.5 2681.01    43.8 2679.67
    49.2 2678.08    53.3 2677.63      71 2677.47    82.3 2676.85    92.8 2675.82
     116 2672.08   128.2 2671.08  148.852668.016   152.5 2666.76   156.5 2665.93
  162.922665.335   168.7    2665  181.252665.356   184.9 2666.46     193 2669.98
   201.4 2670.59   213.6 2670.55   226.1 2670.04   234.4 2668.68   238.5 2668.59
   246.9 2670.44  251.072672.338   267.7 2682.02   278.6 2689.04   287.8 2695.48
#Mann= 5 ,-1 , 0
       0      .1       0  148.85     .06       0  162.92    .045       0
  181.25     .06       0  251.07      .1       0
#XS Ineff= 2 , 0
                          209.36         2669.83
Permanent Ineff=
       F       F
Bank Sta=162.92,181.25
XS Rating Curve= 0 ,0
Exp/Cntr(USF)=0,0
Exp/Cntr=0.5,0.3

Type RM Length L Ch R = 1 ,37867   ,66.6,75.3,80.1
XS GIS Cut Line= 2
2411738.37658275591482.3460543262411947.35682199591388.772812872
#Sta/Elev= 30
       0 2674.52    12.4 2672.48    23.3 2671.19    29.3  2671.1    50.5 2671.67
      65  2671.6    73.8 2671.31   85.542670.377    91.3 2669.62    95.7 2668.46
      99 2667.03     105 2663.21   108.8 2661.53  111.092661.102   117.1 2660.63
     122 2660.81  123.192661.078   126.4 2661.91   135.1 2666.23   138.3 2666.87
     157 2667.23   170.2 2666.71   174.6 2666.25     179 2666.45   183.3 2667.96
  188.312670.351   192.1 2672.47   200.9 2678.55   207.9 2682.69     229 2692.29
#Mann= 5 ,-1 , 0
       0      .1       0   85.54     .06       0  111.09    .045       0
  123.19     .06       0  188.31      .1       0
#XS Ineff= 2 , 0
                          150.79         2668.36
Permanent Ineff=
       F       F
Bank Sta=111.09,123.19
XS Rating Curve= 0 ,0
Exp/Cntr(USF)=0,0
Exp/Cntr=0.3,0.1

Type RM Length L Ch R = 1 ,37792   ,115.4,118.1,117
XS GIS Cut Line= 2
2411747.73979885591491.9150858082411987.91111858591516.867950196
#Sta/Elev= 30
       0 2672.94    14.1  2670.4    18.1 2669.95    25.8 2669.58    46.2 2669.23
    62.3 2668.48    74.4 2667.71   77.642667.304    90.5 2665.44    94.5 2664.46
   106.5  2660.5  110.582659.346   114.6 2658.71   122.6 2658.52   126.6 2658.94
  127.412659.291   134.7 2663.18   138.7 2663.66   150.8 2663.34   154.8  2663.9
   170.9 2670.61   174.9 2672.76  180.532676.428   186.7 2680.95   207.1 2697.13
   219.1 2705.52   223.1 2707.85   227.7 2709.78   235.2 2712.32   241.5 2713.78
#Mann= 5 ,-1 , 0
       0      .1       0   77.64     .06       0  110.58    .045       0
  127.41     .06       0  180.53      .1       0
#XS Ineff= 2 , 0
                          138.94         2667.71
Permanent Ineff=
       F       F
Bank Sta=110.58,127.41
XS Rating Curve= 0 ,0
Exp/Cntr(USF)=0,0
Exp/Cntr=0.3,0.1

Type RM Length L Ch R = 1 ,37674   ,140.8,140.4,139.9
XS GIS Cut Line= 2
2411753.97801494591597.9647594552411959.83914614 591629.15583994
#Sta/Elev= 30
       0 2671.23     7.8 2667.44    11.9 2665.86      20 2663.87      24 2663.18
    28.1 2663.01    36.1 2663.21    40.2 2662.85    44.2  2660.1    48.3 2656.27
    52.3 2653.58      552653.027    56.8 2652.73   70.712652.977    76.6 2653.28
    84.7 2655.45   90.092656.027    92.8    2656   100.9 2656.66     113 2658.12
   121.1 2657.66   137.3 2657.69   141.1 2660.28   145.4  2663.6   148.1 2665.35
   177.7  2682.1   185.8 2687.73  194.412693.183   198.8 2695.58   208.2 2699.75
#Mann= 5 ,-1 , 0
       0      .1       0      55    .045       0   70.71      .1       0
   90.09     .06       0  194.41      .1       0
#XS Ineff= 2 , 0
                          112.74          2658.5
Permanent Ineff=
       F       F
Bank Sta=55,70.71
XS Rating Curve= 0 ,0
Exp/Cntr(USF)=0,0
Exp/Cntr=0.3,0.1

Type RM Length L Ch R = 1 ,37534   ,143.7,143.6,143.2
XS GIS Cut Line= 3
2411704.07228617591735.2055135872411891.21876907591753.920161878
2411981.67290248591722.729081393
#Sta/Elev= 30
       0 2676.13    37.8 2663.11    49.9 2658.15   59.692655.401      66 2654.48
      74 2654.13      78 2652.73   85.292646.937    86.1 2646.36    90.1 2645.59
    94.1 2645.57  100.492646.779   106.2 2647.23   118.1 2651.13   122.2 2651.79
   146.4 2652.28   158.4 2651.87  162.472652.809   166.5 2654.64   170.5 2655.76
   186.6 2655.14   190.7 2655.66   194.9 2656.74   199.2 2658.33   220.7 2668.27
     233 2672.93   245.7 2679.97   249.9 2681.94   258.4 2685.42   283.8 2694.61
#Mann= 5 ,-1 , 0
       0      .1       0   59.69     .06       0   85.29    .045       0
  100.49     .06       0  162.47      .1       0
#XS Ineff= 2 , 0
                          130.61          2656.5
Permanent Ineff=
       F       F
Bank Sta=85.29,100.49
XS Rating Curve= 0 ,0
Exp/Cntr(USF)=0,0
Exp/Cntr=0.3,0.1

Type RM Length L Ch R = 1 ,37390   ,123.8,120,114.4
XS GIS Cut Line= 2
2411689.89247441591878.7695661522411956.74949634591899.563619808
#Sta/Elev= 30
       0 2663.13     8.4 2658.16    15.9 2654.57    19.9 2653.13    23.9  2652.3
    39.9 2650.41      44  2649.5      56 2645.63      60 2644.55      64 2643.86
    89.3 2642.74    92.1 2642.47   97.412641.263  103.332640.312   108.1 2639.84
  116.192640.309   126.5 2641.85   136.2 2642.06   148.3 2643.29   152.3 2644.43
   156.2 2646.61   160.3 2648.53   164.3 2648.73   172.3 2648.32  199.622647.948
   228.5 2647.66   236.5 2648.28   252.6 2652.49   260.8    2655   267.7 2657.64
#Mann= 5 ,-1 , 0
       0      .1       0   97.41     .06       0  103.33    .045       0
  116.19     .06       0  199.62      .1       0
Bank Sta=103.33,116.19
XS Rating Curve= 0 ,0
Exp/Cntr(USF)=0,0
Exp/Cntr=0.3,0.1

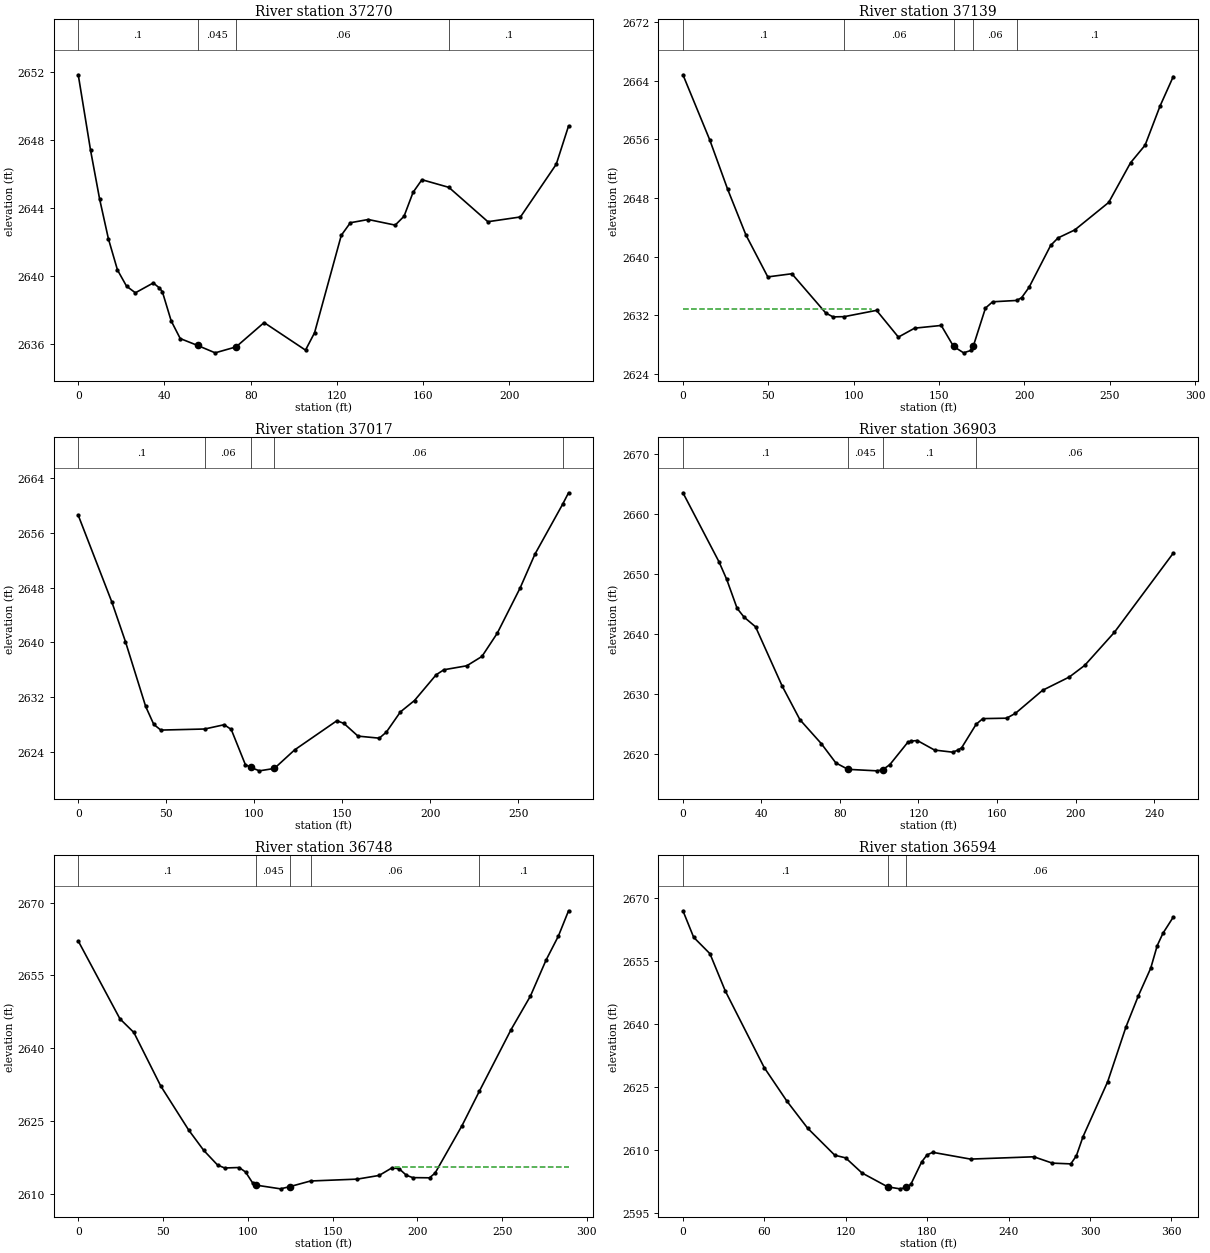
Type RM Length L Ch R = 1 ,37270   ,131.9,131.3,126.7
XS GIS Cut Line= 2
2411736.19566805592019.6397837232411955.16547464591958.246380005
#Sta/Elev= 30
       0 2651.85     5.7 2647.42     9.9 2644.55      14  2642.2    18.2 2640.37
    22.4 2639.42    26.5 2639.03    34.8 2639.61    37.6 2639.32      39  2639.1
    43.1 2637.38    47.3 2636.34    55.42635.932    63.5  2635.5    73.2 2635.85
    86.2 2637.28   105.4 2635.66   109.6 2636.68     122 2642.41   126.2 2643.15
   134.5 2643.34     147 2643.01   151.1 2643.53   155.3 2644.94   159.4 2645.68
   171.9 2645.23     190 2643.21   205.1 2643.49   221.7 2646.59   227.4 2648.84
#Mann= 4 ,-1 , 0
       0      .1       0    55.4    .045       0    73.2     .06       0
   171.9      .1       0
Bank Sta=55.4,73.2
XS Rating Curve= 0 ,0
Exp/Cntr(USF)=0,0
Exp/Cntr=0.3,0.1

Type RM Length L Ch R = 1 ,37139   ,116.8,121.7,124.9
XS GIS Cut Line= 2
2411734.94625733592145.6265880752412005.26895487592048.587671012
#Sta/Elev= 30
       0 2664.82    15.7 2655.93    26.2 2649.18    36.9 2642.94    49.7 2637.22
    63.8 2637.65    83.7 2632.28    87.9 2631.76   94.482631.791   113.4 2632.65
   126.2    2629   135.7 2630.22   151.3 2630.59  158.512627.728   164.4 2626.85
   168.7 2627.18  170.112627.787   177.2 2632.96   181.4 2633.82  195.512634.004
   198.4 2634.39   202.7 2635.78   215.4 2641.52   219.7 2642.54   229.5 2643.63
   249.4 2647.39   262.2 2652.81   270.7  2655.2   279.5 2660.57   287.2 2664.57
#Mann= 5 ,-1 , 0
       0      .1       0   94.48     .06       0  158.51    .045       0
  170.11     .06       0  195.51      .1       0
#XS Ineff= 2 , 0
           110.1 2632.83
Permanent Ineff=
       F       F
Bank Sta=158.51,170.11
XS Rating Curve= 0 ,0
Exp/Cntr(USF)=0,0
Exp/Cntr=0.3,0.1

Type RM Length L Ch R = 1 ,37017   ,119.8,113.6,106.3
XS GIS Cut Line= 3
2411766.89236991592201.7735480852411965.39770859592209.959335247
2412039.06979306592179.262633389
#Sta/Elev= 30
       0 2658.53    19.1 2645.88    26.8 2640.13    38.3 2630.67    42.9 2628.06
    46.9 2627.23    71.82627.385    82.9 2628.01    86.9 2627.32    94.9 2622.21
   97.892621.801   102.9 2621.29  111.392621.638   122.9 2624.34   146.9 2628.59
   150.9  2628.2   158.9 2626.35     171 2626.05     175 2626.93     183 2629.88
     191 2631.54   203.3 2635.29   207.7 2636.02   220.7  2636.6   229.3 2637.96
     238 2641.34     251 2647.94   259.4 2652.86   275.1 2660.12   278.5 2661.81
#Mann= 5 ,-1 , 0
       0      .1       0    71.8     .06       0   97.89    .045       0
  111.39     .06       0   275.1      .1       0
#XS Ineff= 2 , 0
                          149.24         2627.09
Permanent Ineff=
       F       F
Bank Sta=97.89,111.39
XS Rating Curve= 0 ,0
Exp/Cntr(USF)=0,0
Exp/Cntr=0.3,0.1

Type RM Length L Ch R = 1 ,36903   ,151.9,155.5,159.3
XS GIS Cut Line= 2
2411821.58814757592357.0328002482412039.92571096592235.734153919
#Sta/Elev= 30
       0 2663.55    18.4 2652.03    22.3 2649.12    27.6  2644.3    31.1 2642.85
      37 2641.22    50.5 2631.39    59.6 2625.75    70.5 2621.76    77.9 2618.55
   84.092617.481    98.8 2617.23  101.692617.398   105.4 2618.26   114.5 2621.96
   116.4 2622.19   119.4 2622.28   128.2 2620.69   137.4 2620.34     140 2620.67
     142 2621.08  149.392624.993   152.8 2625.93   164.9    2626   169.4 2626.81
   183.2 2630.64   196.9 2632.87   204.7  2634.8   219.8  2640.3   249.8 2653.49
#Mann= 4 ,-1 , 0
       0      .1       0   84.09    .045       0  101.69      .1       0
  149.39     .06       0
#XS Ineff= 2 , 0
                          118.63         2621.94
Permanent Ineff=
       F       F
Bank Sta=84.09,101.69
XS Rating Curve= 0 ,0
Exp/Cntr(USF)=0,0
Exp/Cntr=0.3,0.1

Type RM Length L Ch R = 1 ,36748   ,149.8,153.3,155.8
XS GIS Cut Line= 2
2411845.84787683592481.797122186 2412126.5676012592412.483609998
#Sta/Elev= 30
       0 2662.09    24.6 2646.07    32.8 2643.27    48.6 2632.29    65.1 2623.21
      74 2619.01    82.2 2615.98    86.4 2615.38    94.9 2615.48    98.7 2614.55
   102.8 2612.34  105.082611.844   119.3 2611.09  124.782611.542     1372612.704
   164.6 2613.09   177.5 2613.85   185.2 2615.44   189.4 2615.19   193.5 2613.89
   197.3  2613.4   207.2 2613.36   210.5 2614.34   226.4 2624.12  236.652631.221
   255.3 2643.86   266.7 2650.75   275.9 2658.14   283.2  2663.1   289.2 2668.31
#Mann= 5 ,-1 , 0
       0      .1       0  105.08    .045       0  124.78      .1       0
     137     .06       0  236.65      .1       0
#XS Ineff= 2 , 0
                          186.71         2615.53
Permanent Ineff=
       F       F
Bank Sta=105.08,124.78
XS Rating Curve= 0 ,0
Exp/Cntr(USF)=0,0
Exp/Cntr=0.3,0.1

Type RM Length L Ch R = 1 ,36594   ,100.3,97.8,96.7
XS GIS Cut Line= 3
2411845.84787683592589.2330660772412081.51381827592596.164417296
2412192.41543777592537.247931936
#Sta/Elev= 30
       0 2666.86     7.9 2660.55    19.9 2656.64    31.2 2647.78    59.9 2629.53
    76.6 2621.55    91.9  2615.1   111.9 2608.67   119.9 2608.04   131.9 2604.46
  150.922601.138   159.9 2600.67  164.622601.004   167.9 2601.72   175.9 2607.07
   179.9 2608.76   184.1 2609.36   211.9 2607.75   258.6  2608.3   272.2 2606.79
   285.8 2606.61   289.9 2608.52   294.8 2613.08     313 2626.19   326.5 2639.25
   335.6 2646.63   344.7 2653.19   349.5 2658.57   353.7  2661.5   361.3 2665.35
#Mann= 3 ,-1 , 0
       0      .1       0  150.92    .045       0  164.62     .06       0
Bank Sta=150.92,164.62
XS Rating Curve= 0 ,0
Exp/Cntr(USF)=0,0
Exp/Cntr=0.3,0.1

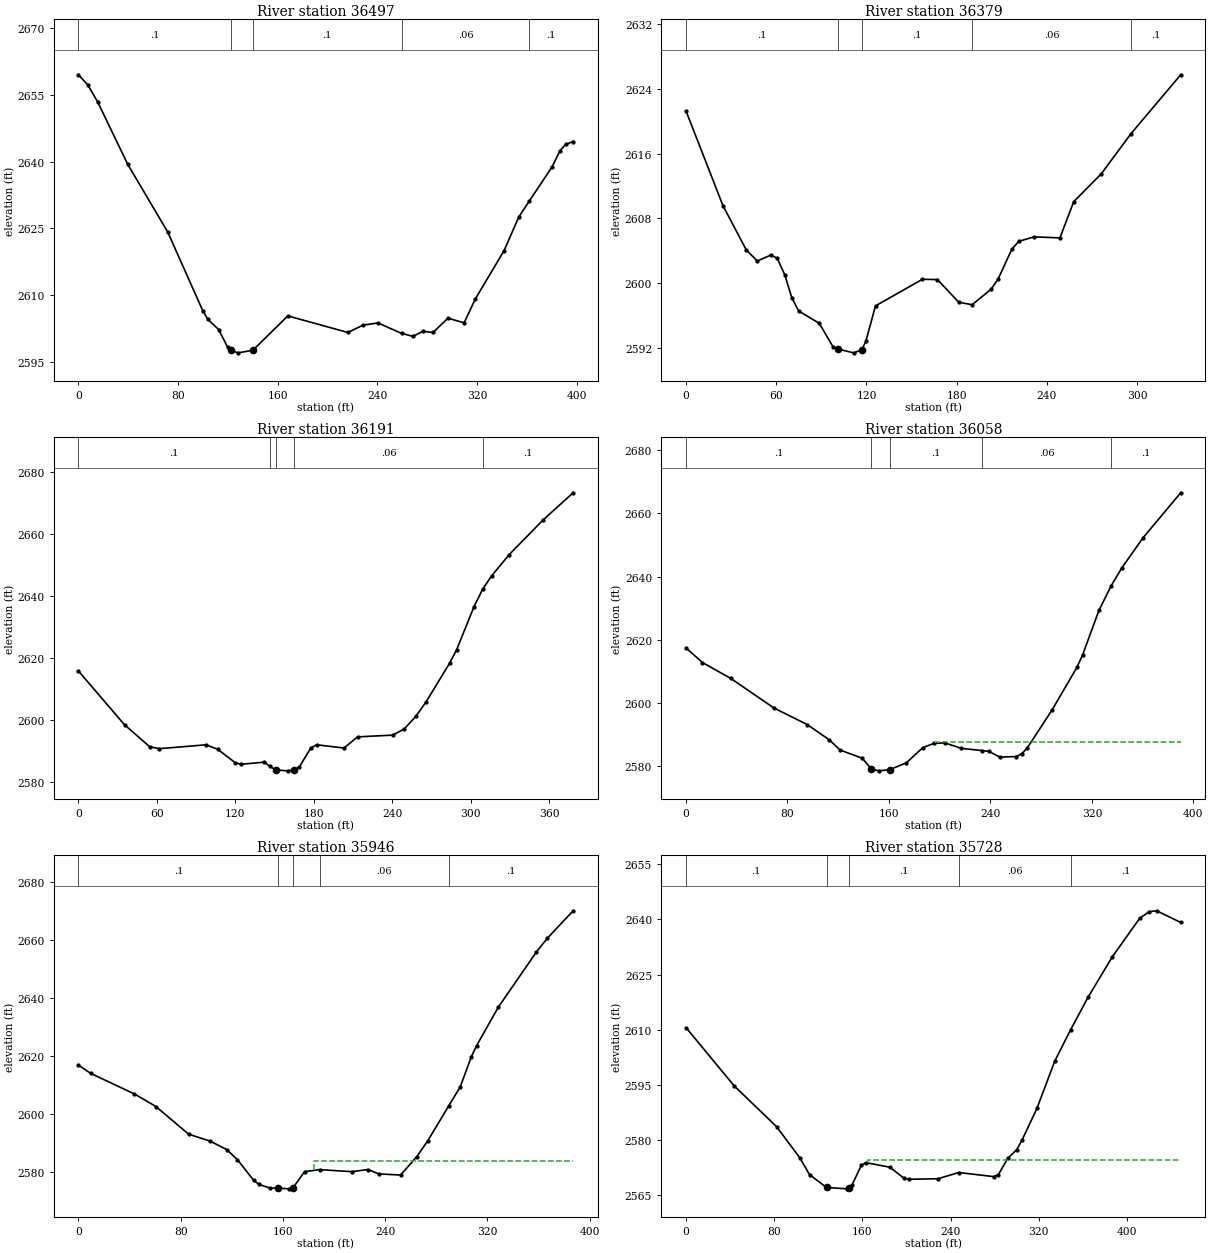
Type RM Length L Ch R = 1 ,36497   ,124.7,117.9,113.6
XS GIS Cut Line= 3
  2411858.354757592701.8901808732412158.72486207592673.818208437
2412242.94077938592628.903052539
#Sta/Elev= 30
       0 2659.52     7.4 2657.28    15.4 2653.44    39.5 2639.43    71.7 2624.17
    99.8 2606.52   103.8 2604.62   112.5  2602.3   119.8  2598.3  122.342597.637
   127.9 2597.06  139.912597.622   168.1 2605.36   216.3 2601.63   228.3 2603.27
   240.4 2603.78  259.342601.435   268.5 2600.76   276.5 2601.89   284.6 2601.63
   296.6 2604.84   309.6 2603.81   318.6 2609.17   341.6 2619.99   353.4 2627.53
  361.992631.199     380 2638.74   386.6 2642.47   391.1 2643.88   397.1 2644.53
#Mann= 5 ,-1 , 0
       0      .1       0  122.34    .045       0  139.91      .1       0
  259.34     .06       0  361.99      .1       0
#XS Ineff= 2 , 0
                          189.85          2603.3
Permanent Ineff=
       F       F
Bank Sta=122.34,139.91
XS Rating Curve= 0 ,0
Exp/Cntr(USF)=0,0
Exp/Cntr=0.3,0.1

Type RM Length L Ch R = 1 ,36379   ,187.1,187.6,188.3
XS GIS Cut Line= 2
2411960.21517194592831.8303587342412247.86624752592672.409280702
#Sta/Elev= 30
       0 2621.25    24.6 2609.56    40.1 2604.11    47.4 2602.75    56.6  2603.5
    60.7 2603.08    65.7 2601.03    70.3 2598.24    74.9 2596.59    88.6 2595.07
    97.7 2592.19  101.192591.891   111.4 2591.43  116.932591.786   119.6 2592.87
     126 2597.22   157.2  2600.5   167.2 2600.46   181.3 2597.67  190.232597.364
   202.9 2599.28   207.5 2600.53   216.6 2604.19   221.2 2605.17   231.4 2605.73
   248.6  2605.6   257.8 2610.07   276.1  2613.5  295.782618.429   328.9 2625.71
#Mann= 5 ,-1 , 0
       0      .1       0  101.19    .045       0  116.93      .1       0
  190.23     .06       0  295.78      .1       0
Bank Sta=101.19,116.93
XS Rating Curve= 0 ,0
Exp/Cntr(USF)=0,0
Exp/Cntr=0.3,0.1

Type RM Length L Ch R = 1 ,36191   ,131.2,132.9,132.6
XS GIS Cut Line= 2
2412026.06300852592994.7171123752412365.69921824592828.364683125
#Sta/Elev= 30
       0 2615.69    35.2 2598.33    54.5 2591.22    61.9 2590.61    97.6 2591.86
   106.5 2590.39   119.8  2586.1   124.3 2585.57   142.1 2586.26  146.382584.876
     151 2583.73   159.9 2583.45  165.092583.808   168.8 2584.65   177.7 2590.87
   182.2 2591.86     203 2590.82   213.4 2594.42   240.1 2594.98     249 2596.94
   257.9 2601.03   265.8 2605.73   283.7 2618.19   289.1 2622.55   302.4 2636.45
  308.932642.061   315.8 2646.36   329.1 2653.19   355.4 2664.54   378.2 2673.25
#Mann= 5 ,-1 , 0
       0      .1       0  146.38     .06       0     151    .045       0
  165.09     .06       0  308.93      .1       0
Bank Sta=151,165.09
XS Rating Curve= 0 ,0
Exp/Cntr(USF)=0,0
Exp/Cntr=0.3,0.1

Type RM Length L Ch R = 1 ,36058   ,111,112.2,111.2
XS GIS Cut Line= 2
 2412057.6657613593108.9337811972412416.98700848592957.345130042
#Sta/Elev= 30
       0 2617.45      13 2612.82    35.3 2607.81    69.5 2598.41    95.5 2593.24
   112.9 2588.42   121.6 2585.15   138.9  2582.6   146.1 2579.18     152  2578.6
   160.6 2578.97   173.7 2581.13   186.7 2585.93   195.4 2587.27     204 2587.44
   217.1  2585.7  233.072585.025   238.8 2584.75   247.5 2582.94   260.5 2583.12
   264.8 2584.01   269.2 2585.92   288.7 2597.91   308.2 2611.31   312.6 2615.15
   325.6 2629.35  335.282637.143   343.6 2642.75   360.3 2652.24     390 2666.48
#Mann= 5 ,-1 , 0
       0      .1       0   146.1    .045       0   160.6      .1       0
  233.07     .06       0  335.28      .1       0
#XS Ineff= 2 , 0
                          196.62         2587.84
Permanent Ineff=
       F       F
Bank Sta=146.1,160.6
XS Rating Curve= 0 ,0
Exp/Cntr(USF)=0,0
Exp/Cntr=0.3,0.1

Type RM Length L Ch R = 1 ,35946   ,219,218.2,217.9
XS GIS Cut Line= 2
2412112.70489876593192.2606221112412476.60083774593060.564948954
#Sta/Elev= 30
       0 2616.89     9.5 2614.04    43.6 2606.99    60.6 2602.63    86.1 2593.13
   103.1 2590.69   115.9 2587.82   124.4 2584.32   137.1  2577.2   141.4 2575.79
   149.9 2574.54   156.42574.568   164.4 2574.29   167.5 2574.42   176.9 2580.22
  188.762580.897   213.7 2580.21   226.5 2580.93     235 2579.43     252 2579.04
   264.7 2585.37   273.3 2590.85  289.83 2602.97   298.7  2609.4   307.3 2619.69
   311.5 2623.59   328.5 2636.85   358.3 2655.84   366.8 2660.54     387    2670
#Mann= 5 ,-1 , 0
       0      .1       0   156.4    .045       0   167.5      .1       0
  188.76     .06       0  289.83      .1       0
#XS Ineff= 2 , 0
                          183.99         2583.76
Permanent Ineff=
       F       F
Bank Sta=156.4,167.5
XS Rating Curve= 0 ,0
Exp/Cntr(USF)=0,0
Exp/Cntr=0.3,0.1

Type RM Length L Ch R = 1 ,35728   ,274.1,267.1,263.5
XS GIS Cut Line= 2
2412188.94976216593396.735483065 2412608.2965109593237.314405033
#Sta/Elev= 30
       0  2610.6    43.6 2594.78    82.1 2583.69   103.5 2575.09     112 2570.65
  127.462567.148   146.3 2566.78  147.812567.073   150.5 2567.79   159.1 2573.22
   163.4 2573.88   184.8 2572.66   197.6 2569.69   201.9 2569.38   228.5 2569.52
  247.322571.216   278.9  2570.1   283.2 2570.59   291.7 2575.05   299.8 2577.37
   304.6 2579.95   318.4 2588.74   334.5 2601.55  348.722609.963   364.5 2618.78
   386.6 2629.83   411.5 2640.32   420.1 2642.09   426.9 2642.33   448.6 2639.16
#Mann= 5 ,-1 , 0
       0      .1       0  127.46    .045       0  147.81      .1       0
  247.32     .06       0  348.72      .1       0
#XS Ineff= 2 , 0
                          165.16          2574.6
Permanent Ineff=
       F       F
Bank Sta=127.46,147.81
XS Rating Curve= 0 ,0
Exp/Cntr(USF)=0,0
Exp/Cntr=0.3,0.1

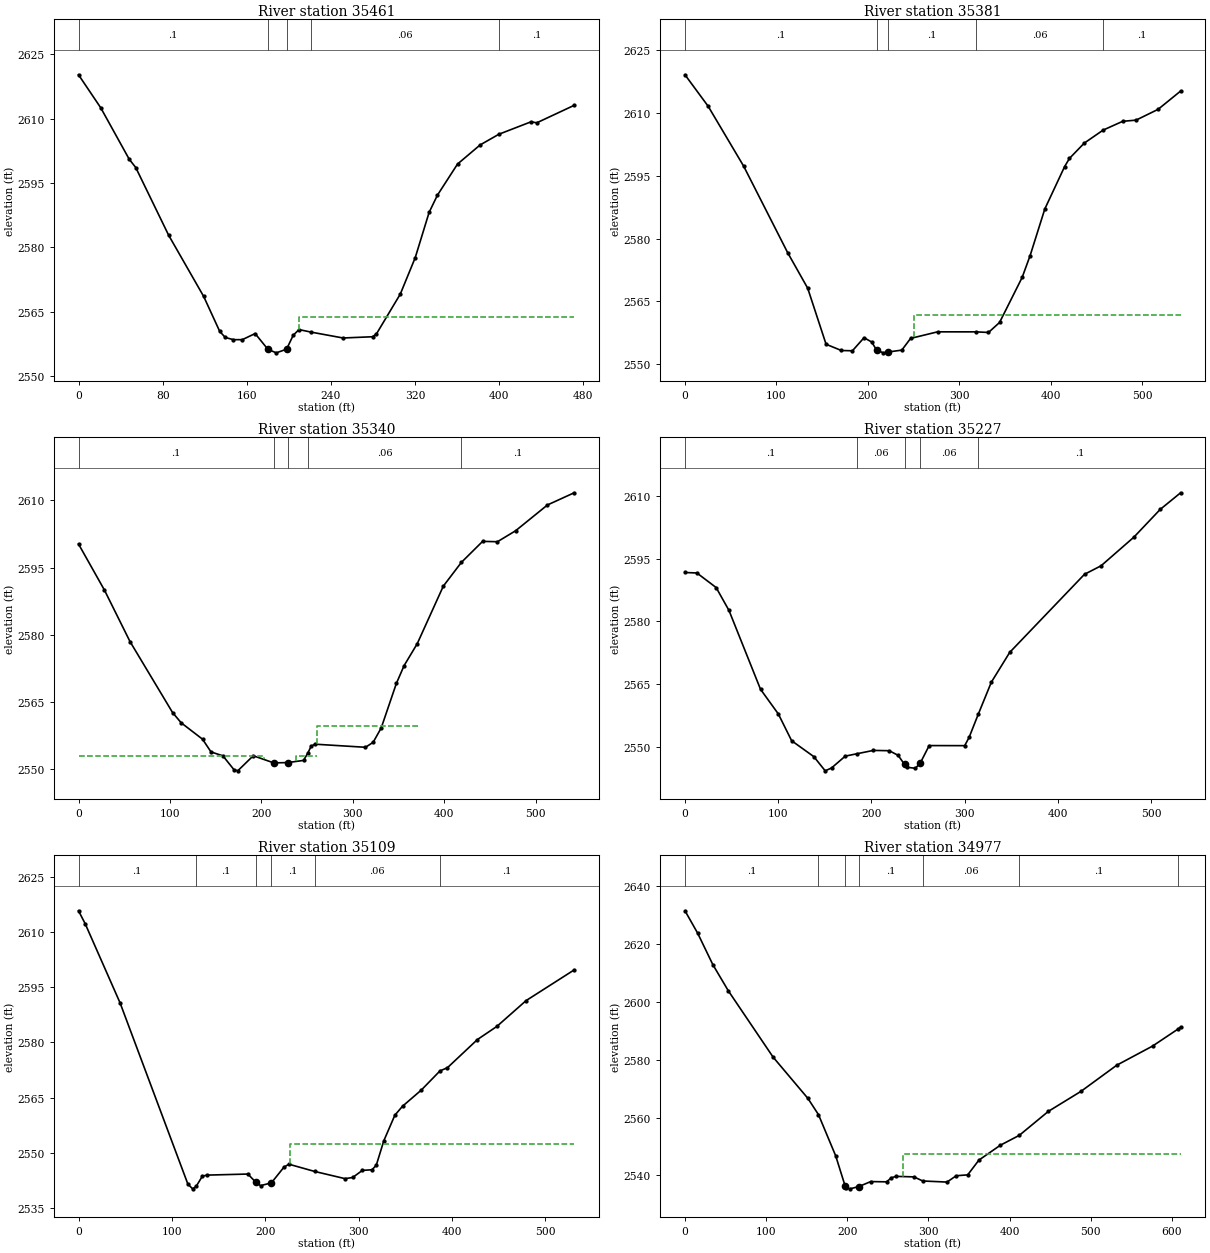
Type RM Length L Ch R = 1 ,35461   ,84.1,79.9,74
XS GIS Cut Line= 2
2412337.97381337593667.0581805972412688.00704992593351.681700143
#Sta/Elev= 30
       0 2620.22    21.1 2612.54    48.2 2600.54    54.4 2598.61    85.7 2582.82
     119 2568.56   134.2 2560.44   139.5    2559   147.3 2558.49   155.7 2558.49
   167.9 2559.91  180.082556.234     188 2555.42  197.782556.266   204.1 2559.51
   209.6 2560.84  221.492560.233   251.5 2558.88   279.5 2559.17   283.2 2559.82
   305.9 2569.11   320.1  2577.6   333.3 2588.15   341.2 2592.16   360.3 2599.41
   381.8 2603.87  399.672606.365   430.3 2609.27   435.6 2609.02   471.2  2613.1
#Mann= 5 ,-1 , 0
       0      .1       0  180.08    .045       0  197.78      .1       0
  221.49     .06       0  399.67      .1       0
#XS Ineff= 2 , 0
                          209.99         2563.75
Permanent Ineff=
       F       F
Bank Sta=180.08,197.78
XS Rating Curve= 0 ,0
Exp/Cntr(USF)=0,0
Exp/Cntr=0.5,0.3

Type RM Length L Ch R = 1 ,35381   ,40.7,41.1,41.8
XS GIS Cut Line= 4
2412365.31535639593743.6563177112412500.73202294593662.493123263
2412568.44035634593466.7465954722412699.95077296593348.257012144
#Sta/Elev= 30
       0 2619.16    25.3 2611.65    64.2  2597.3   112.3 2576.62   134.2 2568.13
   154.3 2554.73     171 2553.24   183.1 2553.17   195.8  2556.3   204.2 2555.26
  209.612553.318   216.9 2552.68  221.81 2552.87   237.1 2553.33   246.7 2556.13
   276.2  2557.7  318.252557.696   331.9 2557.55     344 2559.94   368.7 2570.71
   377.4 2575.92   393.5 2587.09   415.1 2597.19   420.4 2599.16   436.6 2602.82
  457.23 2605.93   478.6 2608.03   493.3 2608.32   517.3 2610.89     542 2615.27
#Mann= 5 ,-1 , 0
       0      .1       0  209.61    .045       0  221.81      .1       0
  318.25     .06       0  457.23      .1       0
#XS Ineff= 2 , 0
                          250.96         2561.76
Permanent Ineff=
       F       F
Bank Sta=209.61,221.81
XS Rating Curve= 0 ,0
Exp/Cntr(USF)=0,0
Exp/Cntr=0.5,0.3

Type RM Length L Ch R = 1 ,35340   ,107.6,112.3,114.2
XS GIS Cut Line= 4
2412401.33966194593763.187567711 2412536.7563285593682.024373263
 2412604.4646619593486.2778454722412735.97507851593367.788262144
#Sta/Elev= 30
       0 2600.26    28.3 2589.99    56.3 2578.48   102.9 2562.61   112.3 2560.33
   135.6 2556.68   144.9 2553.83   157.9 2552.96   169.9 2549.89   174.1 2549.61
   191.1 2552.98  213.612551.379  229.112551.461   246.1 2551.94  250.562553.504
   254.5 2555.14   258.7 2555.56   313.8 2554.87   322.2 2555.98     331 2559.19
   347.6 2569.14   356.1 2573.13   370.4    2578   398.9 2590.85  418.64 2596.15
   441.9 2600.85   458.1 2600.77   477.9 2603.21   512.8 2608.98     542  2611.7
#Mann= 5 ,-1 , 0
       0      .1       0  213.61    .045       0  229.11      .1       0
  250.56     .06       0  418.64      .1       0
#XS Ineff= 4 ,-1
       0   202.5    2553   237.5  260.43    2553  260.43  371.36 2559.68
  371.36     542    2553
Permanent Ineff=
       F       F       F       F
Bank Sta=213.61,229.11
XS Rating Curve= 0 ,0
Exp/Cntr(USF)=0,0
Exp/Cntr=0.5,0.3

Type RM Length L Ch R = 1 ,35227   ,116.8,118.6,119.8
XS GIS Cut Line= 3
2412532.05164753593850.7389879082412708.80110358 593576.95061475
2412735.54105078593372.996595472
#Sta/Elev= 30
       0 2591.68    12.8 2591.56    33.4 2588.08    47.2 2582.59      81 2563.72
   100.1 2557.81   114.4 2551.39   138.2 2547.58   150.4 2544.18   157.2 2544.87
   171.9  2547.7  184.072548.256     202 2549.07   219.1    2549   228.6 2547.89
  235.492545.713   238.4 2545.04   247.1 2544.78  252.392546.057   261.9 2550.23
     300 2550.21   304.8 2552.22  314.642557.785   328.6 2565.42   348.3 2572.55
   428.5 2591.25   446.3 2593.29   481.5 2600.15   509.7 2606.79   531.6 2610.77
#Mann= 5 ,-1 , 0
       0      .1       0  184.07     .06       0  235.49    .045       0
  252.39     .06       0  314.64      .1       0
Bank Sta=235.49,252.39
XS Rating Curve= 0 ,0
Exp/Cntr(USF)=0,0
Exp/Cntr=0.3,0.1

Type RM Length L Ch R = 1 ,35109   ,131.4,131.6,130.3
XS GIS Cut Line= 3
2412621.91240726593880.913023189 2412824.0306088593636.686862995
2412840.87379227593423.339872481
#Sta/Elev= 30
       0 2615.88     7.1 2612.38    44.5  2590.8   117.2  2541.4   122.3 2540.13
  125.972540.772   132.7 2543.58   137.6 2543.87   181.5 2544.16  189.812541.947
     195    2541  206.612541.752   220.1 2546.04   225.4 2546.84  252.892544.874
   285.5 2542.91   293.7 2543.22   304.1 2545.16   314.4 2545.32     319 2546.56
   327.1 2553.24   338.9 2560.19   347.1 2562.63   367.2 2567.03  387.242572.254
   395.3 2573.14   427.4 2580.81   448.2 2584.38   479.5 2591.41     531 2599.77
#Mann= 6 ,-1 , 0
       0      .1       0  125.97      .1       0  189.81    .045       0
  206.61      .1       0  252.89     .06       0  387.24      .1       0
#XS Ineff= 2 , 0
                          226.07         2552.34
Permanent Ineff=
       F       F
Bank Sta=189.81,206.61
XS Rating Curve= 0 ,0
Exp/Cntr(USF)=0,0
Exp/Cntr=0.3,0.1

Type RM Length L Ch R = 1 ,34977   ,94.5,97.4,98.2
XS GIS Cut Line= 3
2412712.26677918 593989.366012272412930.60434257593698.249261081
2412909.81028892593452.186292815
#Sta/Elev= 30
       0  2631.5    15.6 2623.77    34.3  2612.9    53.4 2603.84   108.6 2580.91
   151.5 2566.64  164.532561.024   185.7 2546.81  197.212536.494   198.4  2535.8
   203.4 2535.38  214.31 2536.18   228.9 2537.89   248.4  2537.8   254.3 2539.19
     260 2539.69   282.2 2539.51  292.972538.096   322.9 2537.72   334.3 2539.91
   348.4 2540.21   362.2 2545.31   388.6 2550.45  412.012553.876   447.8 2562.16
   487.9 2569.06   532.1 2578.12   576.2 2584.73  607.542590.605   610.8 2591.33
#Mann= 7 ,-1 , 0
       0      .1       0  164.53      .1       0  197.21    .045       0
  214.31      .1       0  292.97     .06       0  412.01      .1       0
  607.54      .1       0
#XS Ineff= 2 , 0
                          268.35         2547.48
Permanent Ineff=
       F       F
Bank Sta=197.21,214.31
XS Rating Curve= 0 ,0
Exp/Cntr(USF)=0,0
Exp/Cntr=0.3,0.1

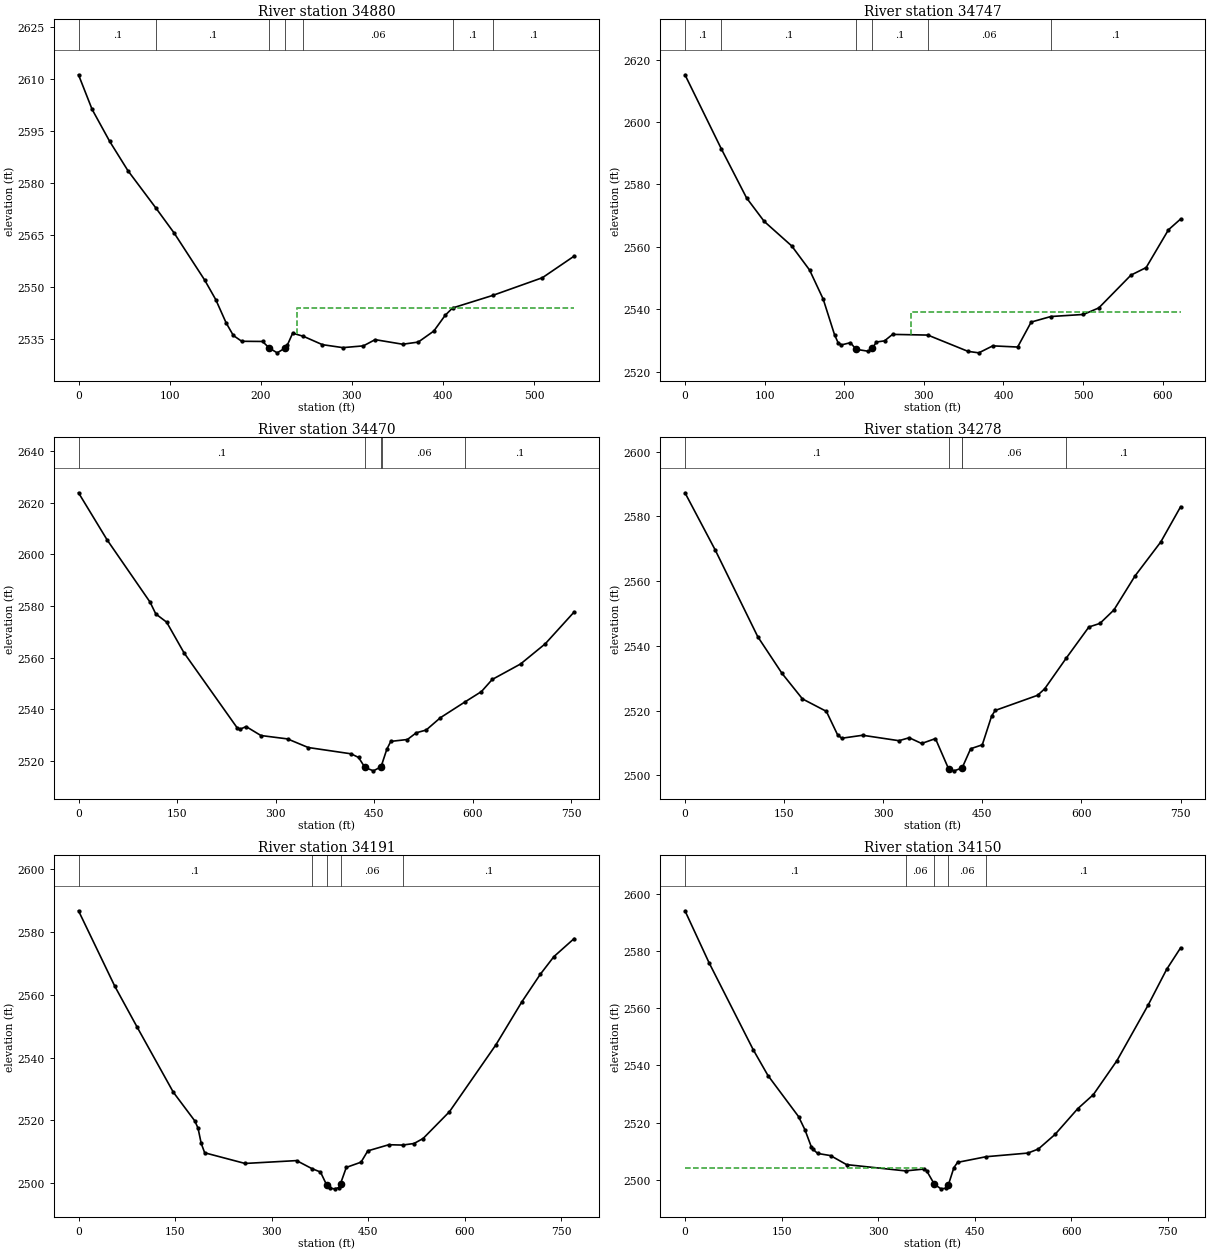
Type RM Length L Ch R = 1 ,34880   ,131.4,133.1,134.4
XS GIS Cut Line= 2
2412767.88666393 594021.272885372413149.66548906593633.879665751
#Sta/Elev= 30
       0 2611.17    14.9 2601.21    34.2 2591.98    54.2 2583.54   85.16 2572.68
   104.9 2565.58   138.5 2551.98   150.6 2546.37     162 2539.66   169.9 2536.03
   179.1 2534.36   201.9 2534.31   209.5 2532.38     218 2531.03   226.5 2532.38
   229.3 2533.34     235  2536.7  246.872535.781   267.6 2533.39   290.1 2532.53
   312.6 2533.04   325.5 2534.83   355.7 2533.51   372.8 2534.13   389.9 2537.31
   402.4 2541.86  410.512543.966  454.43 2547.57   509.1 2552.69   543.9 2558.91
#Mann= 7 ,-1 , 0
       0      .1       0   85.16      .1       0   209.5    .045       0
   226.5      .1       0  246.87     .06       0  410.51      .1       0
  454.43      .1       0
#XS Ineff= 2 , 0
                          239.87         2543.81
Permanent Ineff=
       F       F
Bank Sta=209.5,226.5
XS Rating Curve= 0 ,0
Exp/Cntr(USF)=0,0
Exp/Cntr=0.3,0.1

Type RM Length L Ch R = 1 ,34747   ,278.5,276.6,276.2
XS GIS Cut Line= 3
2412812.77137185594117.5960098182413041.50596207593937.380878129
2413263.30920108593691.317909863
#Sta/Elev= 30
       0 2615.16   45.552591.453    77.4 2575.65    99.5 2568.14   134.1 2560.26
   156.5 2552.54   173.6 2543.21   187.8 2531.82   192.2  2529.3   196.4 2528.53
   207.8 2529.24  214.892527.124   230.2  2526.5  235.292527.427   240.4 2529.46
   250.6 2529.83   260.7 2531.91  305.032531.685   355.5 2526.46     369 2525.99
   386.6 2528.23   417.8 2527.85   434.8 2535.86  459.552537.639   500.4  2538.3
   519.7 2540.39   560.1 2550.91   579.2 2553.34   607.2 2565.45   622.5 2568.91
#Mann= 6 ,-1 , 0
       0      .1       0   45.55      .1       0  214.89    .045       0
  235.29      .1       0  305.03     .06       0  459.55      .1       0
#XS Ineff= 2 , 0
                          284.45         2539.05
Permanent Ineff=
       F       F
Bank Sta=214.89,235.29
XS Rating Curve= 0 ,0
Exp/Cntr(USF)=0,0
Exp/Cntr=0.3,0.1

Type RM Length L Ch R = 1 ,34470   ,189.9,192.6,194
XS GIS Cut Line= 3
2412850.89380356594280.4827634592413193.99568889 594103.73330738
2413440.05865715593829.944934238
#Sta/Elev= 30
       0 2623.81    43.5  2605.6   108.9  2581.5   117.6 2576.94   134.1 2573.77
   160.5 2561.92   241.5 2532.86     246 2532.39     255 2533.39   277.5 2529.93
     318 2528.62   349.5 2525.29   414.8 2522.85   426.1 2521.44  435.782517.577
   448.7 2516.27  459.582517.742  461.162518.521   469.1 2524.64   475.1 2527.66
   500.4 2528.39   513.9 2530.99   528.9 2532.05   550.7 2536.84  588.672543.035
     613 2546.92   629.4  2551.6   672.5 2557.59   710.1  2565.4   754.1 2577.72
#Mann= 5 ,-1 , 0
       0      .1       0  435.78    .045       0  459.58      .1       0
  461.16     .06       0  588.67      .1       0
Bank Sta=435.78,459.58
XS Rating Curve= 0 ,0
Exp/Cntr(USF)=0,0
Exp/Cntr=0.3,0.1

Type RM Length L Ch R = 1 ,34278   ,84.7,86.1,87
XS GIS Cut Line= 3
     2413051.006      594466.854 2413423.3271878594143.684217078
2413499.17751709593897.907217078
#Sta/Elev= 30
       0 2587.26    45.8 2569.58   110.2 2542.79   146.8  2531.5   177.8  2523.6
     214 2519.75   231.1 2512.46   237.3 2511.45   268.9 2512.37   323.8 2510.69
   339.4  2511.6   358.2 2509.83   379.1 2511.34  398.912502.038   407.4 2501.38
  418.822502.225     420 2502.52   432.4 2508.21     450 2509.42   464.1 2518.28
   469.5 2520.03   533.7 2524.71   544.4 2526.71  576.852536.131   611.3  2545.8
   628.1 2546.92   649.2 2551.06   681.1 2561.56   720.2 2572.09   750.2 2582.96
#Mann= 5 ,-1 , 0
       0      .1       0  398.91    .045       0  418.82      .1       0
     420     .06       0  576.85      .1       0
Bank Sta=398.91,418.82
XS Rating Curve= 0 ,0
Exp/Cntr(USF)=0,0
Exp/Cntr=0.5,0.3

Type RM Length L Ch R = 1 ,34191   ,41.2,41.3,41.2
XS GIS Cut Line= 3
2413092.31188408  594503.20492882413459.49938411 594231.50353992
2413515.48896742593923.343817711
#Sta/Elev= 30
       0 2586.79    56.3 2562.77    91.1  2549.7   147.2 2528.99   180.7 2519.81
   185.7 2517.49   190.6 2512.66     196 2509.66   258.7 2506.26   338.8 2507.17
  362.552504.616   375.9 2503.53  385.692499.313   390.2 2498.34   397.8 2498.17
   404.6 2498.57  407.092499.845     416    2505   438.9 2506.67   449.4 2510.27
   482.1 2512.23  503.422512.116   521.2 2512.62   535.3 2514.21   576.3 2522.76
   648.5  2544.1   688.8 2557.79   717.3 2566.53   738.5 2572.18     770 2577.94
#Mann= 5 ,-1 , 0
       0      .1       0  362.55     .06       0  385.69    .045       0
  407.09     .06       0  503.42      .1       0
#XS Ineff= 2 , 0
             370    2503     420            2503
Permanent Ineff=
       F       F
Bank Sta=385.69,407.09
XS Rating Curve= 0 ,0
Exp/Cntr(USF)=0,0
Exp/Cntr=0.5,0.3

Type RM Length L Ch R = 1 ,34150   ,74.9,72,69.4
XS GIS Cut Line= 3
2413115.74938408594537.0590954672413482.93688411594265.357706587
2413538.92646742593957.197984378
#Sta/Elev= 30
       0    2594    37.4 2575.84     106 2545.45   128.9 2536.43   176.4 2522.08
   186.4 2517.44   196.3 2511.48   199.2 2510.58   206.1 2509.19   226.1 2508.44
     251 2505.29  342.622503.087     372 2503.75   375.4 2503.14  387.392498.443
   397.7 2496.82   405.3 2497.03  409.092498.146   417.7 2504.19   423.4 2506.07
  467.872508.051   532.7 2509.32     549 2510.74   574.9 2515.84     610  2524.8
   634.4 2529.74     671  2541.6   719.4 2560.99   748.2  2573.5     770 2581.07
#Mann= 5 ,-1 , 0
       0      .1       0  342.62     .06       0  387.39    .045       0
  409.09     .06       0  467.87      .1       0
#XS Ineff= 2 , 0
          370.42 2504.17
Permanent Ineff=
       F       F
Bank Sta=387.39,409.09
XS Rating Curve= 0 ,0
Exp/Cntr(USF)=0,0
Exp/Cntr=0.5,0.3