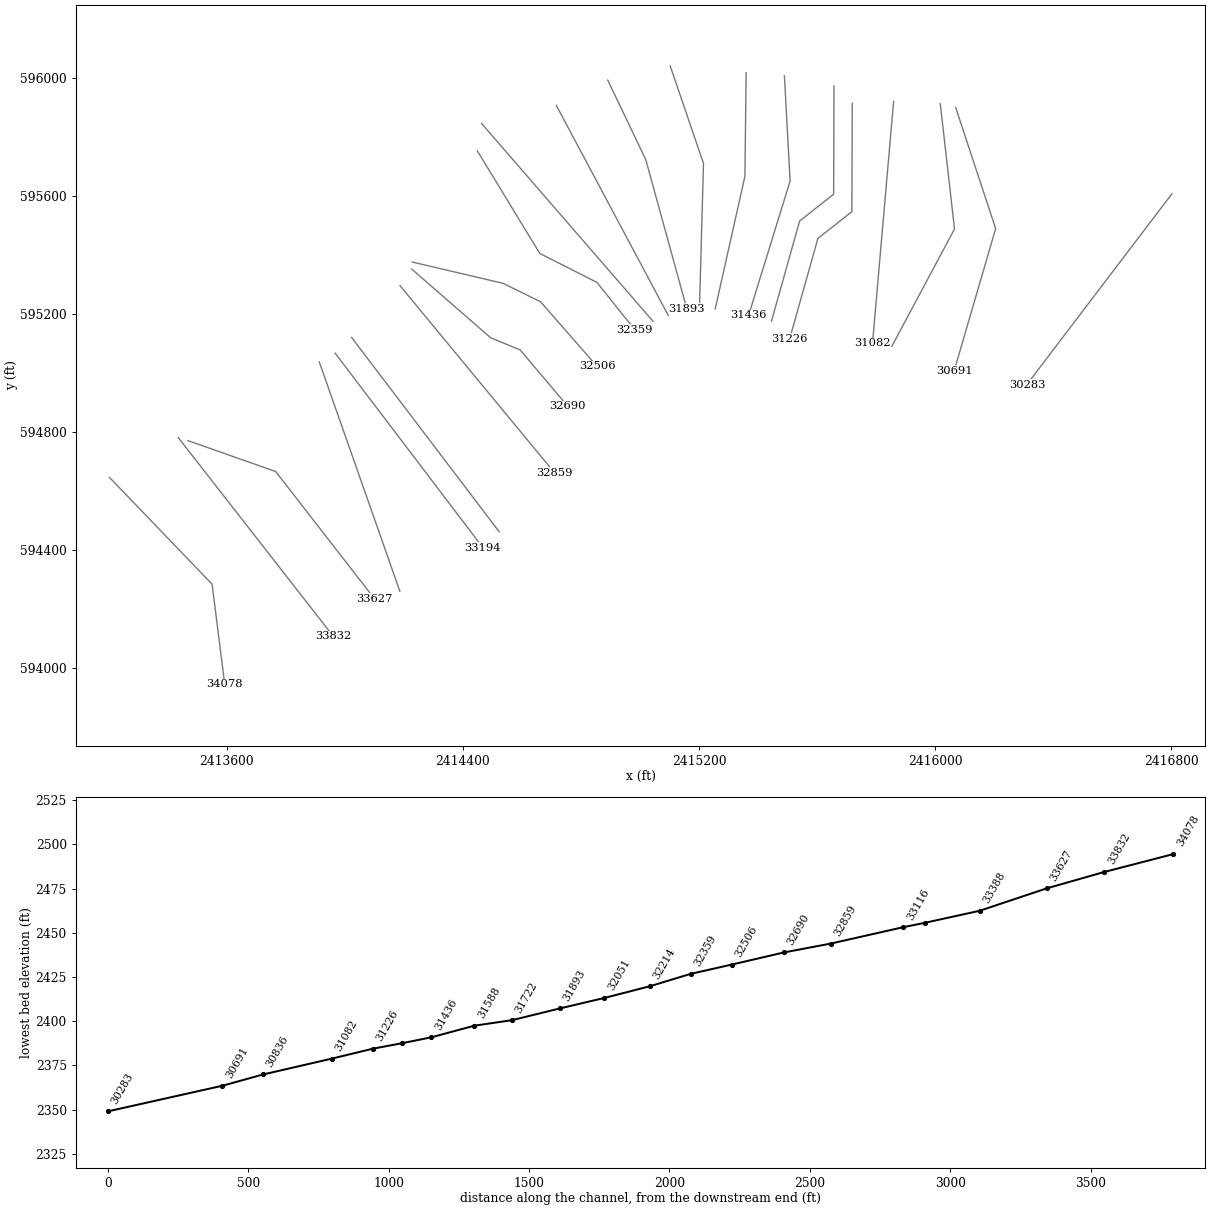
HEC-RAS study SMITHCK.prj: SMITHCK

--- SMITHCK.g01 (geometry) --- (continued)

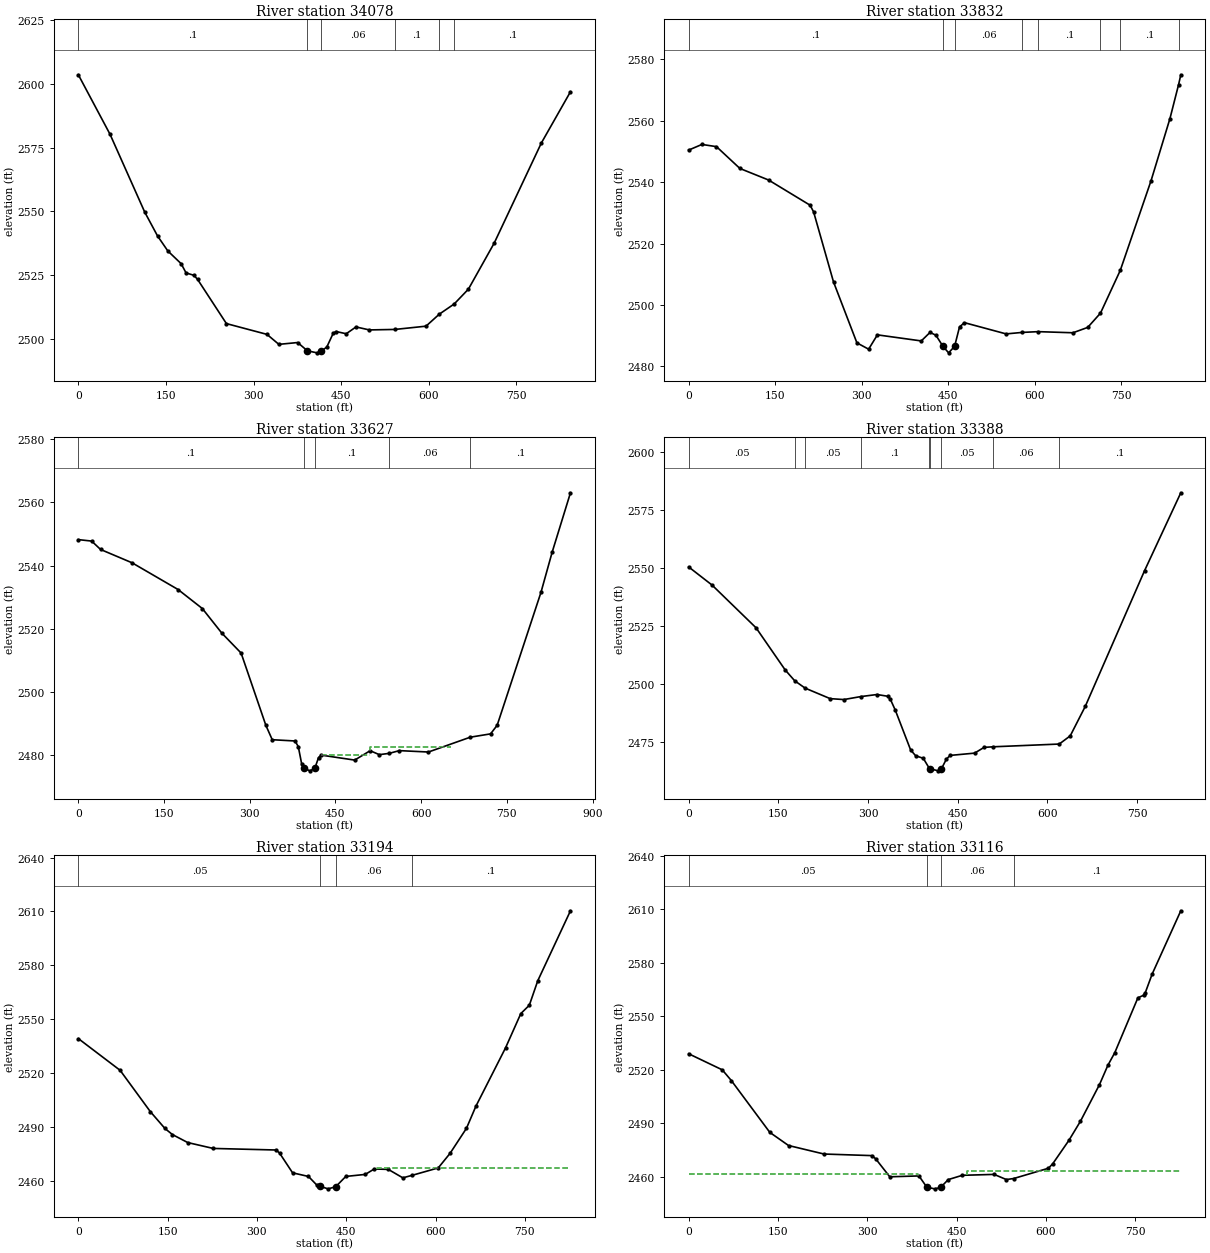
Type RM Length L Ch R = 1 ,34078   ,251.1,246.3,246.4
XS GIS Cut Line= 3
2413203.62648536594645.4661609692413550.96027666594283.948439069
2413593.73535367593945.197919516
#Sta/Elev= 30
       0 2603.59    54.3 2580.24   113.7 2549.72   135.6 2540.38   153.3 2534.47
     176  2529.5   184.5 2525.86   198.1 2524.91   204.3 2523.29   253.6 2505.98
   323.1 2501.75   343.4 2497.84   375.6 2498.55  392.292495.302   408.9 2494.51
  416.392495.268   425.5 2496.77   436.6 2502.24   441.5 2502.87   458.8    2502
   475.5 2504.67   498.4  2503.5  542.22 2503.69   595.4 2504.97  618.192509.685
  643.692513.682     668 2519.49   712.2 2537.56   792.9 2576.81   842.8 2596.93
#Mann= 6 ,-1 , 0
       0      .1       0  392.29    .045       0  416.39     .06       0
  542.22      .1       0  618.19      .1       0  643.69      .1       0
Bank Sta=392.29,416.39
XS Rating Curve= 0 ,0
Exp/Cntr(USF)=0,0
Exp/Cntr=0.3,0.1

Type RM Length L Ch R = 1 ,33832   ,205.4,205.2,205.8
XS GIS Cut Line= 2
     2413436.317      594780.568     2413961.158      594107.777
#Sta/Elev= 30
       0 2550.46    22.9  2552.3    48.2 2551.58    88.8 2544.47   138.5 2540.71
   210.5  2532.5   216.6 2530.32   251.1 2507.51   291.7 2487.64     312 2485.58
   327.2 2490.25   403.3 2488.27   418.5 2491.05   428.7 2490.12  441.092486.464
   450.7 2484.39  461.092486.514   469.6 2492.84   478.2 2494.22   550.4 2490.56
  578.572491.051  605.972491.294   666.3 2490.93   691.9 2492.68     7142497.323
  748.412511.294   801.8 2540.54   834.5 2560.75  849.432571.789   853.3    2575
#Mann= 8 ,-1 , 0
       0      .1       0  441.09    .045       0  461.09     .06       0
  578.57      .1       0  605.97      .1       0     714      .1       0
  748.41      .1       0  849.43      .1       0
#XS Ineff= 2 , 0
          421.71 2488.92
Permanent Ineff=
       F       F
Bank Sta=441.09,461.09
XS Rating Curve= 0 ,0
Exp/Cntr(USF)=0,0
Exp/Cntr=0.3,0.1

Type RM Length L Ch R = 1 ,33627   ,243,238.7,234.2
XS GIS Cut Line= 3
2413468.80465614594770.2816805152413766.33565123594665.495782922
     2414101.112      594234.267
#Sta/Elev= 30
       0  2548.2    23.3 2547.74    38.9 2545.09    94.1 2540.87   174.6 2532.42
     217 2526.42   251.2 2518.63   284.9 2512.34   328.3 2489.46   339.4 2484.94
   379.3 2484.54     385 2482.76     391 2477.22  395.092475.962   405.2  2475.1
  413.882475.856   420.4 2479.27     425 2480.07   483.7  2478.5   510.8 2481.46
   526.8 2480.22  543.882480.615   561.9 2481.49   612.8 2481.05  685.982485.735
   721.6 2486.79   733.1 2489.51   809.8 2531.54   829.3 2544.19   861.4 2563.01
#Mann= 5 ,-1 , 0
       0      .1       0  395.09    .045       0  413.88      .1       0
  543.88     .06       0  685.98      .1       0
#XS Ineff= 3 ,-1
  424.85  511.21 2480.26  511.21  652.43 2482.63  652.43   861.4 2480.26
Permanent Ineff=
       F       F       F
Bank Sta=395.09,413.88
XS Rating Curve= 0 ,0
Exp/Cntr(USF)=0,0
Exp/Cntr=0.3,0.1

Type RM Length L Ch R = 1 ,33388   ,189.1,194.3,199.5
XS GIS Cut Line= 2
      2413913.98      595036.844      2414186.85      594260.071
#Sta/Elev= 30
       0 2550.54    39.1 2542.71   112.7 2524.25   161.4 2506.05  177.322501.368
  194.762498.184   236.7 2493.64   259.5 2493.24  287.982494.527   315.1 2495.42
   333.1 2494.66   337.4 2493.37   345.8 2488.57   371.3 2471.47   379.7 2468.96
   392.5 2467.85  402.472463.556   403.2 2463.34   417.9 2462.44   422.8  2463.3
   431.2 2467.54   437.5 2469.11   478.3 2470.09   494.2 2472.58  509.282472.829
  619.932474.016   638.3 2477.55   663.4 2490.26   762.6  2548.9   823.3 2582.59
#Mann= 9 ,-1 , 0
       0     .05       0  177.32      .1       0  194.76     .05       0
  287.98      .1       0  402.47     .05       0   403.2    .045       0
   422.8     .05       0  509.28     .06       0  619.93      .1       0
Bank Sta=403.2,422.8
XS Rating Curve= 0 ,0
Exp/Cntr(USF)=0,0
Exp/Cntr=0.5,0.3

Type RM Length L Ch R = 1 ,33194   ,78.2,77.9,78.8
XS GIS Cut Line= 2
2413967.74591185595066.3993732582414467.74591183 594408.06603993
#Sta/Elev= 30
       0 2539.27    70.2 2521.61     121  2498.6   145.5 2489.24   158.1 2485.86
   183.8 2481.41   226.6 2478.14   332.3 2477.27     338 2475.57   359.9 2464.57
   386.6 2462.55   400.8  2457.7  406.692457.011   419.5 2455.66  432.192456.788
   449.3 2462.56     482 2463.69   497.1 2466.71   520.7 2466.48   545.1 2461.78
  560.212463.135   604.6 2467.31   624.5 2475.43     652 2489.35   667.8  2501.6
   717.6 2534.08   743.3 2553.18   757.6 2557.84   771.8 2571.47   826.7 2610.39
#Mann= 4 ,-1 , 0
       0     .05       0  406.69    .045       0  432.19     .06       0
  560.21      .1       0
#XS Ineff= 2 , 0
                          501.69            2467
Permanent Ineff=
       F       F
Bank Sta=406.69,432.19
XS Rating Curve= 0 ,0
Exp/Cntr(USF)=0,0
Exp/Cntr=0.5,0.3

Type RM Length L Ch R = 1 ,33116   ,255.6,256.8,257.2
XS GIS Cut Line= 2
2414023.47507851595119.524373258 2414523.4750785 594461.19103993
#Sta/Elev= 30
       0 2528.93    56.4 2519.92    71.6 2513.93   136.3 2484.83   167.7 2477.47
   227.3 2472.69   307.6  2471.8   314.1 2470.02   337.8 2459.92   386.8  2460.4
  400.092454.073   413.2 2453.16  423.092453.929     436 2458.34   459.6 2460.75
   513.1 2461.26   533.6 2458.37  545.972458.951   604.4 2464.72   611.7 2467.29
   638.7 2480.34     658 2491.02   690.1 2511.65   704.2 2522.47   715.8 2529.55
   754.6 2560.31   764.3 2561.79   767.1 2563.26   778.5  2573.6   826.7 2609.15
#Mann= 4 ,-1 , 0
       0     .05       0  400.09    .045       0  423.09     .06       0
  545.97      .1       0
#XS Ineff= 2 , 0
          384.44 2461.24  467.87         2463.04
Permanent Ineff=
       F       F
Bank Sta=400.09,423.09
XS Rating Curve= 0 ,0
Exp/Cntr(USF)=0,0
Exp/Cntr=0.5,0.3

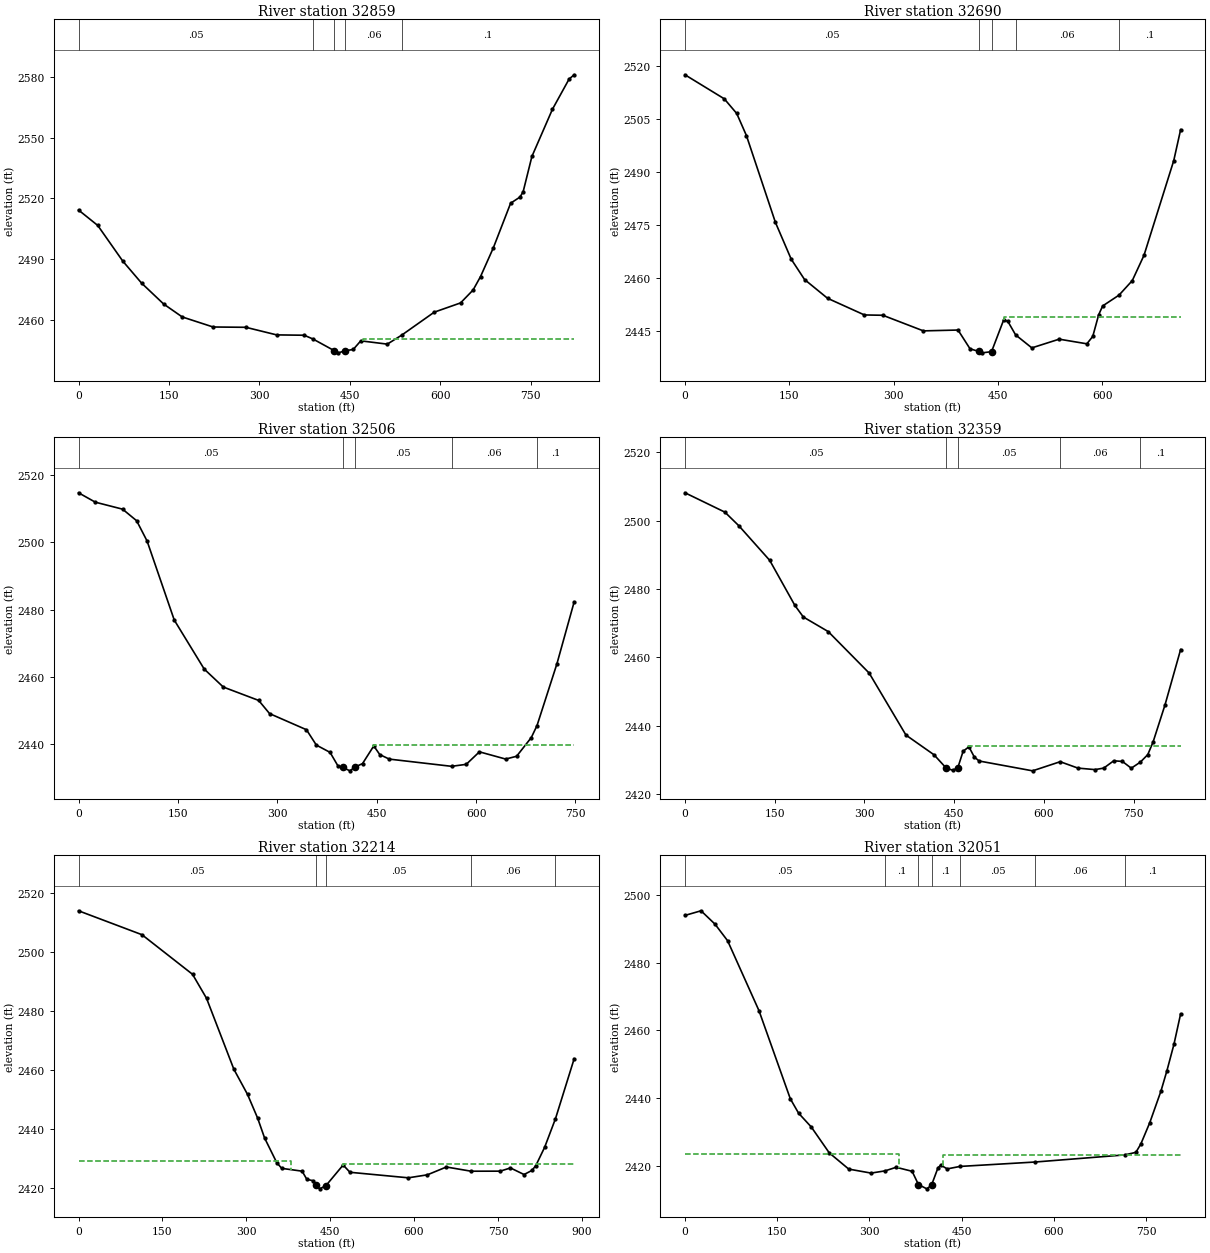
Type RM Length L Ch R = 1 ,32859   ,161.5,168.6,175.2
XS GIS Cut Line= 2
2414187.34345853595295.1061609692414710.78445853594661.256160969
#Sta/Elev= 30
       0 2514.28    31.9 2506.68    73.4 2489.12   104.5  2478.3   141.1    2468
     172 2461.61   223.2 2456.66   277.5 2456.51   328.6 2452.77   374.3  2452.6
  389.082450.709  424.222444.984   430.9 2443.93  442.322444.962   455.6 2445.59
   468.1 2449.84   512.1 2448.22  535.932452.637     590 2463.97   633.6 2468.52
   654.4 2474.89   666.7 2481.49     688 2495.69   716.6 2517.62   732.2 2520.68
   737.4 2523.31   751.9 2540.66     786 2563.93   813.6  2578.8     822  2580.9
#Mann= 5 ,-1 , 0
       0     .05       0  389.08     .06       0  424.22    .045       0
  442.32     .06       0  535.93      .1       0
#XS Ineff= 2 , 0
                          472.42         2450.56
Permanent Ineff=
       F       F
Bank Sta=424.22,442.32
XS Rating Curve= 0 ,0
Exp/Cntr(USF)=0,0
Exp/Cntr=0.3,0.1

Type RM Length L Ch R = 1 ,32690   ,184,184,182.2
XS GIS Cut Line= 4
2414226.83413414595351.3468902352414494.63594634 595118.39829511
2414594.12863508595077.5881536192414755.41394634594886.562834126
#Sta/Elev= 30
       0 2517.38    56.5 2510.59    74.4 2506.45    88.3 2500.23     130  2475.7
   152.7 2465.31   171.9 2459.56   204.9 2454.27   257.9 2449.56   284.4 2449.47
   342.7 2445.06   392.5  2445.3   409.8 2439.99  422.792439.241   427.1 2438.86
  440.672439.187   458.1 2448.15   464.1 2447.75  475.282443.928   498.6 2440.26
   537.9 2442.72   577.7 2441.41   586.2  2443.5   594.7 2449.62   600.4  2452.1
  623.962455.161     643 2459.26   659.8 2466.38   702.6 2493.14   712.5 2501.89
#Mann= 5 ,-1 , 0
       0     .05       0  422.79    .045       0  440.67     .05       0
  475.28     .06       0  623.96      .1       0
#XS Ineff= 2 , 0
                          459.08            2449
Permanent Ineff=
       F       F
Bank Sta=422.79,440.67
XS Rating Curve= 0 ,0
Exp/Cntr(USF)=0,0
Exp/Cntr=0.3,0.1

Type RM Length L Ch R = 1 ,32506   ,146.7,147.7,146.5
XS GIS Cut Line= 4
2414228.71886586595375.1423536712414535.93543416595303.085404875
2414663.44214727 595240.474907262414854.57930001595021.794163422
#Sta/Elev= 30
       0 2514.72    25.4 2511.92    66.5 2509.85    87.7 2506.41   103.5 2500.37
   144.5 2476.88   189.7 2462.31   218.5 2456.97   271.9 2452.99   288.3 2449.08
     344 2444.28   358.9 2439.72   379.6 2437.55   391.8 2433.43  398.622433.068
   409.7 2432.06  416.722433.144   428.6 2434.21   445.6 2439.47   454.6  2436.9
   468.9 2435.55  562.972433.404   585.1 2433.99     605 2437.71   644.6 2435.56
   661.1 2436.39   683.3 2441.95  691.94 2445.52   721.9 2463.83     748 2482.29
#Mann= 5 ,-1 , 0
       0     .05       0  398.62    .045       0  416.72     .05       0
  562.97     .06       0  691.94      .1       0
#XS Ineff= 2 , 0
                          444.64          2439.6
Permanent Ineff=
       F       F
Bank Sta=398.62,416.72
XS Rating Curve= 0 ,0
Exp/Cntr(USF)=0,0
Exp/Cntr=0.3,0.1

Type RM Length L Ch R = 1 ,32359   ,149.2,144.7,138.5
XS GIS Cut Line= 4
2414449.36467316595751.4058341262414660.82521708595404.075675609
2414854.05430579595306.3227438382414982.08686586      595146.119
#Sta/Elev= 30
       0 2508.19    66.7 2502.52    90.1 2498.52   141.6  2488.4   183.7 2475.19
   197.8 2471.81   239.4 2467.54   307.8 2455.39   369.3 2437.23   416.2 2431.46
  436.682427.542   447.6 2426.93  455.882427.636   464.8 2432.49   474.5  2433.8
   483.5 2430.81   491.6 2429.64   580.9 2426.76  627.032429.434   656.7 2427.56
   685.2 2427.12   699.8 2427.56   716.5  2429.7     731 2429.52   745.8 2427.53
  761.012429.317   773.4 2431.51   782.3 2435.23   802.2 2446.08   828.3 2462.29
#Mann= 5 ,-1 , 0
       0     .05       0  436.68    .045       0  455.88     .05       0
  627.03     .06       0  761.01      .1       0
#XS Ineff= 2 , 0
                          473.51            2434
Permanent Ineff=
       F       F
Bank Sta=436.68,455.88
XS Rating Curve= 0 ,0
Exp/Cntr(USF)=0,0
Exp/Cntr=0.3,0.1

Type RM Length L Ch R = 1 ,32214   ,165.1,162.8,159.5
XS GIS Cut Line= 2
2414463.48510977595844.5022707342415043.94229756595174.775324391
#Sta/Elev= 30
       0 2513.85   113.4 2505.76   203.9 2492.36   228.9 2484.25   277.8 2460.24
   302.2 2451.74   320.3 2443.71   332.7    2437   354.4 2428.68   363.3 2426.72
   399.8 2425.77   408.3    2423   419.6 2422.53  424.282421.027   431.4 2419.79
  442.582420.911   473.2 2427.85   485.4 2425.39   589.8 2423.52   623.8 2424.53
   657.8 2427.18  701.962425.753   754.1 2425.77   772.4 2426.86   796.7 2424.63
   810.9 2426.03   817.8 2427.68   833.5 2433.84   852.9 2443.53   886.3  2463.8
#Mann= 5 ,-1 , 0
       0     .05       0  424.28    .045       0  442.58     .05       0
  701.96     .06       0   852.9      .1       0
#XS Ineff= 2 , 0
          379.34  2429.1  472.38         2428.08
Permanent Ineff=
       F       F
Bank Sta=424.28,442.58
XS Rating Curve= 0 ,0
Exp/Cntr(USF)=0,0
Exp/Cntr=0.3,0.1

Type RM Length L Ch R = 1 ,32051   ,161.7,158.3,154.5
XS GIS Cut Line= 2
2414716.78943416 595905.46619025     2415095.858      595194.288
#Sta/Elev= 30
       0 2494.04    26.1 2495.41    48.8 2491.46    69.3 2486.55   120.3 2465.87
   171.3 2439.77   184.7 2435.53   205.4 2431.43   234.6 2423.78   266.3 2418.98
   302.6  2417.8  325.232418.453   343.4 2419.52   369.3 2418.33   379.6 2414.41
   393.2 2413.14   400.9 2414.25   411.3 2419.33   415.9 2420.16   426.4 2419.04
  447.182419.771  569.122421.073  714.852423.177   733.1 2423.93   741.1 2426.37
   755.8 2432.75   773.9 2442.06   783.6 2448.08     795 2455.88   805.9 2464.92
#Mann= 7 ,-1 , 0
       0     .05       0  325.23      .1       0   379.6    .045       0
   400.9      .1       0  447.18     .05       0  569.12     .06       0
  714.85      .1       0
#XS Ineff= 2 , 0
          348.27 2423.44  418.87         2423.19
Permanent Ineff=
       F       F
Bank Sta=379.6,400.9
XS Rating Curve= 0 ,0
Exp/Cntr(USF)=0,0
Exp/Cntr=0.3,0.1

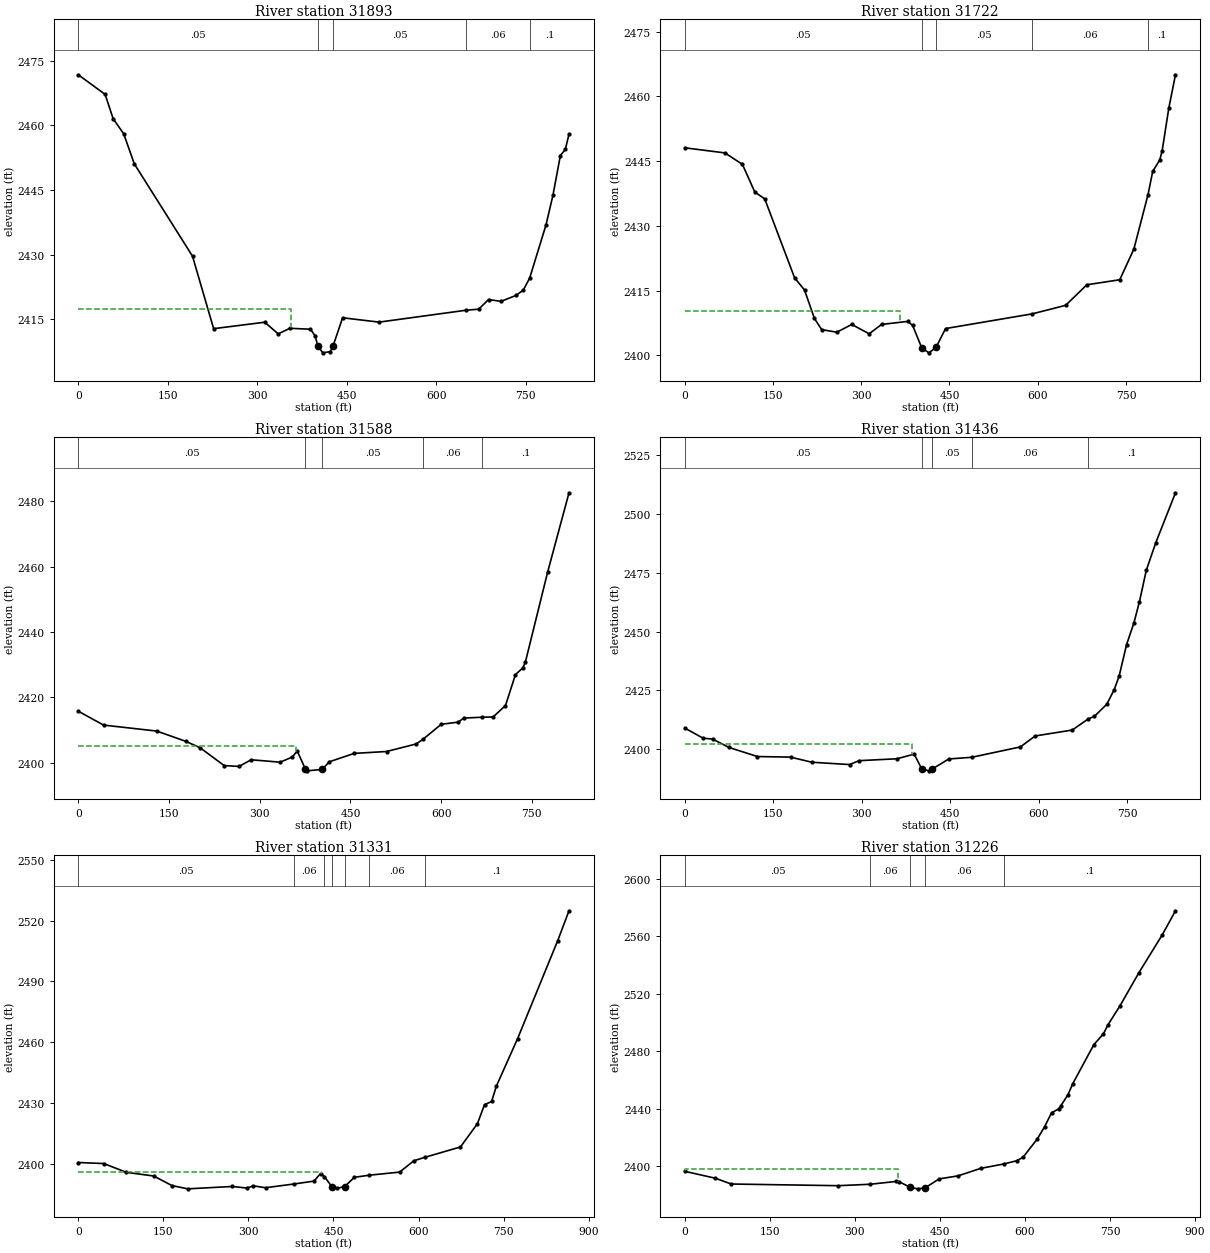
Type RM Length L Ch R = 1 ,31893   ,175.2,170.6,165
XS GIS Cut Line= 3
     2414890.872      595991.1312415019.70191952595722.061943891
     2415158.714      595216.589
#Sta/Elev= 30
       0 2471.77    45.1 2467.21    58.4 2461.59    76.2 2458.06    93.9  2451.1
   191.5 2429.66   226.9 2412.83   312.6 2414.33   335.1 2411.62   354.7 2412.92
   389.2  2412.7     397 2411.17  401.582408.821   409.9 2407.22   422.4  2407.5
  426.982408.771   443.1 2415.36   504.3 2414.35  649.672417.103   671.2 2417.36
   687.8  2419.6   708.6 2419.16   733.5 2420.54   745.9 2421.77  756.612424.552
   784.1 2436.94   795.7 2443.81   808.1 2453.02   816.4 2454.43   822.6 2457.98
#Mann= 5 ,-1 , 0
       0     .05       0  401.58    .045       0  426.98     .05       0
  649.67     .06       0  756.61      .1       0
#XS Ineff= 2 , 0
          355.97 2417.42
Permanent Ineff=
       F       F
Bank Sta=401.58,426.98
XS Rating Curve= 0 ,0
Exp/Cntr(USF)=0,0
Exp/Cntr=0.3,0.1

Type RM Length L Ch R = 1 ,31722   ,138.1,134,131.3
XS GIS Cut Line= 3
2415102.47667806596039.1409731722415215.18505366595708.934836578
     2415201.664      595223.879
#Sta/Elev= 30
       0 2448.09    68.4  2446.9      98 2444.26   119.1 2437.84     136 2436.24
   186.7 2417.97   203.6 2415.13   220.5 2408.53   232.8 2405.95   258.6 2405.35
   283.9 2407.15   313.5 2404.99   334.6 2407.15   379.4 2407.86   387.4 2406.91
  403.082401.677   415.1 2400.57  427.082401.815   443.4  2406.2  590.812409.605
   647.5 2411.58   683.5 2416.34   739.5 2417.51   763.5 2424.63  787.432437.175
   795.5 2442.61   807.5 2445.29   811.5 2447.34   822.9 2457.32   834.2 2465.01
#Mann= 5 ,-1 , 0
       0     .05       0  403.08    .045       0  427.08     .05       0
  590.81     .06       0  787.43      .1       0
#XS Ineff= 2 , 0
          365.28 2410.36
Permanent Ineff=
       F       F
Bank Sta=403.08,427.08
XS Rating Curve= 0 ,0
Exp/Cntr(USF)=0,0
Exp/Cntr=0.3,0.1

Type RM Length L Ch R = 1 ,31588   ,151.2,152.6,150.1
XS GIS Cut Line= 3
 2415359.5735683596016.1826487812415355.45070244595665.127458531
     2415254.739      595216.017
#Sta/Elev= 30
       0 2415.73    41.8 2411.48   129.8 2409.64   177.6 2406.51   201.6 2404.51
   241.2 2399.07   265.8 2398.81   285.8 2400.85   333.8 2400.11   353.8 2401.68
     362 2403.55  375.222398.106   378.4 2397.46  403.022397.894   415.3 2400.25
   456.3 2402.81   509.6 2403.38   558.8  2405.7  569.782407.112   600.1 2411.72
   628.4 2412.39   637.1 2413.62  667.522413.879   685.8 2413.97   706.3 2417.46
   722.7 2426.91     735 2429.03   739.1 2430.72     776 2458.36   811.3 2482.64
#Mann= 5 ,-1 , 0
       0     .05       0  375.22    .045       0  403.02     .05       0
  569.78     .06       0  667.52      .1       0
#XS Ineff= 2 , 0
          360.77  2405.2
Permanent Ineff=
       F       F
Bank Sta=375.22,403.02
XS Rating Curve= 0 ,0
Exp/Cntr(USF)=0,0
Exp/Cntr=0.3,0.1

Type RM Length L Ch R = 1 ,31436   ,114.3,105,95.2
XS GIS Cut Line= 3
2415489.19565123596005.5040536562415508.55605366595649.718458532
      2415368.22       595195.28
#Sta/Elev= 30
       0 2409.06    31.1 2404.77    47.2 2404.37    75.2 2400.81   123.3 2396.97
   179.3 2396.73   215.4 2394.56   279.5 2393.57   295.5 2395.22   359.7 2396.03
     389 2397.99  401.612391.788   414.1 2390.91  419.112391.622   447.6 2395.94
  486.662396.662     569 2401.06   594.1  2405.7   656.9 2408.21  683.792412.886
   694.6 2414.06   715.5 2419.16   728.1 2425.38   736.5  2431.2     749 2444.45
   761.6 2453.78   770.9 2462.72   782.5 2476.02   798.4 2487.58   831.9 2508.83
#Mann= 5 ,-1 , 0
       0     .05       0  401.61    .045       0  419.11     .05       0
  486.66     .06       0  683.79      .1       0
#XS Ineff= 2 , 0
          385.57  2402.4
Permanent Ineff=
       F       F
Bank Sta=401.61,419.11
XS Rating Curve= 0 ,0
Exp/Cntr(USF)=0,0
Exp/Cntr=0.5,0.3

Type RM Length L Ch R = 1 ,31331   ,106.2,104.4,102.7
XS GIS Cut Line= 4
  2415657.179961595971.4443869942415655.91865492 595604.74572744
2415540.81448825 595514.120727442415445.50198828595175.058227425
#Sta/Elev= 30
       0 2400.55      45 2400.04      85 2395.69     133 2393.89     165 2389.18
     193 2387.55   271.9 2388.72     297 2387.95     309 2389.02   330.2  2388.1
  379.852389.923   415.7 2391.37   427.2  2395.1  434.222393.562   447.1 2388.64
   456.6 2387.85   469.9 2388.67   486.8 2393.24  513.112394.284   566.8 2395.82
   591.8 2401.42  611.372403.131     674 2408.24   703.9 2419.74   716.4 2429.08
   728.9 2430.69   737.2 2438.21   774.6 2461.65   845.2 2509.94   865.4 2524.89
#Mann= 7 ,-1 , 0
       0     .05       0  379.85     .06       0  434.22     .05       0
   447.1    .045       0   469.9     .05       0  513.11     .06       0
  611.37      .1       0
#XS Ineff= 2 , 0
          427.28 2395.68   527.5            2392
Permanent Ineff=
       F       F
Bank Sta=447.1,469.9
XS Rating Curve= 0 ,0
Exp/Cntr(USF)=0,0
Exp/Cntr=0.5,0.3

Type RM Length L Ch R = 1 ,31226   ,128.4,144.4,158.2
XS GIS Cut Line= 4
2415718.98551655595912.4166092162415717.72421047595545.717949662
 2415602.6200438595455.0929496622415507.30754383595116.030449647
#Sta/Elev= 30
       0 2396.62      54  2391.8      82 2387.78   270.7 2386.62  327.042387.613
   372.3 2389.56   378.4 2389.32   397.8 2385.41   410.7 2384.43   423.7 2385.05
   448.7 2391.34   481.9 2393.44   522.1 2398.67  562.172401.673   586.1 2404.01
   596.9 2406.52     622 2419.23   634.8 2427.75   646.8 2437.25   659.3 2439.95
   663.4 2442.26   675.9 2449.89   684.2 2457.46   721.6 2484.75   738.2 2492.05
   746.5 2498.52   767.3 2511.47   801.1 2534.78   842.1 2560.96   865.4 2577.69
#Mann= 5 ,-1 , 0
       0     .05       0  327.04     .06       0   397.8    .045       0
   423.7     .06       0  562.17      .1       0
#XS Ineff= 2 , 0
          375.42  2398.5
Permanent Ineff=
       F       F
Bank Sta=397.8,423.7
XS Rating Curve= 0 ,0
Exp/Cntr(USF)=0,0
Exp/Cntr=0.5,0.3

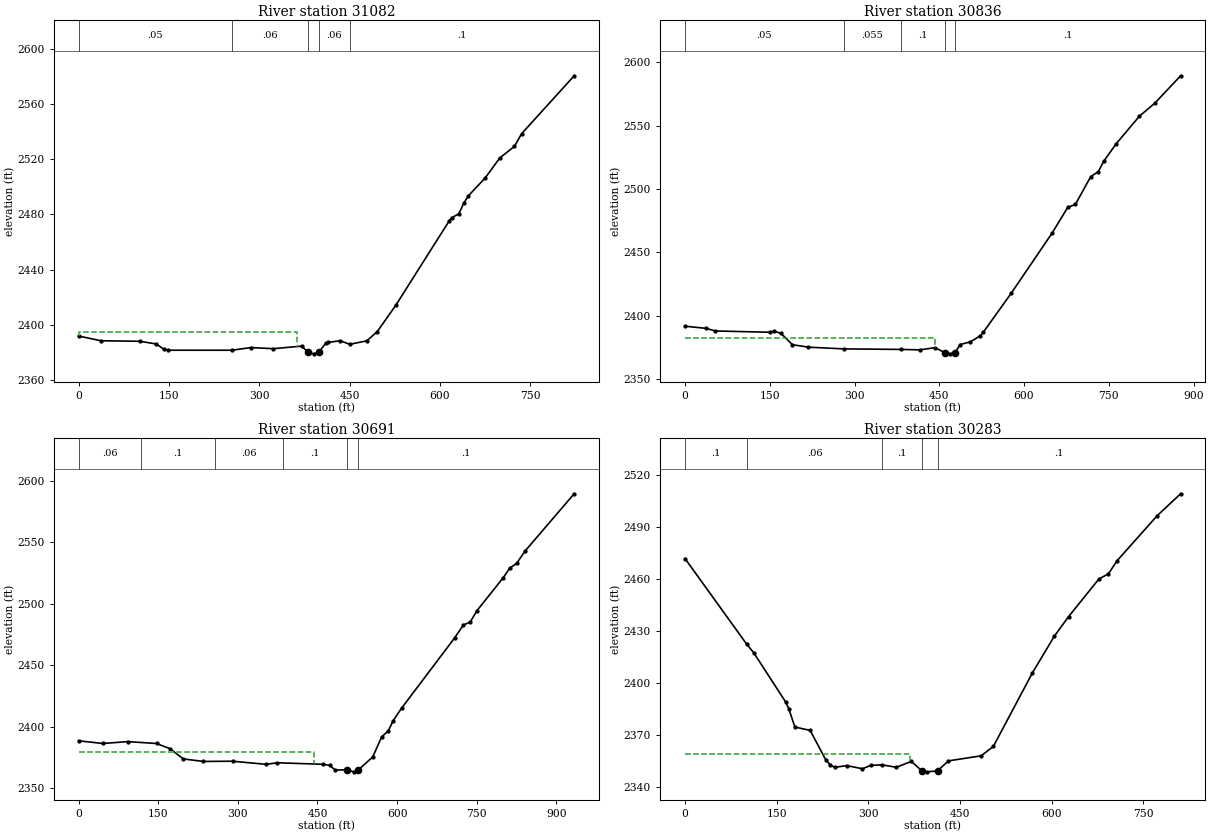
Type RM Length L Ch R = 1 ,31082   ,251.3,245.7,240.2
XS GIS Cut Line= 2
2415859.04365492595919.1554496452415787.51587712595099.711005198
#Sta/Elev= 30
       0 2391.84    36.9 2388.37     102 2387.99   129.2    2386   141.2  2382.3
   149.3 2381.51  254.542381.493   285.8 2383.42   323.6 2382.62   370.1 2384.48
  381.48 2379.93     390 2378.88  399.082380.149   410.2 2386.56   414.3 2387.13
   434.3 2388.44  450.042385.784   478.5 2388.31   495.9 2395.07   526.7 2414.18
     615 2475.15   619.1 2477.57   631.1 2480.34   639.1 2487.93   647.1 2493.52
   675.2 2506.58   699.3 2521.01   723.4  2529.3   735.4 2538.53   822.6 2580.53
#Mann= 5 ,-1 , 0
       0     .05       0  254.54     .06       0  381.48    .045       0
  399.08     .06       0  450.04      .1       0
#XS Ineff= 2 , 0
          361.89  2394.5
Permanent Ineff=
       F       F
Bank Sta=381.48,399.08
XS Rating Curve= 0 ,0
Exp/Cntr(USF)=0,0
Exp/Cntr=0.3,0.1

Type RM Length L Ch R = 1 ,30836   ,141.3,144.9,147.3
XS GIS Cut Line= 3
2416017.03173417595911.4482414542416065.30372927595487.080756094
     2415853.249      595090.137
#Sta/Elev= 30
       0 2391.68    37.3    2390    53.4 2387.93     150 2386.92     158 2387.78
   170.1 2385.97   190.2 2377.08   218.4 2375.15  280.582373.792   381.72373.364
   415.6 2373.02   442.4 2374.77  460.122370.737     469 2369.88  478.222370.874
   486.7  2377.2   504.9 2379.31   522.2 2384.02   527.6 2386.72   577.4 2417.77
     650 2465.39   677.2 2485.42   690.8 2487.78     718 2509.69   731.6 2513.76
   740.9 2521.75   763.3 2535.82   804.2 2557.43   831.4 2567.67   877.1  2589.3
#Mann= 5 ,-1 , 0
       0     .05       0  280.58    .055       0   381.7      .1       0
  460.12    .045       0  478.22      .1       0
#XS Ineff= 2 , 0
          443.07  2382.5
Permanent Ineff=
       F       F
Bank Sta=460.12,478.22
XS Rating Curve= 0 ,0
Exp/Cntr(USF)=0,0
Exp/Cntr=0.3,0.1

Type RM Length L Ch R = 1 ,30691   ,419.4,408.1,405.7
XS GIS Cut Line= 3
2416069.26068653595898.3563772652416204.62872927595488.207214625
      2416064.21      595006.897
#Sta/Elev= 30
       0 2388.74    45.8 2386.53    92.6 2388.06   146.9 2386.53   172.1 2382.35
   197.4 2373.99   235.1 2371.95   290.1 2372.15   353.3  2369.6   374.3 2370.88
   460.3 2369.65   473.2 2368.81   483.3 2364.94   504.82365.125   518.4 2363.51
   526.22364.775   554.1 2375.65   570.8  2391.9   583.3 2396.79   592.5 2405.08
   608.3 2415.21   708.7 2472.58   724.8 2482.85   737.5 2485.09     750  2494.3
     800 2521.33   811.9 2528.93     825 2532.81   840.9  2542.9   933.3 2589.36
#Mann= 6 ,-1 , 0
       0     .06       0  116.92      .1       0  257.63     .06       0
  384.92      .1       0   504.8    .045       0   526.2      .1       0
#XS Ineff= 2 , 0
          444.19    2380
Permanent Ineff=
       F       F
Bank Sta=504.8,526.2
XS Rating Curve= 0 ,0
Exp/Cntr(USF)=0,0
Exp/Cntr=0.3,0.1

Type RM Length L Ch R = 1 ,30283   ,194.2,191.9,190.4
XS GIS Cut Line= 2
     2416801.181      595605.7082416310.16213659594959.990512188
#Sta/Elev= 30
       0 2472.04  101.072422.601   112.4 2417.77   164.9 2389.23   169.9 2385.39
   179.9 2374.87   204.9 2372.91   230.2  2356.1   237.9 2352.93   244.9 2351.62
   264.9 2352.61   290.5  2350.8     304 2352.75  322.852353.043   345.8 2351.65
   370.5 2355.02   387.6 2349.63     396 2349.02   413.3 2349.57   431.2 2355.34
   484.7 2358.26   504.7 2363.68   568.3 2405.89   604.6 2427.32   627.7 2438.48
   677.4 2460.24     693 2463.22   707.5 2470.89   773.1 2496.83   811.2 2509.37
#Mann= 5 ,-1 , 0
       0      .1       0  101.07     .06       0  322.85      .1       0
   387.6    .045       0   413.3      .1       0
#XS Ineff= 2 , 0
          367.53 2359.08
Permanent Ineff=
       F       F
Bank Sta=387.6,413.3
XS Rating Curve= 0 ,0
Exp/Cntr(USF)=0,0
Exp/Cntr=0.3,0.1