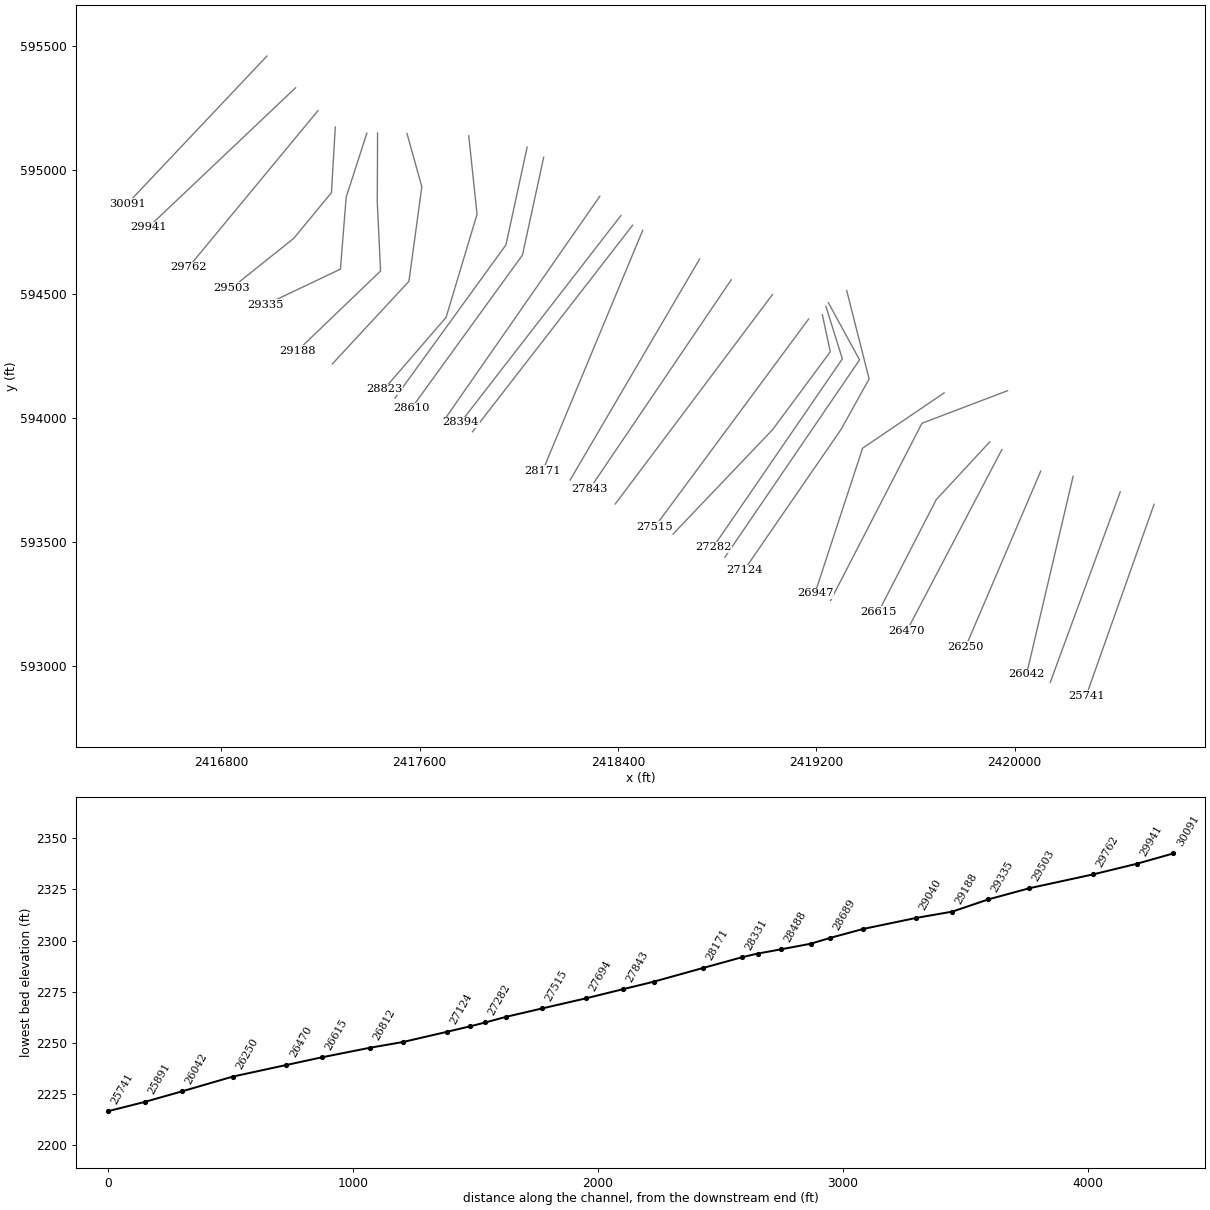
HEC-RAS study SMITHCK.prj: SMITHCK

--- SMITHCK.g01 (geometry) --- (continued)

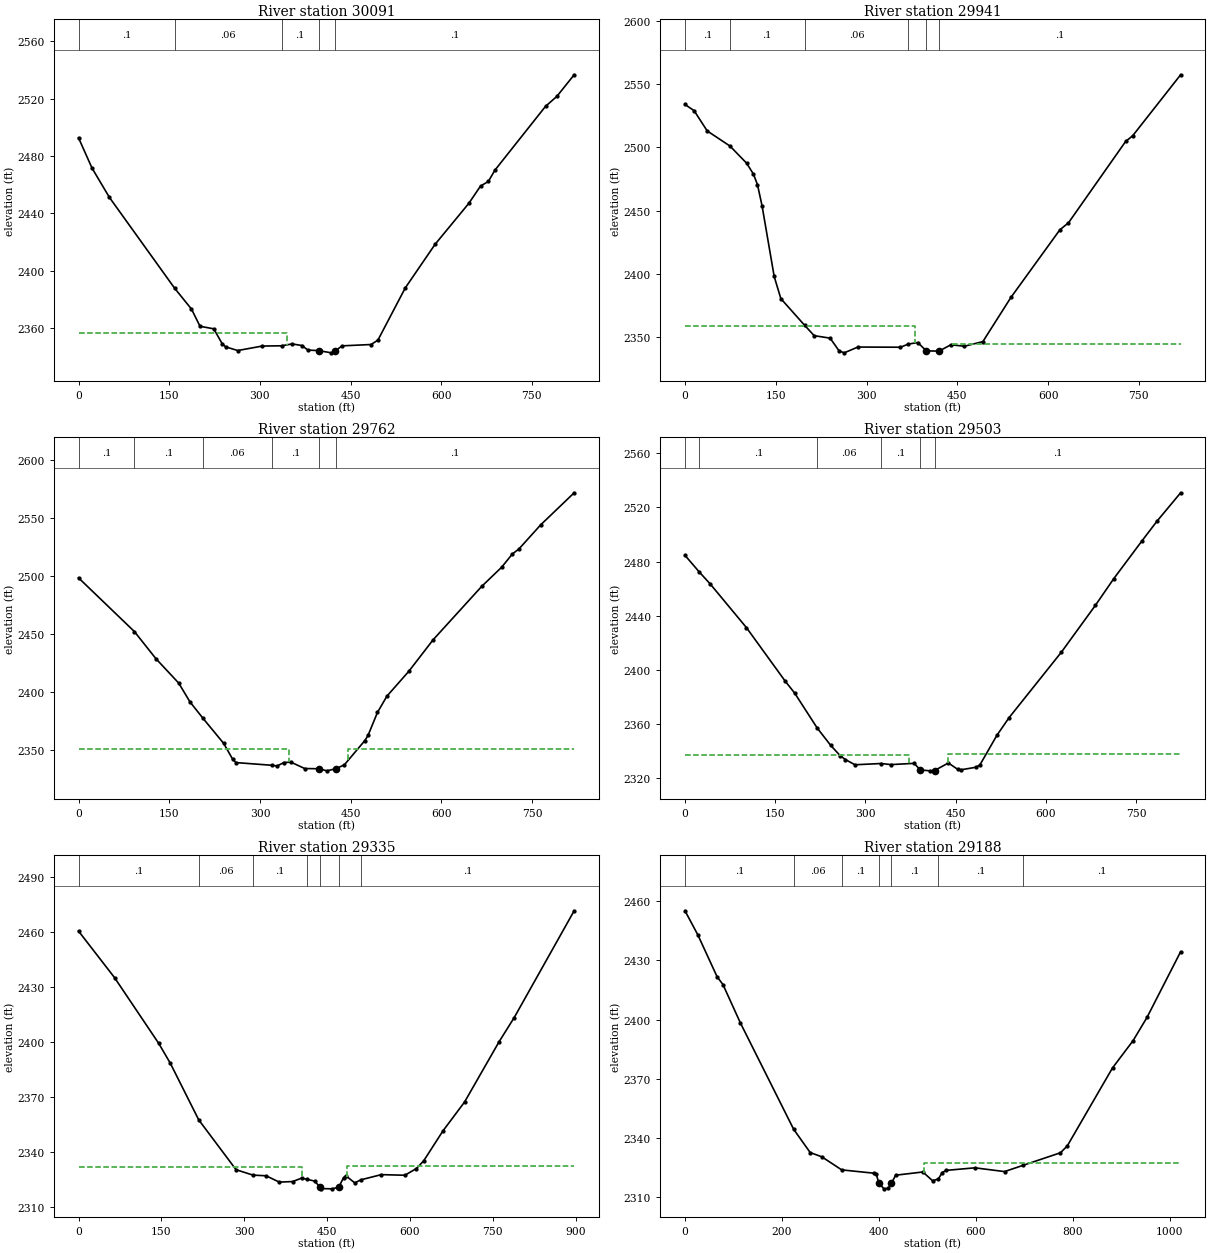
Type RM Length L Ch R = 1 ,30091   ,150.9,149.9,148.7
XS GIS Cut Line= 2
     2416984.491      595459.357     2416421.462      594863.285
#Sta/Elev= 30
       0 2492.61    22.3 2471.48    51.1 2451.01     1592387.633   186.9 2373.08
     201 2361.09   223.7 2359.33   237.8 2348.83   243.3 2346.78   263.3 2344.17
   303.8  2347.3  335.892347.488   353.3 2348.78   369.8 2347.66   379.3  2344.5
  397.322344.116   418.4 2342.57  424.22 2343.71   435.9 2347.44     484 2348.38
   495.3 2351.47   540.5 2387.85   589.9 2418.32   645.6 2446.83     665 2458.92
   677.9 2462.12   688.9 2470.06   772.5 2514.51   791.2 2521.46   819.9 2536.55
#Mann= 5 ,-1 , 0
       0      .1       0     159     .06       0  335.89      .1       0
  397.32    .045       0  424.22      .1       0
#XS Ineff= 2 , 0
          344.98  2356.5
Permanent Ineff=
       F       F
Bank Sta=397.32,424.22
XS Rating Curve= 0 ,0
Exp/Cntr(USF)=0,0
Exp/Cntr=0.3,0.1

Type RM Length L Ch R = 1 ,29941   ,177,178.8,181.4
XS GIS Cut Line= 2
     2417100.103      595331.464     2416505.696      594768.045
#Sta/Elev= 30
       0 2533.88    15.1 2528.99    36.7 2512.99   74.382500.998   101.8 2487.49
   113.1 2478.87   119.8 2470.43   127.3 2453.95   147.4 2397.88   158.4 2380.38
  197.652359.305   213.5 2351.08   239.8 2349.12   254.6  2339.1   263.1  2337.5
   285.7 2342.08   356.1 2341.94  369.222344.447   384.7 2345.64   398.9 2339.01
     420  2338.9   439.4  2343.9   461.5  2342.7   492.2 2346.37   538.6 2381.34
   619.5 2434.81   633.7 2440.33   728.1 2504.64   739.8 2509.17     819 2557.37
#Mann= 6 ,-1 , 0
       0      .1       0   74.38      .1       0  197.65     .06       0
  369.22      .1       0   398.9    .045       0     420      .1       0
#XS Ineff= 2 , 0
          379.93  2358.8  442.06         2344.59
Permanent Ineff=
       F       F
Bank Sta=398.9,420
XS Rating Curve= 0 ,0
Exp/Cntr(USF)=0,0
Exp/Cntr=0.3,0.1

Type RM Length L Ch R = 1 ,29762   ,259.4,259.8,260
XS GIS Cut Line= 2
2417190.61772927595239.4972707342416668.69672927594607.943270734
#Sta/Elev= 30
       0 2498.26   92.38 2452.07   127.9 2428.78   165.6 2407.77   184.4 2391.46
  205.852377.424     240 2355.87   254.6 2342.47   260.3  2339.4  319.332337.096
   328.2 2336.49   339.8 2339.47   351.2 2339.74   373.9 2334.29   397.9  2334.1
   410.4  2332.3   425.1 2334.08   439.3  2337.4   473.4 2358.38   478.6 2362.78
   494.2 2382.59   509.8 2396.53   546.1 2417.96   586.2 2445.03   666.5 2490.94
   699.3 2507.31   717.3 2518.87   727.7 2522.92     764 2543.84   819.3  2571.4
#Mann= 6 ,-1 , 0
       0      .1       0   92.38      .1       0  205.85     .06       0
  319.33      .1       0   397.9    .045       0   425.1      .1       0
#XS Ineff= 2 , 0
          347.24    2351  445.55         2351.06
Permanent Ineff=
       F       F
Bank Sta=397.9,425.1
XS Rating Curve= 0 ,0
Exp/Cntr(USF)=0,0
Exp/Cntr=0.3,0.1

Type RM Length L Ch R = 1 ,29503   ,159.5,167.5,185
XS GIS Cut Line= 4
2417260.31343416595172.5173512192417244.72453902 594908.22429511
2417092.88074945594724.0892414612416842.38119025594523.714458531
#Sta/Elev= 30
       0 2484.65   24.032472.231    42.1 2463.45   102.2  2431.3   166.3 2391.98
   182.3 2383.01  219.982357.083   242.4 2344.31     258 2336.77   266.9 2333.84
   282.7 2330.03  326.322330.966   342.4 2330.16     381 2331.08   391.4 2326.21
   407.7 2325.55     415 2325.78     438 2331.35   453.2 2326.74   458.8 2326.31
   484.2 2328.22   490.4  2329.9   518.7 2351.79   538.9  2364.8     626 2413.23
   682.4  2447.7   713.1  2467.5   759.2 2494.91   784.8 2509.83   824.2 2530.84
#Mann= 6 ,-1 , 0
       0      .1       0   24.03      .1       0  219.98     .06       0
  326.32      .1       0   391.4    .045       0     415      .1       0
#XS Ineff= 2 , 0
          373.17  2337.5  437.58         2337.86
Permanent Ineff=
       F       F
Bank Sta=391.4,415
XS Rating Curve= 0 ,0
Exp/Cntr(USF)=0,0
Exp/Cntr=0.3,0.1

Type RM Length L Ch R = 1 ,29335   ,145.7,147,152.6
XS GIS Cut Line= 4
     2417387.673      595148.5512417304.28696162594890.441670711
2417281.00032439594599.7460292812416979.09751955594456.314699985
#Sta/Elev= 30
       0 2460.75    65.2 2435.33   145.1 2399.49   166.1 2388.65  217.572357.733
   285.2 2330.52  315.892327.575   339.4 2327.22   363.4 2323.77   387.5 2324.06
   403.6 2325.91  413.692325.278   427.6  2324.3  436.512321.177   439.7 2320.22
   459.6 2320.09  471.012321.062   479.8 2326.19   483.8 2327.22   499.9 2323.37
  511.492325.039     548 2327.84   590.7 2327.51   611.5 2331.16   624.7 2335.35
   659.7 2351.75   698.8  2367.5   761.3  2400.4   788.6 2413.55   897.1 2471.81
#Mann= 7 ,-1 , 0
       0      .1       0  217.57     .06       0  315.89      .1       0
  413.69      .1       0  436.51    .045       0  471.01      .1       0
  511.49      .1       0
#XS Ineff= 2 , 0
          404.74 2331.84  485.91          2332.8
Permanent Ineff=
       F       F
Bank Sta=436.51,471.01
XS Rating Curve= 0 ,0
Exp/Cntr(USF)=0,0
Exp/Cntr=0.3,0.1

Type RM Length L Ch R = 1 ,29188   ,151.4,148.6,145.1
XS GIS Cut Line= 4
     2417430.848      595148.7682417429.54432439594871.273348766
  2417442.913986594592.393568304 2417107.1567098 594269.97851464
#Sta/Elev= 30
       0 2455.14    26.3 2443.03    66.3 2421.65    78.3 2417.74   114.2  2398.3
  224.192344.299   258.2 2332.54   282.2 2330.36  323.252323.731   390.3 2322.04
   394.4 2321.59     400 2316.98   410.4 2314.12   419.2 2314.43   425.9 2316.98
   434.4 2321.03   490.5 2322.67   510.5 2318.26  522.362319.069   530.5 2322.36
   538.5 2323.48     598 2324.78     659 2322.87  697.512326.061   774.3 2332.41
   788.4 2335.87   881.7 2375.44   924.2  2389.3   952.9 2401.08  1022.2 2434.38
#Mann= 7 ,-1 , 0
       0      .1       0  224.19     .06       0  323.25      .1       0
     400    .045       0   425.9      .1       0  522.36      .1       0
  697.51      .1       0
#XS Ineff= 2 , 0
                          493.79         2327.15
Permanent Ineff=
       F       F
Bank Sta=400,425.9
XS Rating Curve= 0 ,0
Exp/Cntr(USF)=0,0
Exp/Cntr=0.3,0.1

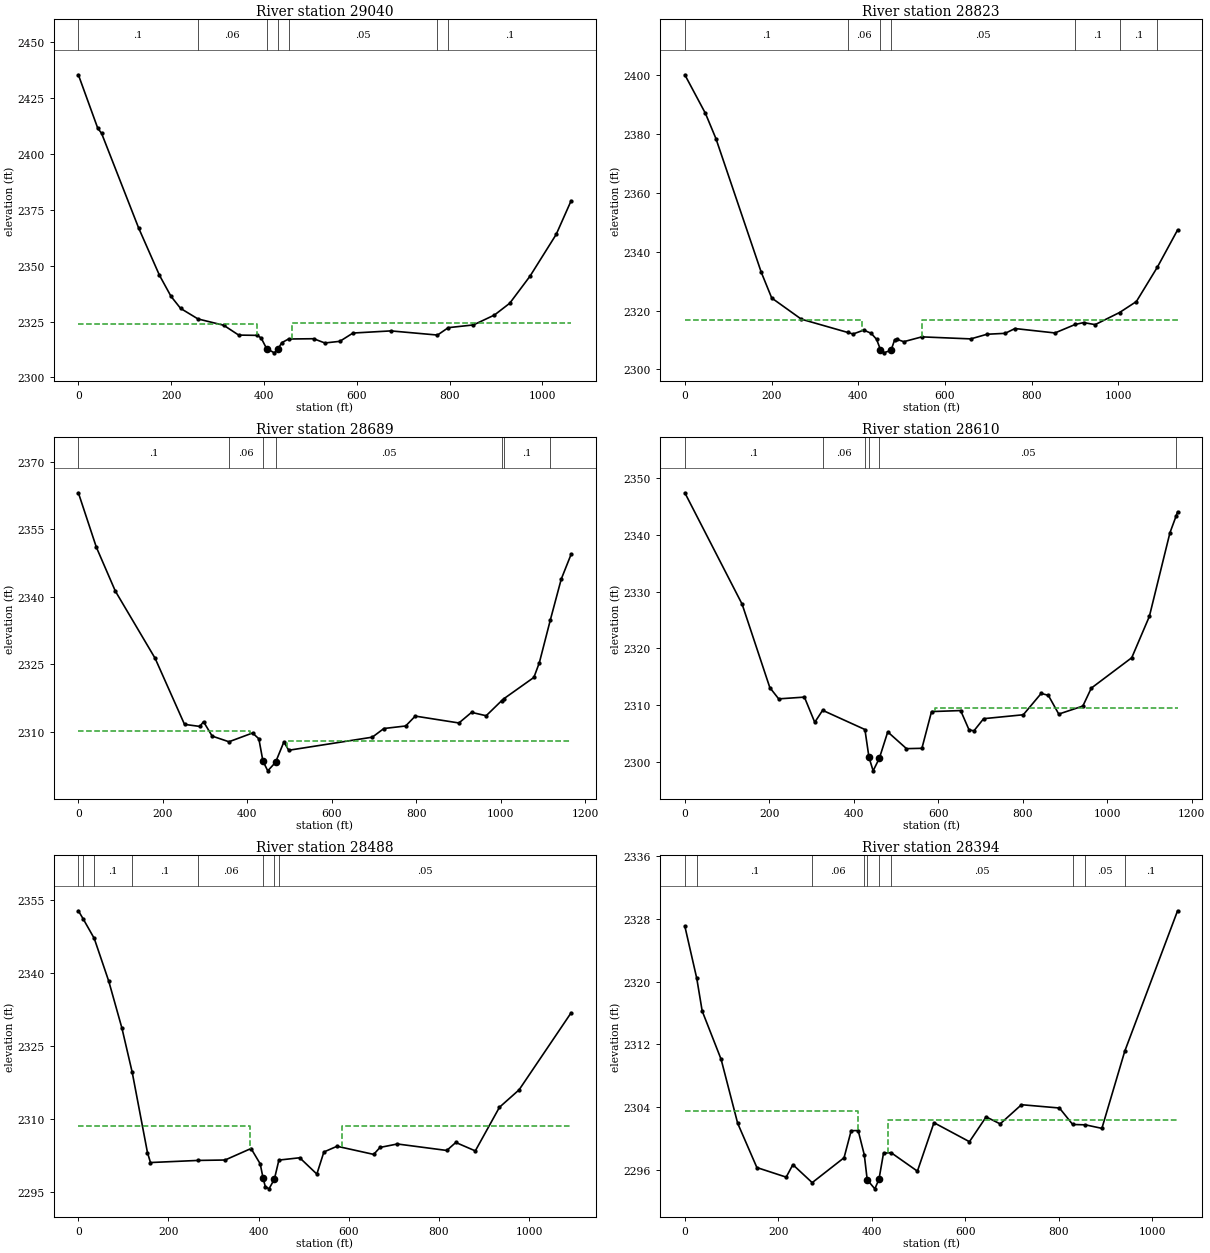
Type RM Length L Ch R = 1 ,29040   ,218.4,216.4,213.1
XS GIS Cut Line= 4
2417549.49575855595146.7976756092417609.26641525594932.029778024
2417557.28128111594550.8054609912417248.62262686  594217.5673805
#Sta/Elev= 30
       0 2435.35    41.8 2411.44    50.1 2409.14   129.8 2366.89   174.7 2345.73
   199.6  2336.3   220.3 2330.89  257.85 2326.17   313.2 2323.35   345.5 2318.96
   385.9 2318.83     394 2317.62   405.6 2312.95   422.2 2311.02   430.1 2312.73
   438.4 2315.56  452.952317.205     507 2317.33   531.2 2315.43   563.5 2316.17
   591.8 2319.87   673.4 2320.83  773.952318.971  797.212322.277   851.4  2323.5
   896.7 2327.93   929.6 2333.19   973.3 2345.29  1029.7 2363.96  1061.9 2379.01
#Mann= 7 ,-1 , 0
       0      .1       0  257.85     .06       0   405.6    .045       0
   430.1     .06       0  452.95     .05       0  773.95      .1       0
  797.21      .1       0
#XS Ineff= 2 , 0
          385.57 2324.08  459.98         2324.36
Permanent Ineff=
       F       F
Bank Sta=405.6,430.1
XS Rating Curve= 0 ,0
Exp/Cntr(USF)=0,0
Exp/Cntr=0.3,0.1

Type RM Length L Ch R = 1 ,28823   ,139.4,134,125.7
XS GIS Cut Line= 4
 2417798.5262477595137.8076896962417831.84265805594821.115065298
2417707.07833611594405.2339921712417456.30297942594114.679072649
#Sta/Elev= 30
       0 2400.15    47.6    2387    71.7 2378.46   176.2 2333.03   200.4 2324.26
   268.7 2317.06     3762312.538   387.9 2312.02   412.7 2313.35   429.7 2312.26
   442.2 2310.23  451.222306.684   458.9 2305.62  475.622306.499     484 2310.09
   488.2 2310.27   504.9 2309.41   546.6 2311.05   659.4 2310.36   696.9 2311.94
   738.7 2312.25   761.4 2313.88   853.6 2312.38  900.422315.275   919.9  2315.9
   946.3 2315.21 1002.642319.333  1041.4 2323.06 1090.03 2334.81  1136.4 2347.39
#Mann= 7 ,-1 , 0
       0      .1       0     376     .06       0  451.22    .045       0
  475.62     .05       0  900.42      .1       0 1002.64      .1       0
 1090.03      .1       0
#XS Ineff= 2 , 0
          408.57  2316.8  547.91          2316.8
Permanent Ineff=
       F       F
Bank Sta=451.22,475.62
XS Rating Curve= 0 ,0
Exp/Cntr(USF)=0,0
Exp/Cntr=0.5,0.3

Type RM Length L Ch R = 1 ,28689   ,78.8,79,79.5
XS GIS Cut Line= 3
2418033.95173552595092.1665262752417948.46486721594697.702311649
2417501.02460138594079.657965336
#Sta/Elev= 30
       0 2363.14    42.6 2351.02    87.6 2341.25   181.8 2326.29   251.3 2311.61
   287.6 2311.15   296.3  2312.2   316.8    2309  356.522307.739   412.4 2309.69
   427.3  2308.4  437.012303.426   448.4 2301.27  466.812303.164   486.5 2307.68
   498.1 2305.85   695.9 2308.76   723.4 2310.69   774.9 2311.25   797.6 2313.45
     901 2311.92   930.9 2314.28   965.5 2313.53 1002.172316.883 1007.992317.355
  1078.5 2322.06  1091.5 2325.37 1117.522334.883  1143.2 2343.92  1166.6 2349.45
#Mann= 7 ,-1 , 0
       0      .1       0  356.52     .06       0  437.01    .045       0
  466.81     .05       0 1002.17      .1       0 1007.99      .1       0
 1117.52      .1       0
#XS Ineff= 2 , 0
          407.22 2310.22     495            2308
Permanent Ineff=
       F       F
Bank Sta=437.01,466.81
XS Rating Curve= 0 ,0
Exp/Cntr(USF)=0,0
Exp/Cntr=0.5,0.3

Type RM Length L Ch R = 1 ,28610   ,122,122.4,122.7
XS GIS Cut Line= 3
2418100.61840218595051.1943040532418015.13153387594656.730089427
2417567.69126804594038.685743114
#Sta/Elev= 30
       0 2347.43   135.7 2327.79   201.2 2313.11   222.2 2311.12   283.1 2311.43
   307.6 2306.99  326.212309.105  426.37 2305.72  435.912300.846   445.8 2298.44
  460.612300.674   480.4  2305.3   524.8 2302.35   561.3 2302.41   584.1 2308.88
     653 2309.06   672.9 2305.66   684.5 2305.49   707.4 2307.63   801.3 2308.32
   843.7 2312.08   860.6 2311.74   885.3 2308.44   942.3 2309.85   962.3 2313.01
  1058.1 2318.37  1099.8 2325.65  1148.5 2340.38 1163.262343.359  1166.6 2344.08
#Mann= 6 ,-1 , 0
       0      .1       0  326.21     .06       0  426.37     .05       0
  435.91    .045       0  460.61     .05       0 1163.26      .1       0
#XS Ineff= 2 , 0
                          592.56         2309.44
Permanent Ineff=
       F       F
Bank Sta=435.91,460.61
XS Rating Curve= 0 ,0
Exp/Cntr(USF)=0,0
Exp/Cntr=0.5,0.3

Type RM Length L Ch R = 1 ,28488   ,94.8,94.1,93.5
XS GIS Cut Line= 2
2418327.01344444594893.9361111112417703.01436641 593996.03987211
#Sta/Elev= 30
       0 2352.76   11.072351.027   35.242347.081    67.5 2338.28    96.7 2328.65
  119.542319.569   153.3 2303.13     160 2301.07  265.212301.502   325.6 2301.59
   383.2 2303.95   403.5  2300.8  410.012297.806   414.8 2296.14     423 2295.67
  434.912297.645  444.982301.573   491.2 2302.05   529.2  2298.7   544.8 2303.24
     574 2304.41   655.3 2302.74   669.3 2304.17   707.9 2304.88   817.5 2303.55
   837.5 2305.19   880.8 2303.46   934.4 2312.42     978    2316  1093.4 2331.81
#Mann= 8 ,-1 , 0
       0      .1       0   11.07      .1       0   35.24      .1       0
  119.54      .1       0  265.21     .06       0  410.01    .045       0
  434.91     .06       0  444.98     .05       0
#XS Ineff= 2 , 0
          380.16 2308.62  584.44         2308.62
Permanent Ineff=
       F       F
Bank Sta=410.01,434.91
XS Rating Curve= 0 ,0
Exp/Cntr(USF)=0,0
Exp/Cntr=0.5,0.3

Type RM Length L Ch R = 1 ,28394   ,62.4,62.8,62.7
XS GIS Cut Line= 2
2418411.91077778594815.8812222222417766.46521193593982.574307612
#Sta/Elev= 30
       0 2327.06   25.532320.411    37.1 2316.26    77.6 2310.11     113 2301.97
   154.1 2296.33   216.8 2295.11   231.1  2296.7  272.432294.409   340.6 2297.58
   355.8 2301.02   370.8 2301.04  383.872297.946  390.122294.773   406.4 2293.62
  415.25 2294.83     425 2298.16  441.152298.227   497.5 2295.87   532.9 2302.04
   608.8 2299.62   644.5 2302.78   674.5 2301.89   720.1 2304.33   801.3 2303.91
   829.62301.812  856.782301.768   892.1 2301.32  941.042311.146    1054 2329.02
#Mann= 10 ,-1 , 0
       0      .1       0   25.53      .1       0  272.43     .06       0
  383.87      .1       0  390.12    .045       0  415.25      .1       0
  441.15     .05       0   829.6      .1       0  856.78     .05       0
  941.04      .1       0
#XS Ineff= 2 , 0
           369.8 2303.47  434.06         2302.41
Permanent Ineff=
       F       F
Bank Sta=390.12,415.25
XS Rating Curve= 0 ,0
Exp/Cntr(USF)=0,0
Exp/Cntr=0.5,0.3

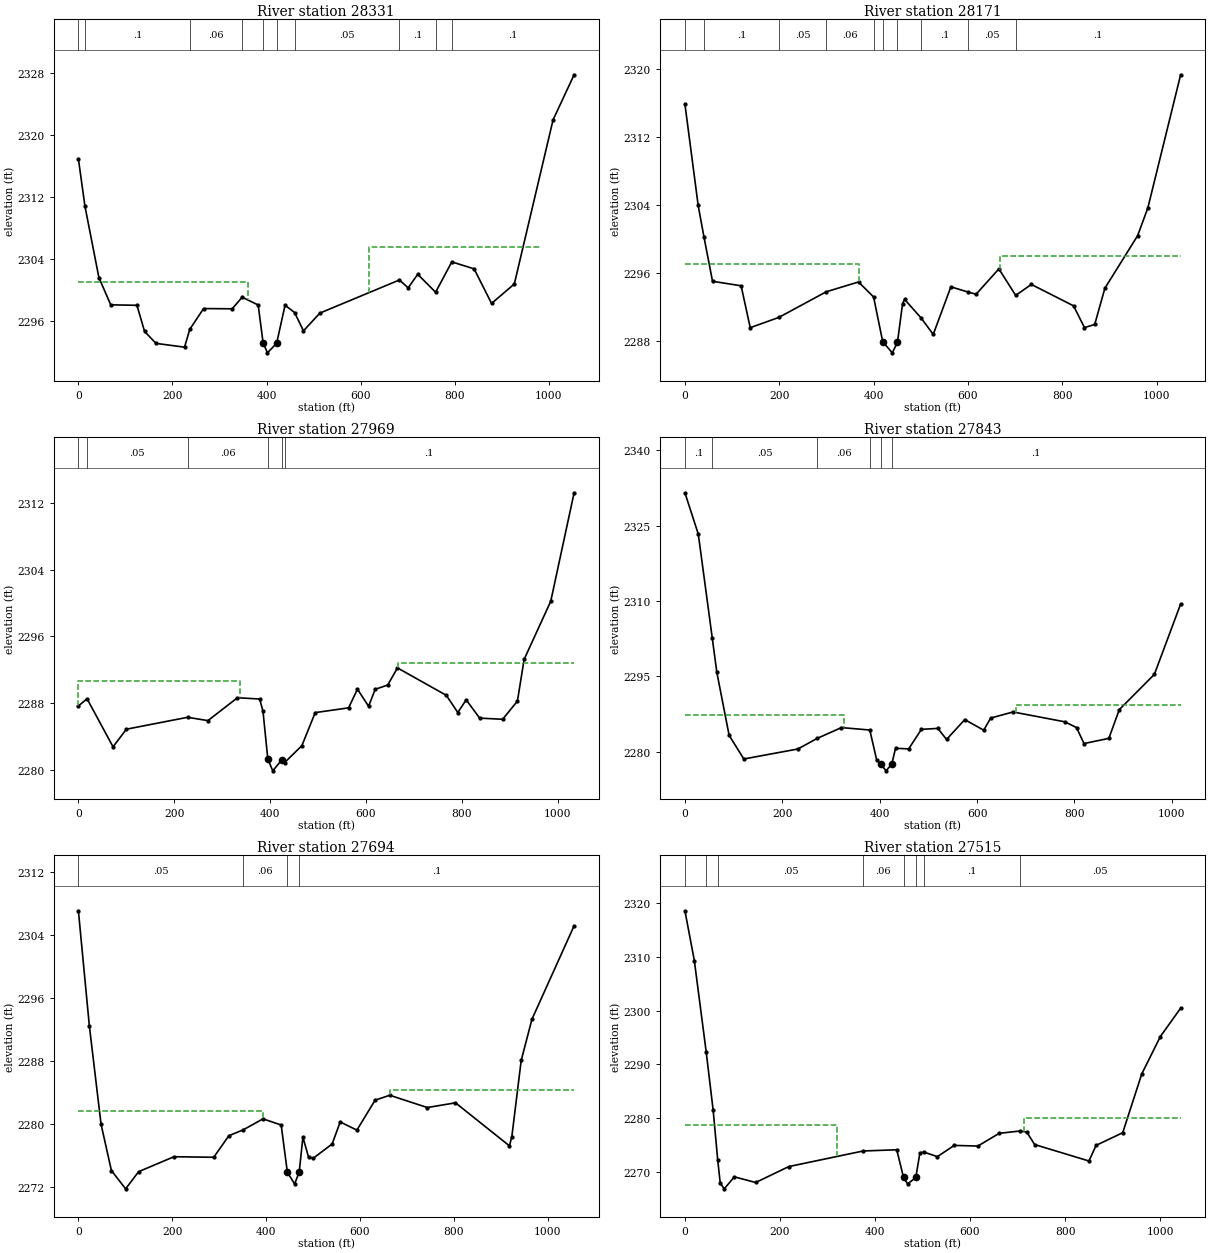
Type RM Length L Ch R = 1 ,28331   ,156.3,159.8,166.7
XS GIS Cut Line= 2
     2418459.133594776.9923333332417813.68743416593943.685418723
#Sta/Elev= 30
       0 2316.89   13.95 2310.78    43.6 2301.58    68.8 2298.06   124.5    2298
   140.7 2294.63     165 2293.09   225.7  2292.6  236.812294.899   266.2 2297.58
   326.9 2297.55  348.252299.042   382.3 2298.04  392.622293.203   401.9 2291.87
  421.522293.095   439.4 2298.01  459.682297.072   478.6 2294.71   513.6    2297
  682.552301.265   701.2 2300.25   721.5    2302  759.532299.687  793.98  2303.6
   841.4  2302.7   878.5 2298.24   926.9 2300.75  1009.3 2321.92    1054 2327.73
#Mann= 10 ,-1 , 0
       0      .1       0   13.95      .1       0  236.81     .06       0
  348.25      .1       0  392.62    .045       0  421.52      .1       0
  459.68     .05       0  682.55      .1       0  759.53     .05       0
  793.98      .1       0
#XS Ineff= 4 ,-1
       0  359.86 2300.96  449.56  617.81 2296.98  617.81  982.85 2305.48
  982.85    1054 2296.98
Permanent Ineff=
       F       F       F       F
Bank Sta=392.62,421.52
XS Rating Curve= 0 ,0
Exp/Cntr(USF)=0,0
Exp/Cntr=0.5,0.3

Type RM Length L Ch R = 1 ,28171   ,205.1,202.2,199.8
XS GIS Cut Line= 2
2418500.00777778594756.5306666672418096.60221193593786.484454494
#Sta/Elev= 30
       0 2315.87    28.1 2303.94    40.42300.224    58.5 2295.02   119.1 2294.49
   138.4 2289.56  199.022290.767  299.432293.783   367.9 2294.94  399.842293.176
  419.292287.887   439.6  2286.6  450.492287.857   461.3  2292.4   465.6 2292.89
  500.242290.725   526.3 2288.77   563.7 2294.37  600.652293.742   617.2  2293.5
   665.4 2296.48  701.052293.358   734.2 2294.65   823.7 2292.13   846.8 2289.57
   868.5 2289.94   890.1 2294.21   959.4 2300.38   981.1 2303.65  1050.6 2319.32
#Mann= 10 ,-1 , 0
       0     .05       0    40.4      .1       0  199.02     .05       0
  299.43     .06       0  399.84     .05       0  419.29    .045       0
  450.49     .05       0  500.24      .1       0  600.65     .05       0
  701.05      .1       0
#XS Ineff= 2 , 0
          369.33 2297.11  666.97         2297.95
Permanent Ineff=
       F       F
Bank Sta=419.29,450.49
XS Rating Curve= 0 ,0
Exp/Cntr(USF)=0,0
Exp/Cntr=0.3,0.1

Type RM Length L Ch R = 1 ,27969   ,127.3,125.9,124.6
XS GIS Cut Line= 2
     2418729.503       594640.942418207.05273172593748.652517093
#Sta/Elev= 30
       0 2287.64   18.072288.511    72.3 2282.75   100.1 2284.86  227.742286.287
   270.2 2285.89   331.8 2288.63   378.2 2288.48   385.1 2286.99  395.15 2281.27
   405.5 2279.87   424.5  2281.2  429.972280.848   466.2 2282.89     494 2286.85
   563.6 2287.42   582.1 2289.66   605.3 2287.61   619.2 2289.65   645.2 2290.15
   665.5 2292.21   767.5 2288.92   791.4 2286.86   808.9 2288.38     837 2286.19
   884.9 2286.05   915.8 2288.23   929.7 2293.22   985.3  2300.2    1034  2313.2
#Mann= 6 ,-1 , 0
       0      .1       0   18.07     .05       0  227.74     .06       0
  395.15    .045       0   424.5     .06       0  429.97      .1       0
#XS Ineff= 2 , 0
          336.87  2290.6  666.97         2292.84
Permanent Ineff=
       F       F
Bank Sta=395.15,424.5
XS Rating Curve= 0 ,0
Exp/Cntr(USF)=0,0
Exp/Cntr=0.3,0.1

Type RM Length L Ch R = 1 ,27843   ,149.8,149,148
XS GIS Cut Line= 2
     2418856.769      594556.8732418286.43670489593713.650246359
#Sta/Elev= 30
       0 2331.55    27.5  2323.3   56.172302.614    65.5 2295.82    90.8 2283.25
     121 2278.55     232 2280.54  271.822282.663   321.5  2284.8  379.642284.317
   393.9 2278.32   401.9 2277.55   413.2 2276.19  424.892277.577   432.5 2280.68
   459.5 2280.56   485.6 2284.45   519.4 2284.64   537.3 2282.44   574.7 2286.39
   613.6 2284.28   627.9  2286.7   673.9 2287.91   780.2 2285.95   804.3  2284.8
   819.5 2281.62   870.6 2282.66     892 2288.37   964.1  2295.4    1018  2309.4
#Mann= 6 ,-1 , 0
       0      .1       0   56.17     .05       0  271.82     .06       0
  379.64      .1       0   401.9    .045       0  424.89      .1       0
#XS Ineff= 2 , 0
           327.4 2287.36   680.5         2289.32
Permanent Ineff=
       F       F
Bank Sta=401.9,424.89
XS Rating Curve= 0 ,0
Exp/Cntr(USF)=0,0
Exp/Cntr=0.3,0.1

Type RM Length L Ch R = 1 ,27694   ,179.1,179.2,179.4
XS GIS Cut Line= 2
2419023.14640488594497.2284317032418389.43302928593652.459948796
#Sta/Elev= 30
       0 2307.12    23.3 2292.52    48.3 2279.99    70.3 2274.12   100.6 2271.79
   128.3 2273.97   203.6 2275.87   288.3  2275.8   320.6 2278.54  351.24 2279.29
   393.3 2280.68     432  2279.9  445.172273.902   460.6 2272.41  470.372273.919
   478.3 2278.36   490.2 2275.83   500.6 2275.69   540.6 2277.49   557.7 2280.29
   593.3 2279.25     632 2283.05   663.3 2283.68   743.3 2282.12   803.3 2282.72
   918.3 2277.25   923.4 2278.44   943.3  2288.1   966.2 2293.34    1056 2305.21
#Mann= 4 ,-1 , 0
       0     .05       0  351.24     .06       0  445.17    .045       0
  470.37      .1       0
#XS Ineff= 2 , 0
          393.69 2281.68  664.26         2284.32
Permanent Ineff=
       F       F
Bank Sta=445.17,470.37
XS Rating Curve= 0 ,0
Exp/Cntr(USF)=0,0
Exp/Cntr=0.3,0.1

Type RM Length L Ch R = 1 ,27515   ,148.4,147.8,144.3
XS GIS Cut Line= 2
2419168.82043948594398.315734178 2418548.4645054593559.622236706
#Sta/Elev= 30
       0 2318.58    19.8 2309.32   44.672292.394    59.4  2281.5   69.052272.205
    74.3 2267.92    82.7 2266.85   104.1 2269.08   148.9 2268.03   218.5 2270.99
  375.01 2273.89   445.8 2274.12   460.1 2268.96   468.7 2267.76   485.9 2268.96
   494.5 2273.54  502.45  2273.7   531.2 2272.84   566.8 2274.93   616.5 2274.81
   661.3 2277.17  705.342277.616   719.5 2277.41   735.9 2275.09   850.3 2272.03
   865.3 2274.94   921.3 2277.29   961.6 2288.27  1000.6 2295.19  1043.2 2300.46
#Mann= 8 ,-1 , 0
       0     .05       0   44.67      .1       0   69.05     .05       0
  375.01     .06       0   460.1    .045       0   485.9     .05       0
  502.45      .1       0  705.34     .05       0
#XS Ineff= 2 , 0
          320.63 2278.72  714.32         2280.04
Permanent Ineff=
       F       F
Bank Sta=460.1,485.9
XS Rating Curve= 0 ,0
Exp/Cntr(USF)=0,0
Exp/Cntr=0.3,0.1

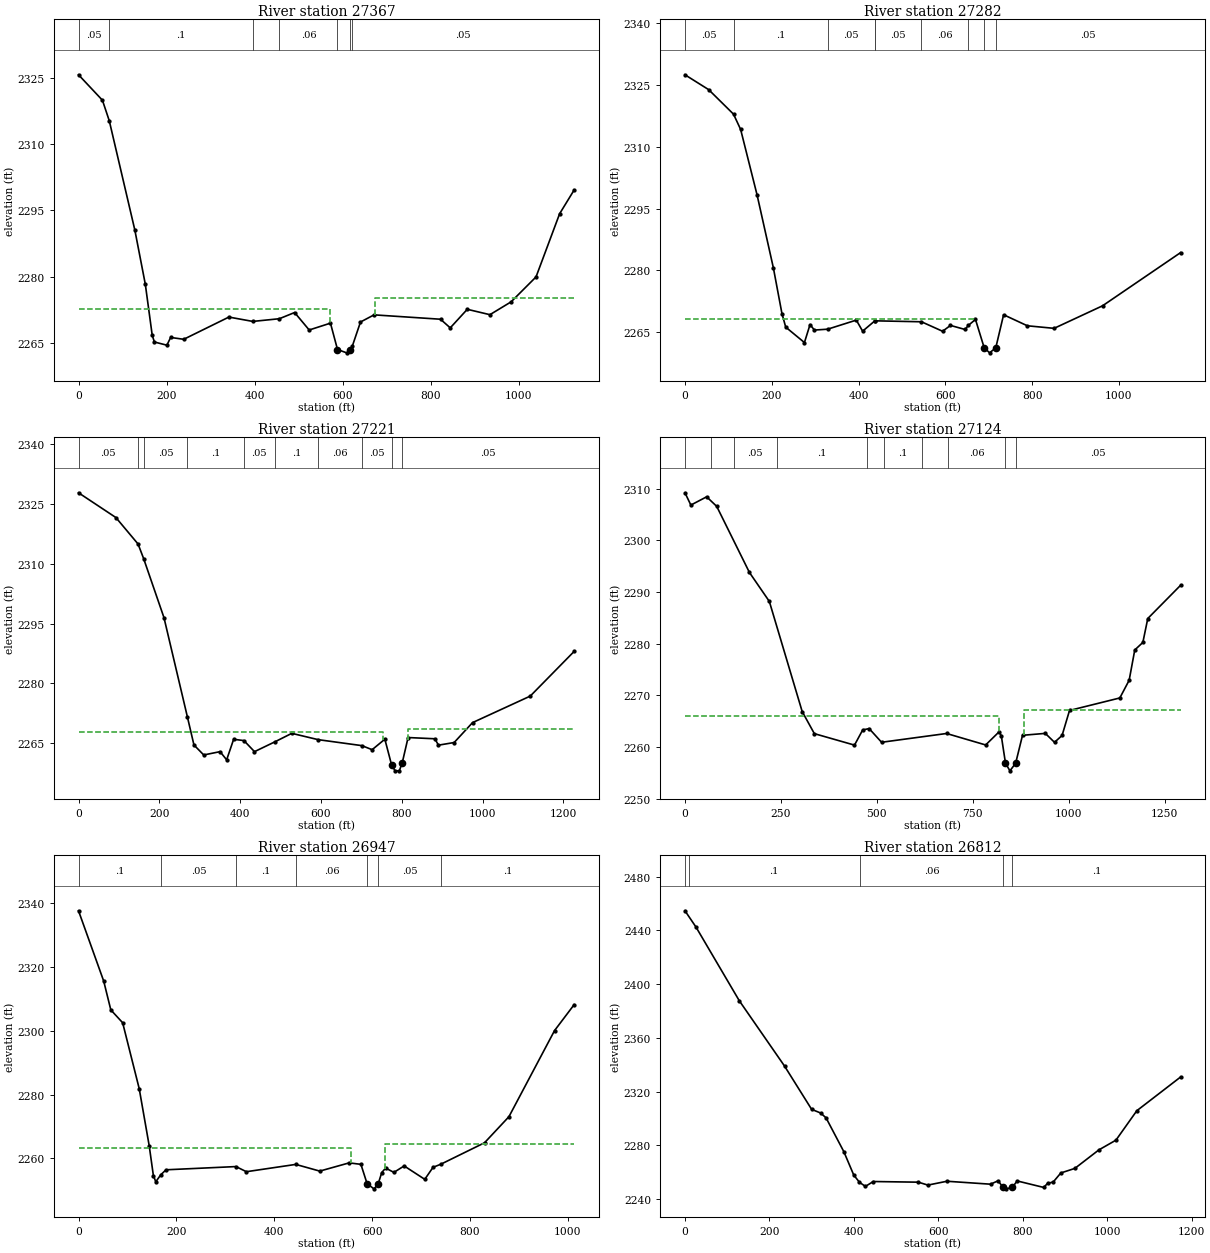
Type RM Length L Ch R = 1 ,27367   ,82.3,85,87.7
XS GIS Cut Line= 4
2419224.32143269 594415.683227422419256.29417814594266.537523597
2419024.28778131593952.8752441262418622.23809935593530.961005211
#Sta/Elev= 30
       0 2325.76    54.3 2319.99   69.862315.331   127.9 2290.56   151.7 2278.27
   167.4 2266.69   172.3 2265.18   200.7 2264.45   209.2 2266.21   238.9 2265.79
   341.5 2270.83  395.692269.843     4562270.453   490.7 2271.86   523.8  2267.9
   572.1 2269.45  588.092263.475   608.9 2262.72  617.392263.329  621.662264.212
   640.3 2269.71   671.1 2271.33     822 2270.34   844.1 2268.38   882.8 2272.59
   934.2 2271.37   982.3 2274.28  1038.9 2279.93  1092.5 2294.26  1125.5 2299.65
#Mann= 7 ,-1 , 0
       0     .05       0   69.86      .1       0  395.69     .05       0
     456     .06       0  588.09    .045       0  617.39     .06       0
  621.66     .05       0
#XS Ineff= 2 , 0
          570.91 2272.74  673.73         2275.12
Permanent Ineff=
       F       F
Bank Sta=588.09,617.39
XS Rating Curve= 0 ,0
Exp/Cntr(USF)=0,0
Exp/Cntr=0.5,0.3

Type RM Length L Ch R = 1 ,27282   ,61.5,61.2,61.5
XS GIS Cut Line= 3
2419238.90476602594449.0165607632419304.87698825594237.905449659
2418784.04365492593478.183227435
#Sta/Elev= 30
       0 2327.49    54.6 2323.88  111.912317.921   128.3 2314.21     166 2298.38
   203.7 2280.61   223.5 2269.49   232.2  2266.2   275.3 2262.46   288.2 2266.82
   298.3 2265.49  328.752265.702   394.9 2267.91   409.4 2265.22   436.92267.668
  437.792267.736  545.042267.504   593.7  2265.2   611.9 2266.62   645.5 2265.63
  653.192266.635   669.5 2268.07  689.592261.192   702.1 2259.96  716.292261.186
   734.3 2269.21   789.1 2266.53   850.7 2265.91   962.3 2271.38  1142.3 2284.31
#Mann= 9 ,-1 , 0
       0     .05       0  111.91      .1       0  328.75     .05       0
   436.9      .1       0  437.79     .05       0  545.04     .06       0
  653.19     .05       0  689.59    .045       0  716.29     .05       0
#XS Ineff= 2 , 0
          665.68 2268.29   735.8         2269.12
Permanent Ineff=
       F       F
Bank Sta=689.59,716.29
XS Rating Curve= 0 ,0
Exp/Cntr(USF)=0,0
Exp/Cntr=0.5,0.3

Type RM Length L Ch R = 1 ,27221   ,96.5,96.6,96.1
XS GIS Cut Line= 3
2419248.62698826594464.2943385242419374.32143269594233.738782972
2418831.26587714593437.211005211
#Sta/Elev= 30
       0 2327.82    92.5 2321.61  147.362314.975  161.122311.326   211.5 2296.51
  269.262271.708   285.7 2264.58   309.9 2262.08   350.3 2262.91   366.6 2260.86
   383.9 2266.01  409.372265.686   435.5 2262.91  485.29 2265.34   527.8  2267.5
  593.312265.915  701.32 2264.42   726.6  2263.4   758.1 2266.03  774.722259.614
   783.4  2258.1     794 2258.12  801.222260.149   815.6 2266.45   881.8 2266.14
   890.8 2264.54   929.6  2265.2   975.1 2270.19  1117.9 2276.84  1226.6 2288.05
#Mann= 10 ,-1 , 0
       0     .05       0  147.36      .1       0  161.12     .05       0
  269.26      .1       0  409.37     .05       0  485.29      .1       0
  593.31     .06       0  701.32     .05       0  774.72    .045       0
  801.22     .05       0
#XS Ineff= 2 , 0
          754.45 2267.76  814.43         2268.56
Permanent Ineff=
       F       F
Bank Sta=774.72,801.22
XS Rating Curve= 0 ,0
Exp/Cntr(USF)=0,0
Exp/Cntr=0.5,0.3

Type RM Length L Ch R = 1 ,27124   ,171.6,177.4,181.8
XS GIS Cut Line= 4
2419322.44752276594513.6769690292419412.82702705594156.845151799
2419300.72814433593954.776271939 2418908.3492105593384.433227435
#Sta/Elev= 30
       0  2309.2    15.3 2306.82    56.5 2308.42    82.7 2306.57   167.9 2293.78
   219.8 2288.17   305.4 2266.85   337.1 2262.57   441.7 2260.35   463.1 2263.29
   479.9 2263.55   512.3  2260.9   681.6  2262.6   783.5 2260.38   819.1 2262.97
   824.4 2262.09   835.12256.869   846.7 2255.37   861.62256.841   879.5 2262.25
   938.9 2262.62   962.9 2260.89   982.6 2262.22    1002 2267.06  1133.1 2269.48
  1157.4 2272.91    1172 2278.77  1193.1 2280.23  1205.9 2284.86  1291.5  2291.3
#Mann= 10 ,-1 , 0
       0     .05       0   66.84      .1       0  127.61     .05       0
   238.9      .1       0  474.98     .05       0  518.95      .1       0
  618.71     .05       0  685.77     .06       0   835.1    .045       0
   861.6     .05       0
#XS Ineff= 2 , 0
          817.36 2265.92  883.88         2267.08
Permanent Ineff=
       F       F
Bank Sta=835.1,861.6
XS Rating Curve= 0 ,0
Exp/Cntr(USF)=0,0
Exp/Cntr=0.3,0.1

Type RM Length L Ch R = 1 ,26947   ,138.1,135.3,132.9
XS GIS Cut Line= 3
2419715.51017349594100.4981102162419386.56448536593877.375509735
     2419194.759      593292.616
#Sta/Elev= 30
       0 2337.61    51.5 2315.56      66 2306.54    90.2 2302.51     124 2281.88
   144.4 2264.01     153 2254.59   157.9 2252.66  168.312254.875   178.9 2256.41
  321.722257.421   343.1 2255.81  443.982258.099     493    2256   553.1 2258.58
   577.1 2258.12   589.8 2252.03   603.8 2250.44  612.092251.866   619.7 2255.54
   627.6 2256.95   644.5  2255.6   665.5 2257.62   707.6 2253.42   724.5 2257.19
  740.492258.163   829.7 2264.88   879.6 2273.06   972.8 2300.05  1012.9 2308.19
#Mann= 7 ,-1 , 0
       0      .1       0  168.31     .05       0  321.72      .1       0
  443.98     .06       0   589.8    .045       0  612.09     .05       0
  740.49      .1       0
#XS Ineff= 2 , 0
          557.38  2263.2  626.38          2264.4
Permanent Ineff=
       F       F
Bank Sta=589.8,612.09
XS Rating Curve= 0 ,0
Exp/Cntr(USF)=0,0
Exp/Cntr=0.3,0.1

Type RM Length L Ch R = 1 ,26812   ,195.7,196.2,195.3
XS GIS Cut Line= 3
2419971.00085491594109.3063872612419625.90811477593977.943985646
     2419257.454      593262.711
#Sta/Elev= 30
       0 2454.67      26 2442.59   128.7 2387.65   235.7 2339.08   299.9 2306.84
   321.3 2304.07   334.1 2300.48   376.2 2275.31   399.7 2257.88   413.2 2252.51
   427.3 2249.43     446 2253.07   552.7 2252.58   575.2 2250.41   620.4 2253.27
   723.7 2251.08   741.6 2253.65     7532248.804   759.6 2247.62   775.22248.697
   786.7  2253.5   849.6 2248.66   858.6 2251.67   872.1 2252.71   890.1 2259.44
   923.3 2262.84   980.1  2276.6  1020.6 2283.87  1070.1  2305.8  1173.8 2330.92
#Mann= 5 ,-1 , 0
       0      .1       0     8.5      .1       0  414.48     .06       0
     753    .045       0   775.2      .1       0
Bank Sta=753,775.2
XS Rating Curve= 0 ,0
Exp/Cntr(USF)=0,0
Exp/Cntr=0.3,0.1

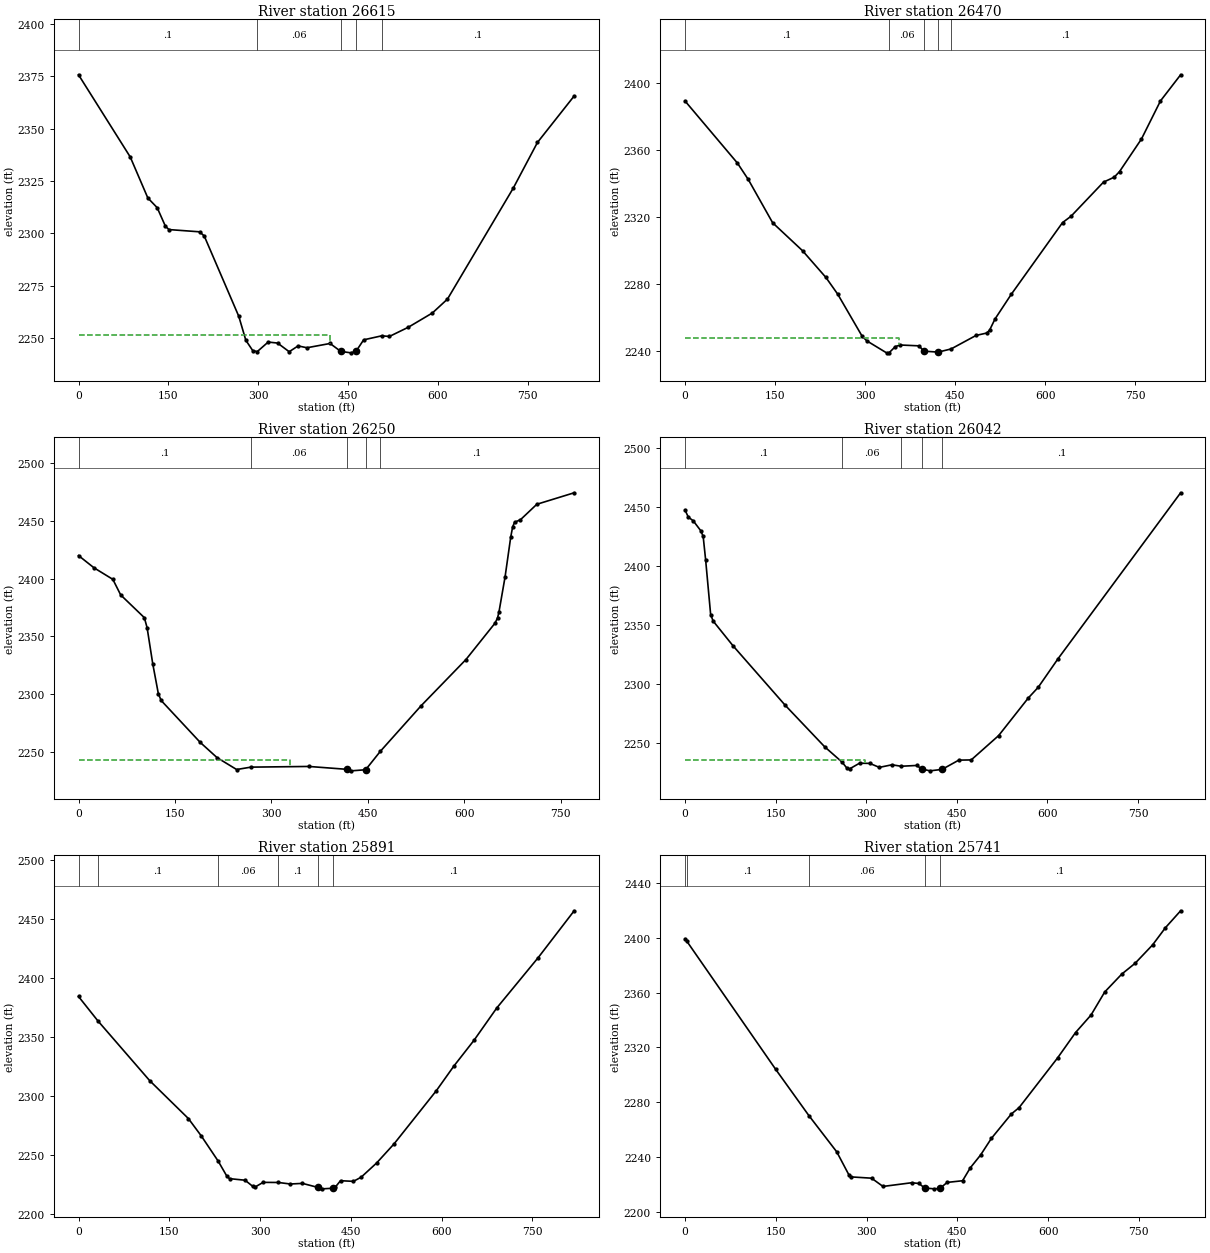
Type RM Length L Ch R = 1 ,26615   ,144.4,145.4,144.5
XS GIS Cut Line= 3
2419899.56048291593903.0008658592419683.64889024 593670.01329511
 2419450.3238122593216.209160969
#Sta/Elev= 30
       0 2375.75    86.4  2336.5   115.8 2316.91   131.4 2312.28   145.2 2303.39
   151.1 2301.82   202.2 2300.75     210 2298.76   267.7  2260.4   279.5 2248.94
   290.9 2244.06   298.52243.525   316.8  2248.1   332.5 2247.62   351.9 2243.48
   366.8 2246.26   381.6 2245.38   420.2 2247.42  438.012243.639     455 2242.95
  463.712243.772   476.3 2249.16  506.462251.077   519.3 2250.78   550.8 2255.16
   591.2 2262.01   616.3 2268.63   726.2 2321.63   766.6 2343.44   827.9 2365.62
#Mann= 5 ,-1 , 0
       0      .1       0   298.5     .06       0  438.01    .045       0
  463.71     .06       0  506.46      .1       0
#XS Ineff= 2 , 0
          420.79 2251.41
Permanent Ineff=
       F       F
Bank Sta=438.01,463.71
XS Rating Curve= 0 ,0
Exp/Cntr(USF)=0,0
Exp/Cntr=0.3,0.1

Type RM Length L Ch R = 1 ,26470   ,215.9,219.5,219.4
XS GIS Cut Line= 2
     2419948.287      593871.991     2419565.293      593140.934
#Sta/Elev= 30
       0 2389.48    87.3 2352.42   105.4 2342.62     146 2316.78   195.7 2300.13
   234.7 2284.15   254.4 2274.15     295 2249.09   302.8 2246.33   335.6 2239.19
  340.042239.303   350.2  2242.9   358.2 2243.87   389.8 2243.36   397.6 2240.18
   421.7 2239.64  443.082241.508   484.6 2249.56   502.7 2251.03   507.3  2252.8
   516.2 2259.37   543.3 2274.11   628.7 2316.91   642.7 2320.65   696.9 2341.05
   714.7 2343.99   723.6 2347.35   760.1 2366.79   791.7 2389.48   825.3 2405.09
#Mann= 5 ,-1 , 0
       0      .1       0  340.04     .06       0   397.6    .045       0
   421.7     .06       0  443.08      .1       0
#XS Ineff= 2 , 0
          357.02  2247.8
Permanent Ineff=
       F       F
Bank Sta=397.6,421.7
XS Rating Curve= 0 ,0
Exp/Cntr(USF)=0,0
Exp/Cntr=0.3,0.1

Type RM Length L Ch R = 1 ,26250   ,205.3,208.5,211.4
XS GIS Cut Line= 2
     2420104.756      593784.803 2419802.0241927593075.937268282
#Sta/Elev= 30
       0 2420.07    24.1 2409.44    53.4 2399.44    65.6 2385.93   102.4 2366.23
   106.7 2357.46   115.4 2326.41   124.1 2300.47   128.5 2294.48   189.3 2258.14
   215.4 2244.98   245.9 2234.64  268.032236.708   358.2  2237.3   417.4 2234.81
   424.2  2233.5   446.5 2234.44  469.322250.373   532.9 2289.98   602.5 2329.95
   647.7 2361.47   651.6 2365.94   653.8 2370.98   663.4 2401.73   672.1 2435.95
   675.1 2444.84   678.1 2448.94   687.3 2451.13   712.7  2464.5   770.8 2474.47
#Mann= 5 ,-1 , 0
       0      .1       0  268.03     .06       0   417.4    .045       0
   446.5     .06       0  469.32      .1       0
#XS Ineff= 2 , 0
          328.85 2243.11
Permanent Ineff=
       F       F
Bank Sta=417.4,446.5
XS Rating Curve= 0 ,0
Exp/Cntr(USF)=0,0
Exp/Cntr=0.3,0.1

Type RM Length L Ch R = 1 ,26042   ,153.3,150.8,148.3
XS GIS Cut Line= 2
     2420235.419      593763.988     2420047.624      592965.211
#Sta/Elev= 30
       0 2447.21     5.5 2441.15    13.7 2437.98      26 2429.69    30.1 2424.85
    34.2 2404.91    42.5  2358.6    46.6 2353.12    79.4 2332.23   165.7 2281.91
   231.4 2246.54  259.992233.695   268.4 2228.34   272.5 2227.89     289 2232.71
     306 2232.54   321.8 2229.17   342.6 2231.36  357.812230.131   383.5 2230.79
  392.482227.709   405.8 2226.24  425.682227.476   453.3  2235.3   473.9 2235.49
   519.3  2256.1   568.4 2287.94   584.8 2296.98   617.7 2321.24   820.6 2461.73
#Mann= 5 ,-1 , 0
       0      .1       0  259.99     .06       0  357.81      .1       0
  392.48    .045       0  425.68      .1       0
#XS Ineff= 2 , 0
          298.52  2235.1
Permanent Ineff=
       F       F
Bank Sta=392.48,425.68
XS Rating Curve= 0 ,0
Exp/Cntr(USF)=0,0
Exp/Cntr=0.3,0.1

Type RM Length L Ch R = 1 ,25891   ,149.8,150,150.2
XS GIS Cut Line= 2
     2420425.413      593701.053     2420143.123       592932.24
#Sta/Elev= 30
       0 2384.49   31.772363.925   117.6 2313.03   181.5 2280.86   202.8 2266.11
  230.712244.733   245.4 2231.62   249.7 2229.78   275.2 2228.45     288  2223.2
   292.3 2222.85     305 2226.62  330.172226.537     350 2225.24   370.1 2225.76
     395 2222.41     403 2221.13   420.4 2221.63   424.3 2222.58   432.9 2228.04
   454.2 2227.49     467    2231   492.5 2243.04   521.4 2259.32   591.4 2304.58
   620.3 2325.46   653.7 2347.42   691.1 2374.73   759.6 2417.52     819 2457.28
#Mann= 6 ,-1 , 0
       0      .1       0   31.77      .1       0  230.71     .06       0
  330.17      .1       0     395    .045       0   420.4      .1       0
Bank Sta=395,420.4
XS Rating Curve= 0 ,0
Exp/Cntr(USF)=0,0
Exp/Cntr=0.3,0.1

Type RM Length L Ch R = 1 ,25741   ,156.4,152.2,147.7
XS GIS Cut Line= 2
     2420561.875      593651.097     2420288.391      592879.107
#Sta/Elev= 30
       0 2399.34    2.792397.731     150 2303.85  204.642270.183   250.8 2243.61
   270.7 2226.93   273.8 2225.33   308.3 2224.38   327.2 2218.34   374.6 2221.05
   386.6  2220.5     396  2217.2     412 2216.59   421.1 2216.84   433.2 2221.29
   458.7 2222.51   471.4 2231.92   488.4 2241.28   506.4 2253.53   539.3 2271.31
   552.1 2275.96   615.7 2312.29   645.4 2330.84   670.9  2343.6   693.6 2360.49
   721.8 2373.58   743.8 2381.45   772.7  2394.9   793.9 2407.46     819 2419.83
#Mann= 5 ,-1 , 0
       0      .1       0    2.79      .1       0  204.64     .06       0
     396    .045       0   421.1      .1       0
Bank Sta=396,421.1
XS Rating Curve= 0 ,0
Exp/Cntr(USF)=0,0
Exp/Cntr=0.3,0.1