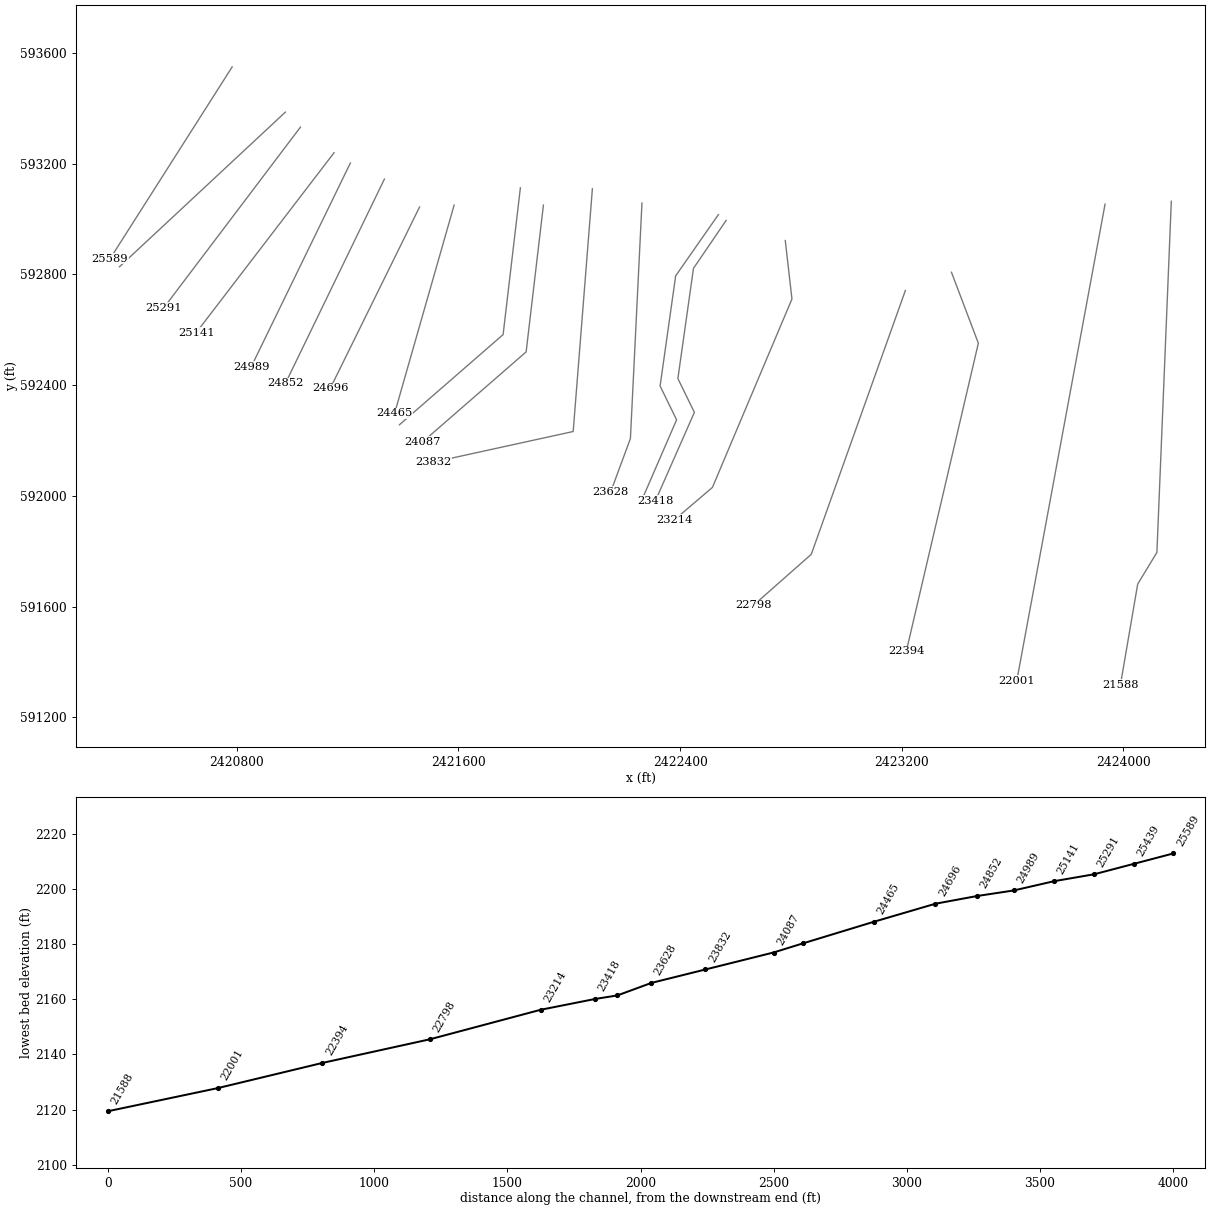
HEC-RAS study SMITHCK.prj: SMITHCK

--- SMITHCK.g01 (geometry) --- (continued)

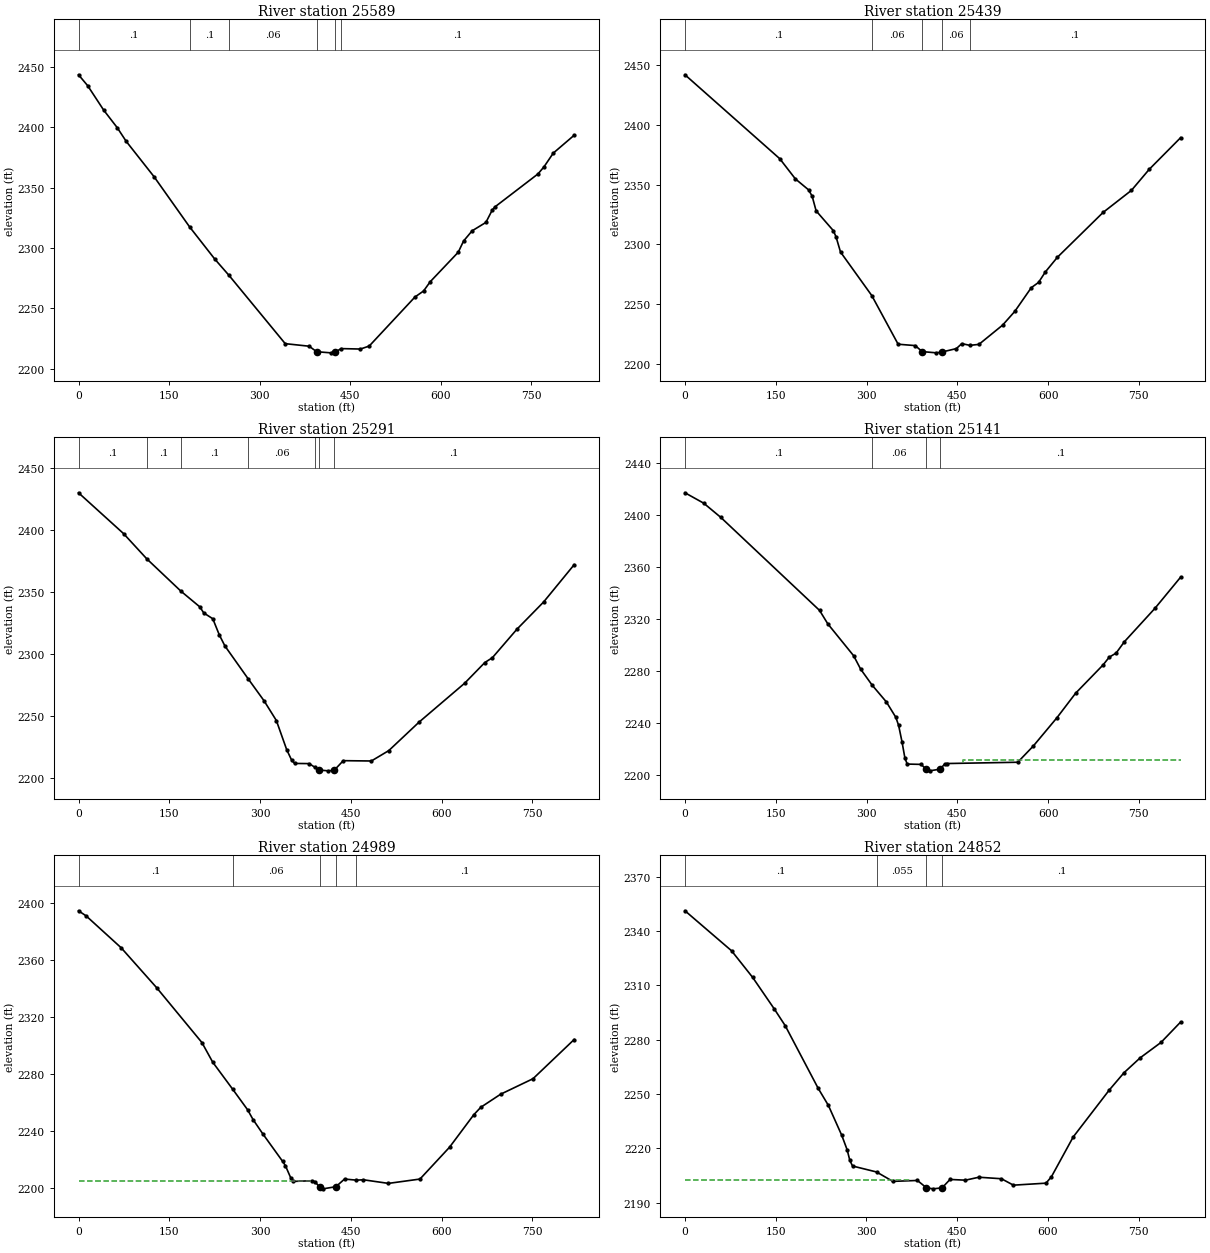
Type RM Length L Ch R = 1 ,25589   ,154.9,149.8,144.4
XS GIS Cut Line= 2
     2420783.113      593549.262     2420342.224       592856.08
#Sta/Elev= 30
       0 2443.69    15.2 2434.64    41.7  2414.4    64.1 2399.87      79 2388.51
   125.3 2359.09  184.012317.603   225.8 2290.86  249.592277.215   342.6 2220.68
   382.3 2218.56  394.712214.008   417.9 2213.07  424.912213.682  435.632216.583
   467.2 2216.22   481.8 2218.69   557.6 2259.36   571.9 2264.37     583 2272.08
   629.4 2296.54   638.2 2305.81   652.4 2314.28   675.2 2321.24   685.6 2331.38
   690.2 2334.12   761.5 2361.45   771.4 2367.28   786.9 2378.73   821.5 2393.54
#Mann= 6 ,-1 , 0
       0      .1       0  184.01      .1       0  249.59     .06       0
  394.71    .045       0  424.91     .06       0  435.63      .1       0
Bank Sta=394.71,424.91
XS Rating Curve= 0 ,0
Exp/Cntr(USF)=0,0
Exp/Cntr=0.3,0.1

Type RM Length L Ch R = 1 ,25439   ,144.8,148,151.2
XS GIS Cut Line= 2
     2420975.224      593385.994     2420376.303      592827.361
#Sta/Elev= 30
       0 2441.74   156.6 2371.57   182.4  2354.7   204.2 2345.53   210.1 2340.28
   216.7 2327.96   245.2 2311.38   249.6 2306.25     257 2293.55  308.612257.177
   352.2 2216.46   380.5  2215.3   391.8 2210.33   391.8  2210.3   415.3 2209.25
   424.6 2209.94   448.4 2212.79   457.4 2216.95  470.722215.507   485.7 2216.32
   524.8 2232.41   544.9 2243.86   572.2 2263.72   584.2 2268.12   595.5 2276.91
   615.3 2289.12   690.9 2326.66   737.8 2345.14   767.1 2362.68     819 2389.16
#Mann= 5 ,-1 , 0
       0      .1       0  308.61     .06       0   391.8    .045       0
   424.6     .06       0  470.72      .1       0
Bank Sta=391.8,424.6
XS Rating Curve= 0 ,0
Exp/Cntr(USF)=0,0
Exp/Cntr=0.3,0.1

Type RM Length L Ch R = 1 ,25291   ,150.1,150,149.9
XS GIS Cut Line= 2
     2421029.598      593331.725     2420535.732      592678.382
#Sta/Elev= 30
       0 2430.21    74.4 2397.23  112.93 2376.76  169.242350.685   200.5 2337.97
   206.9 2333.11   221.9  2328.4   232.6 2315.39   241.9 2306.42  279.972280.108
   306.6 2262.09   326.9 2246.17     344 2222.59   352.2 2214.09   357.2 2211.47
   381.1 2211.34  390.69 2208.33   397.4 2206.15   412.7 2205.49   422.4 2205.92
   437.5 2213.71   483.9 2213.45   512.7 2221.85   562.8  2244.9   638.1 2276.32
   671.4 2293.03   683.8 2296.89   724.4 2319.94   768.4 2341.88     819 2372.09
#Mann= 7 ,-1 , 0
       0      .1       0  112.93      .1       0  169.24      .1       0
  279.97     .06       0  390.69      .1       0   397.4    .045       0
   422.4      .1       0
Bank Sta=397.4,422.4
XS Rating Curve= 0 ,0
Exp/Cntr(USF)=0,0
Exp/Cntr=0.3,0.1

Type RM Length L Ch R = 1 ,25141   ,148.9,152.1,155.9
XS GIS Cut Line= 2
     2421150.965      593239.317      2420653.05      592589.054
#Sta/Elev= 30
       0 2416.93      31 2408.91    59.1 2398.03   222.4 2326.42     236 2316.07
   278.8 2291.47   290.2 2281.28  309.212268.952   332.7 2256.04   348.3 2244.24
     353    2238   358.7 2225.09   363.4 2212.81   367.2 2208.19     390 2207.94
   398.7 2204.27   404.3 2202.98   421.4 2204.27   428.9 2208.07   432.8  2208.6
   549.8 2209.59   575.5 2222.04   614.6 2243.83   645.5 2262.72   690.9  2284.5
     701 2290.43   712.4 2293.59   726.1 2302.34   776.5 2327.99     819 2352.01
#Mann= 4 ,-1 , 0
       0      .1       0  309.21     .06       0   398.7    .045       0
   421.4      .1       0
#XS Ineff= 2 , 0
                          458.84         2211.03
Permanent Ineff=
       F       F
Bank Sta=398.7,421.4
XS Rating Curve= 0 ,0
Exp/Cntr(USF)=0,0
Exp/Cntr=0.3,0.1

Type RM Length L Ch R = 1 ,24989   ,136.6,136.6,136.6
XS GIS Cut Line= 2
     2421209.844      593202.114     2420851.636      592465.591
#Sta/Elev= 30
       0  2394.4    12.7 2390.78    70.5 2368.47   129.1 2340.52   203.9 2302.09
   221.8  2288.3  255.022269.233   279.5 2254.93   288.4 2248.13   304.4 2238.19
   337.3 2218.83   341.8 2215.89   350.7 2207.27   355.1 2204.81   386.3 2205.28
   390.7 2204.59  398.412200.826     404  2199.6  425.312201.102   439.6 2206.46
   459.12205.685   470.8 2205.94   512.1 2203.42   564.2 2206.45   613.1 2228.77
   653.1  2251.5   664.7 2256.73   697.5 2265.89     751 2276.75     819 2304.22
#Mann= 5 ,-1 , 0
       0      .1       0  255.02     .06       0  398.41    .045       0
  425.31     .06       0   459.1      .1       0
#XS Ineff= 2 , 0
          383.88 2205.44
Permanent Ineff=
       F       F
Bank Sta=398.41,425.31
XS Rating Curve= 0 ,0
Exp/Cntr(USF)=0,0
Exp/Cntr=0.3,0.1

Type RM Length L Ch R = 1 ,24852   ,157.1,157,156.8
XS GIS Cut Line= 2
     2421332.654      593144.064     2420975.645      592406.625
#Sta/Elev= 30
       0 2351.28      77 2329.17   111.8 2314.49   147.7 2296.98   165.7 2287.77
   220.2 2253.14     237 2243.74   259.2 2227.14   268.1 2219.13   272.5  2213.3
     277 2210.21   316.62206.922   343.6 2201.73   384.2 2202.23  399.212198.159
   410.3  2197.6  425.012198.152   438.1 2202.79   463.6 2202.39   485.8 2204.02
   523.1 2203.18   542.9 2199.63   596.8 2200.74   605.8 2204.32   641.7 2226.26
   701.6 2252.32   725.8 2261.81   752.5 2270.03   786.8  2278.5   819.3 2289.79
#Mann= 4 ,-1 , 0
       0      .1       0   316.6    .055       0  399.21    .045       0
  425.01      .1       0
#XS Ineff= 2 , 0
          371.41 2202.42
Permanent Ineff=
       F       F
Bank Sta=399.21,425.01
XS Rating Curve= 0 ,0
Exp/Cntr(USF)=0,0
Exp/Cntr=0.3,0.1

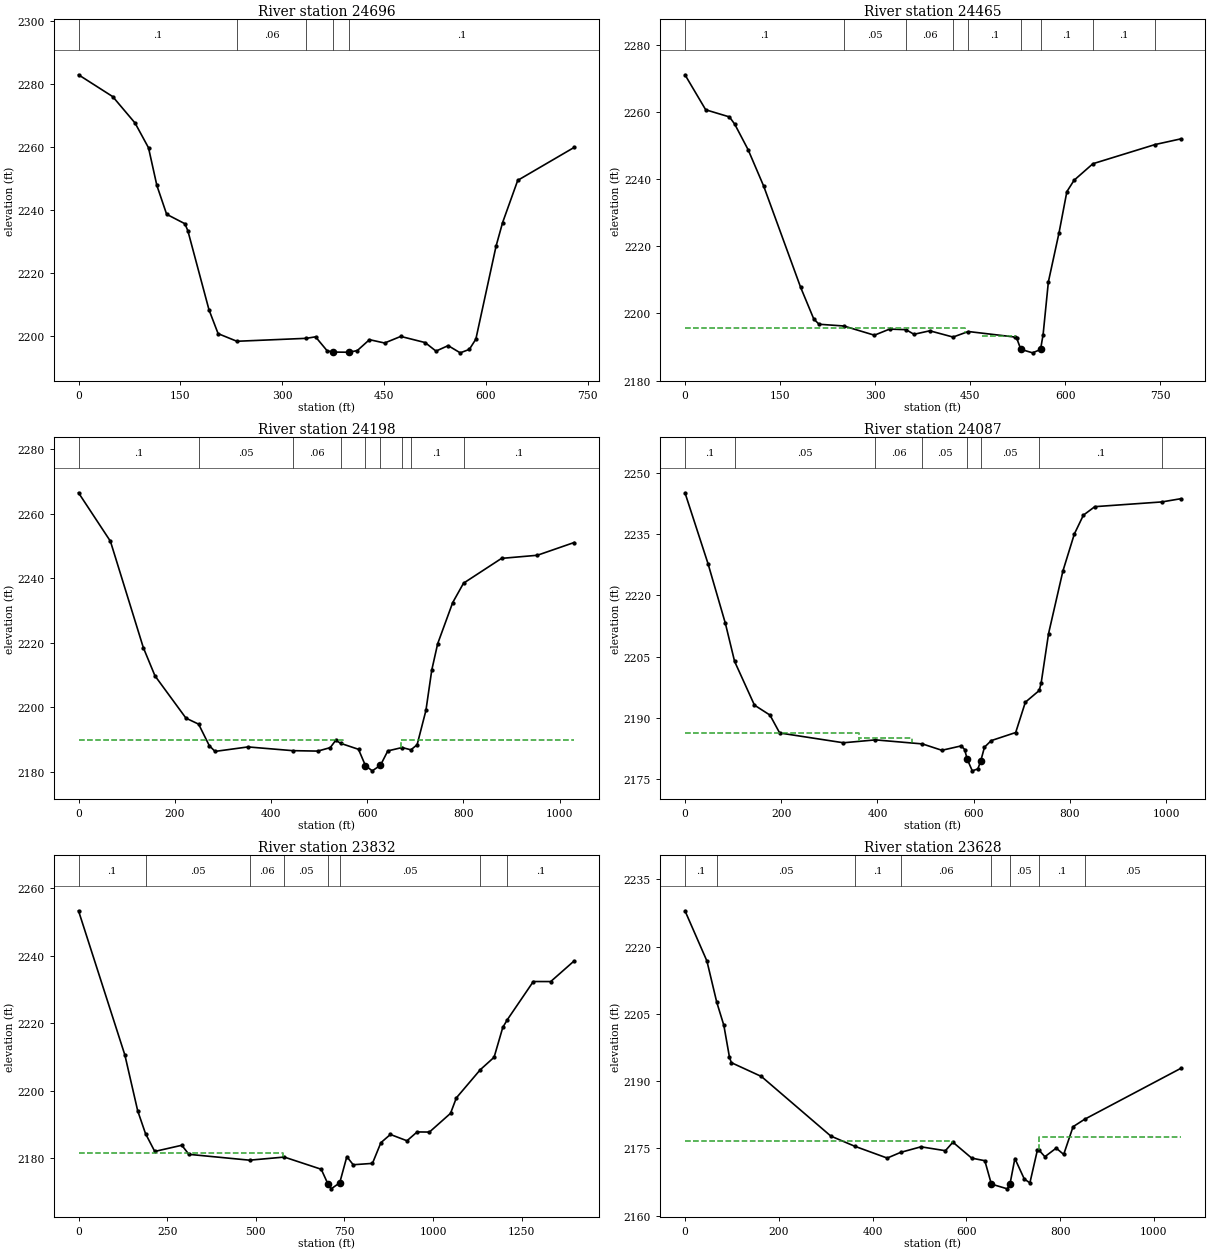
Type RM Length L Ch R = 1 ,24696   ,222.1,230.2,232.3
XS GIS Cut Line= 2
2421459.63201728593043.2365709072421137.32418561592388.223880732
#Sta/Elev= 30
       0 2283.03    50.4  2276.1    83.3 2267.71   103.1 2259.86   115.4 2247.91
   129.8 2238.76   156.6 2235.77     161 2233.57   192.2 2208.43   205.6 2200.88
  233.26 2198.46  335.452199.396   349.1 2199.87   366.1 2195.46  374.112195.037
  398.31 2194.98   410.6 2195.51   428.5 2198.97   450.8 2197.91   474.6    2200
   510.5 2198.05   526.5 2195.34   544.4 2197.08   562.2 2194.79   575.6 2195.89
   585.2 2199.13     615 2228.68   624.6 2236.13   646.9 2249.53     730 2259.98
#Mann= 5 ,-1 , 0
       0      .1       0  233.26     .06       0  335.45      .1       0
  374.11    .045       0  398.31      .1       0
#XS Ineff= 2 , 0
          344.25    2199
Permanent Ineff=
       F       F
Bank Sta=374.11,398.31
XS Rating Curve= 0 ,0
Exp/Cntr(USF)=0,0
Exp/Cntr=0.3,0.1

Type RM Length L Ch R = 1 ,24465   ,281.6,267.3,260.1
XS GIS Cut Line= 2
2421584.39633922593050.1679221262421369.52445144592298.116314888
#Sta/Elev= 30
       0 2271.03    32.7 2260.61    70.1 2258.49    78.4 2256.36    99.6 2248.74
   124.2 2237.88   182.4  2207.8   203.2 2198.35   211.5 2196.77  250.562196.254
   298.9 2193.51   322.9 2195.33  348.842195.153   361.3 2193.78   386.3 2194.82
     4232192.958  447.132194.606   520.2 2192.97   523.5 2192.58  529.932189.309
   548.5 2188.26  561.032189.261   565.1  2193.7   573.4 2209.38   590.1 2223.88
   602.6 2236.25     614 2239.64   643.72244.557  741.992250.273   782.1 2251.94
#Mann= 9 ,-1 , 0
       0      .1       0  250.56     .05       0  348.84     .06       0
     423    .055       0  447.13      .1       0  529.93    .045       0
  561.03      .1       0   643.7      .1       0  741.99      .1       0
#XS Ineff= 2 ,-1
       0  442.07 2195.54  468.26  520.06 2193.18
Permanent Ineff=
       F       F
Bank Sta=529.93,561.03
XS Rating Curve= 0 ,0
Exp/Cntr(USF)=0,0
Exp/Cntr=0.5,0.3

Type RM Length L Ch R = 1 ,24198   ,106.7,110.6,109.4
XS GIS Cut Line= 3
2421823.52795627593112.550083095 2421761.1457953592582.301714858
2421386.85282949592256.528207576
#Sta/Elev= 30
       0 2266.43    66.3 2251.43   134.7 2218.51   158.9 2209.78   223.3 2196.69
  249.632194.827   271.7  2188.2   283.7 2186.39   352.2 2187.78  444.822186.629
   497.2 2186.49   523.1 2187.56   534.6 2189.83  545.03 2188.88   581.9 2187.04
  596.312181.987   610.5 2180.38  627.512182.095   642.8 2186.55  672.592187.597
   690.8 2186.88   703.7 2188.45     722 2199.06   734.2  2211.6   746.4 2219.71
   777.7 2232.46  800.162238.451   879.2 2246.13   953.5 2247.09  1030.1 2251.04
#Mann= 9 ,-1 , 0
       0      .1       0  249.63     .05       0  444.82     .06       0
  545.03      .1       0  596.31    .045       0  627.51      .1       0
  672.59     .05       0   690.8      .1       0  800.16      .1       0
#XS Ineff= 2 , 0
             550    2190     670            2190
Permanent Ineff=
       F       F
Bank Sta=596.31,627.51
XS Rating Curve= 0 ,0
Exp/Cntr(USF)=0,0
Exp/Cntr=0.5,0.3

Type RM Length L Ch R = 1 ,24087   ,240.8,255.7,271.6
XS GIS Cut Line= 3
2421906.70417089593050.1679221262421844.32200993592519.919553889
2421470.02904411592194.146046606
#Sta/Elev= 30
       0 2245.13    47.8 2227.81      84 2213.14  103.122203.846   144.4 2193.14
   176.6 2190.71   196.8 2186.33   329.3 2183.93  395.912184.639  493.512183.649
   533.9 2182.09   574.2 2183.17   581.2 2182.28  586.512179.915   597.1 2177.06
   608.7 2177.54  614.812179.526   622.4 2182.85   636.5 2184.46   687.3 2186.44
   707.4 2193.86  736.232196.728   740.3  2198.6   755.6 2210.65   785.4 2225.96
   809.2 2235.04     828 2239.65   851.7 2241.73  991.362242.894  1030.1 2243.67
#Mann= 8 ,-1 , 0
       0      .1       0  103.12     .05       0  395.91     .06       0
  493.51     .05       0  586.51    .045       0  614.81     .05       0
  736.23      .1       0  991.36      .1       0
#XS Ineff= 2 ,-1
       0  361.93 2186.36  361.93  472.22 2185.04
Permanent Ineff=
       F       F
Bank Sta=586.51,614.81
XS Rating Curve= 0 ,0
Exp/Cntr(USF)=0,0
Exp/Cntr=0.5,0.3

Type RM Length L Ch R = 1 ,23832   ,202.4,203.4,203.5
XS GIS Cut Line= 3
2422083.45362697593109.0844074852422014.14011479 592232.26847831
2421508.15147581592121.366858809
#Sta/Elev= 30
       0 2253.27   130.7 2210.54   166.9    2194  188.942187.245     215 2181.97
   291.2  2183.8   311.3 2181.11  482.362179.379  580.172180.304   684.4 2176.69
  703.872172.207   712.5 2170.89  736.57 2172.68   756.6 2180.43   774.5 2178.03
   828.8 2178.43   852.6 2184.56   879.4    2187   926.2 2185.13   954.8 2187.75
   989.5 2187.71    1049 2193.26  1065.4 2197.84 1132.86 2206.18  1171.8 2209.87
  1196.4 2218.74 1209.432221.043  1282.4 2232.31  1331.5  2232.3  1397.6 2238.42
#Mann= 8 ,-1 , 0
       0      .1       0  188.94     .05       0  482.36     .06       0
  580.17     .05       0  703.87    .045       0  736.57     .05       0
 1132.86      .1       0 1209.43      .1       0
#XS Ineff= 2 , 0
          577.68  2181.6
Permanent Ineff=
       F       F
Bank Sta=703.87,736.57
XS Rating Curve= 0 ,0
Exp/Cntr(USF)=0,0
Exp/Cntr=0.3,0.1

Type RM Length L Ch R = 1 ,23628   ,107.4,127.2,134.4
XS GIS Cut Line= 3
2422262.41171047593057.5350792712422220.74504383592206.840634838
2422149.56448825592014.132301509
#Sta/Elev= 30
       0 2227.98    46.8 2216.78   67.792207.579    82.9 2202.44    94.9 2195.32
    98.9 2194.12     163 2191.04   311.1 2177.75     3622175.487   431.3 2172.85
  460.082174.123   503.3 2175.36   555.4 2174.49   571.4 2176.39   611.5 2172.84
   639.5 2172.26  653.432167.052   687.5 2165.99   693.22167.083   703.6 2172.75
   723.6  2168.2   735.6 2167.31   751.6 2174.63  754.292174.704   767.6 2173.15
   791.7 2175.07   807.7 2173.66   827.7 2179.84  852.372181.502  1057.1 2192.83
#Mann= 8 ,-1 , 0
       0      .1       0   67.79     .05       0     362      .1       0
  460.08     .06       0  653.43    .045       0   693.2     .05       0
  754.29      .1       0  852.37     .05       0
#XS Ineff= 2 , 0
          569.56 2176.66   754.9         2177.64
Permanent Ineff=
       F       F
Bank Sta=653.43,693.2
XS Rating Curve= 0 ,0
Exp/Cntr(USF)=0,0
Exp/Cntr=0.5,0.3

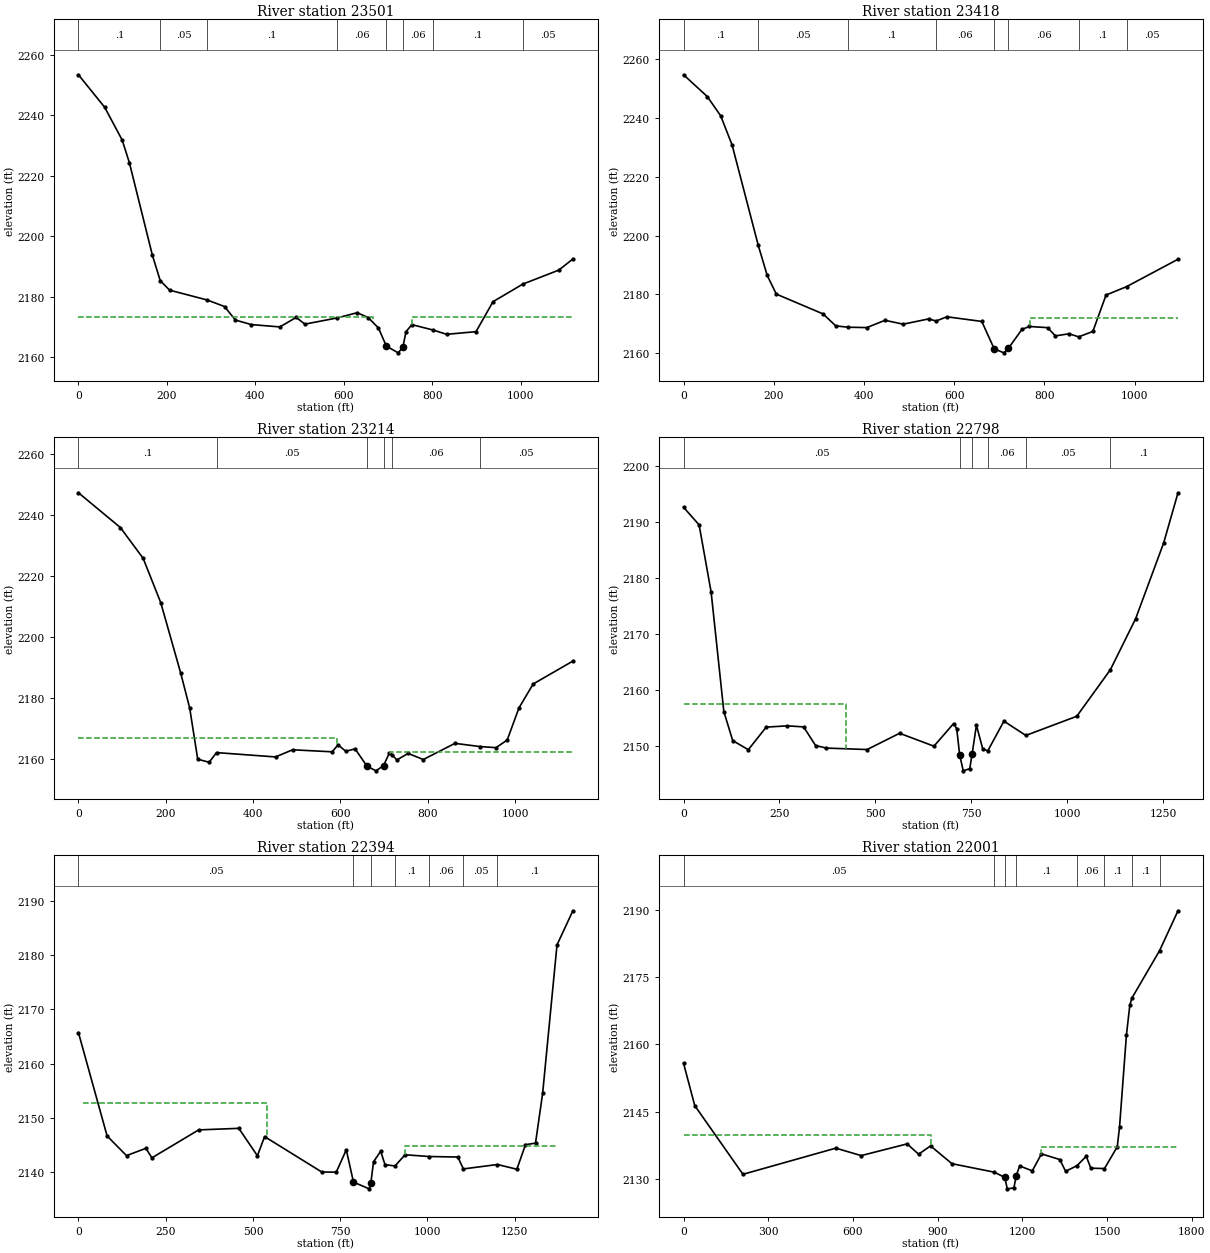
Type RM Length L Ch R = 1 ,23501   ,92.9,83.3,86.4
XS GIS Cut Line= 5
2422538.45337713593015.8684126142422384.09934945  592794.5759826
2422327.86496536592396.6162485632422387.41171049592274.548968166
2422264.14782165591989.826745942
#Sta/Elev= 30
       0 2253.43    59.3 2242.68    98.9 2231.83   115.2 2224.32   167.2 2193.71
  184.962185.322   206.1 2182.19  291.122178.936   330.2 2176.78   354.8  2172.3
   390.8 2170.81   455.4 2170.03   492.2 2173.18     512 2170.95  583.742172.974
   630.2 2174.73     655 2173.13   678.2 2169.68     696 2163.71   722.7 2161.46
   733.4 2163.26   740.5 2168.46   753.8 2170.79  802.192168.987   832.3 2167.59
   898.8 2168.46   937.2 2178.38 1004.552184.189  1086.2 2188.84  1117.8 2192.51
#Mann= 8 ,-1 , 0
       0      .1       0  184.96     .05       0  291.12      .1       0
  583.74     .06       0     696    .045       0   733.4     .06       0
  802.19      .1       0 1004.55     .05       0
#XS Ineff= 2 , 0
          664.85 2173.47  754.72         2173.47
Permanent Ineff=
       F       F
Bank Sta=696,733.4
XS Rating Curve= 0 ,0
Exp/Cntr(USF)=0,0
Exp/Cntr=0.5,0.3

Type RM Length L Ch R = 1 ,23418   ,217,204.1,182.1
XS GIS Cut Line= 5
 2422566.1684313 592994.769485282422448.33546056592821.485704839
2422392.10107647592423.5259707872422451.64782159 592301.45869039
2422311.02282161591982.014245957
#Sta/Elev= 30
       0 2254.57    52.7 2247.16    82.3 2240.64   107.7 2230.68  165.542196.696
   185.4 2186.48   205.6 2180.12   309.2  2173.4   337.5 2169.33  364.862168.872
   406.2 2168.75   446.6 2171.22     487 2169.91   543.5  2171.7  559.942170.987
   583.9 2172.42   661.2 2170.84  688.71 2161.55   710.2 2160.18  720.012161.663
   750.2 2168.13   766.8 2169.13     807 2168.73   824.5 2165.94   854.8 2166.65
  876.032165.611   907.5 2167.44   936.7  2179.8  982.342182.656  1096.3 2191.95
#Mann= 8 ,-1 , 0
       0      .1       0  165.54     .05       0  364.86      .1       0
  559.94     .06       0  688.71    .045       0  720.01     .06       0
  876.03      .1       0  982.34     .05       0
#XS Ineff= 2 , 0
                          767.08            2172
Permanent Ineff=
       F       F
Bank Sta=688.71,720.01
XS Rating Curve= 0 ,0
Exp/Cntr(USF)=0,0
Exp/Cntr=0.5,0.3

Type RM Length L Ch R = 1 ,23214   ,414.9,416.2,416.3
XS GIS Cut Line= 4
2422779.77282161592922.1184126142422803.82133096592710.923226044
2422516.80055705592030.3585043552422378.73115495591912.569801509
#Sta/Elev= 30
       0 2247.27      96  2235.9   148.3  2225.8   188.6 2211.28   234.4 2188.18
   254.9 2176.77   273.2 2160.06   299.5 2159.07  316.282162.232   451.5 2160.81
   490.5 2163.15   581.3 2162.49   594.7 2164.78   612.2 2162.68   633.8 2163.44
  660.882157.819   681.5 2156.26  698.882157.955   711.9 2161.98   718.42161.566
   729.3 2159.81   755.3 2161.96     790 2159.96   862.5 2165.25  919.472164.217
   956.6 2163.84   982.2 2166.34  1009.3  2176.9  1041.8  2184.7  1132.7 2192.18
#Mann= 6 ,-1 , 0
       0      .1       0  316.28     .05       0  660.88    .045       0
  698.88     .05       0   718.4     .06       0  919.47     .05       0
#XS Ineff= 2 , 0
          592.42 2166.92  712.71          2162.3
Permanent Ineff=
       F       F
Bank Sta=660.88,698.88
XS Rating Curve= 0 ,0
Exp/Cntr(USF)=0,0
Exp/Cntr=0.3,0.1

Type RM Length L Ch R = 1 ,22798   ,396.9,403.5,396.3
XS GIS Cut Line= 3
2423213.26387563 592741.722792892422873.62766591591788.662000308
2422665.68712935591604.981193011
#Sta/Elev= 30
       0 2192.67    40.5 2189.53    71.8 2177.53     105 2156.14   128.1 2150.94
   168.8 2149.31   215.4 2153.35   270.6 2153.58   313.1 2153.39   344.1 2150.06
   372.5  2149.6   478.7 2149.34   563.3 2152.25   652.8 2149.94   704.1 2153.99
   712.2 2153.07  719.812148.405   729.2 2145.53   746.2 2145.92  752.122148.456
   763.6 2153.69   780.1 2149.44   793.12149.098   835.3 2154.42  892.382151.861
  1025.2 2155.29 1112.882163.621  1178.7 2172.74  1251.8  2186.3  1289.2 2195.27
#Mann= 6 ,-1 , 0
       0     .05       0  719.81    .045       0  752.12     .05       0
   793.1     .06       0  892.38     .05       0 1112.88      .1       0
#XS Ineff= 2 , 0
             423  2157.4  766.49         2151.61
Permanent Ineff=
       F       F
Bank Sta=719.81,752.12
XS Rating Curve= 0 ,0
Exp/Cntr(USF)=0,0
Exp/Cntr=0.3,0.1

Type RM Length L Ch R = 1 ,22394   ,389,392.9,389.7
XS GIS Cut Line= 3
2423379.61630489592807.5706294692423476.71376239592551.147757851
2423216.72955124 591438.62876376
#Sta/Elev= 30
       0 2165.73    82.1 2146.68   137.7 2143.06   193.3 2144.41   210.4 2142.65
   344.4  2147.8   459.4 2148.09   512.8 2143.03   533.3 2146.57   697.2 2140.04
   738.7 2140.02   767.4 2144.13  788.092138.175   833.2 2136.94  837.792138.013
   845.5 2141.92     866 2143.87   878.3  2141.4  907.222141.154   935.8 2143.22
 1005.022142.897  1087.1  2142.8 1102.832140.609 1200.642141.423  1256.2 2140.55
  1280.9 2145.08  1309.6 2145.36  1330.1 2154.58  1371.2 2181.89  1416.7 2188.18
#Mann= 7 ,-1 , 0
       0     .05       0  788.09    .045       0  837.79     .05       0
  907.22      .1       0 1005.02     .06       0 1102.83     .05       0
 1200.64      .1       0
#XS Ineff= 4 ,-1
   14.43  539.35  2152.8  867.85  936.56 2142.24  936.56 1371.03  2144.9
 1371.03  1416.7 2142.24
Permanent Ineff=
       F       F       F       F
Bank Sta=788.09,837.79
XS Rating Curve= 0 ,0
Exp/Cntr(USF)=0,0
Exp/Cntr=0.3,0.1

Type RM Length L Ch R = 1 ,22001   ,422,412.8,403.2
XS GIS Cut Line= 2
2423934.12440239593053.6335977362423615.28224632591331.192819869
#Sta/Elev= 30
       0 2155.74    39.6 2146.34   210.4 2131.03   539.4 2136.86   629.3  2135.2
     792 2137.81   832.7 2135.51     875 2137.36   950.7  2133.4 1100.912131.502
  1137.8 2130.34  1146.9 2127.79  1170.3 2127.99  1178.5 2130.73  1190.7 2132.89
  1235.4  2131.8  1267.9 2135.58    1333 2134.32  1353.4  2131.7 1393.62 2132.94
  1426.6 2135.05  1442.8  2132.4 1491.192132.307  1536.4 2137.16  1544.5 2141.54
    1569 2162.12  1581.1 2168.77 1588.762170.356 1686.332180.875  1751.7 2189.77
#Mann= 8 ,-1 , 0
       0     .05       0 1100.91      .1       0  1137.8    .045       0
  1178.5      .1       0 1393.62     .06       0 1491.19      .1       0
 1588.76      .1       0 1686.33      .1       0
#XS Ineff= 2 , 0
          877.11 2139.88 1266.14         2137.15
Permanent Ineff=
       F       F
Bank Sta=1137.8,1178.5
XS Rating Curve= 0 ,0
Exp/Cntr(USF)=0,0
Exp/Cntr=0.3,0.1

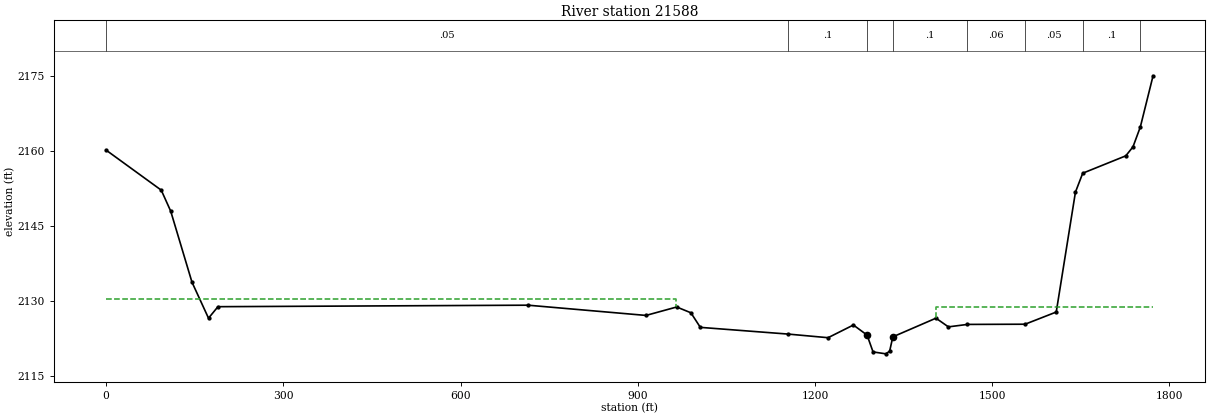
Type RM Length L Ch R = 1 ,21588   ,373.6,383.6,394.7
XS GIS Cut Line= 4
2424173.25601944593064.0306245642424121.27088529591795.593351527
2424051.95737311591681.2260564172423989.57521214591317.330117431
#Sta/Elev= 30
       0 2160.17    93.4 2152.15   109.4 2147.95   145.4 2133.73   173.4 2126.52
   189.4 2128.82   714.2 2129.12     914 2127.07     966 2128.76     990  2127.6
    1006 2124.68 1154.822123.334  1222.2 2122.61  1265.1 2125.15 1288.232123.138
  1298.4 2119.76  1320.2 2119.38  1326.5 2119.93 1331.83 2122.78  1404.9 2126.52
  1425.9 2124.78 1458.232125.271 1555.772125.311  1608.5 2127.75    1641 2151.76
 1653.312155.542  1726.2 2159.02  1738.4 2160.82 1750.862164.809  1772.4 2175.05
#Mann= 8 ,-1 , 0
       0     .05       0 1154.82      .1       0 1288.23    .045       0
 1331.83      .1       0 1458.23     .06       0 1555.77     .05       0
 1653.31      .1       0 1750.86      .1       0
#XS Ineff= 2 , 0
          965.05  2130.3 1404.18         2128.82
Permanent Ineff=
       F       F
Bank Sta=1288.23,1331.83
XS Rating Curve= 0 ,0
Exp/Cntr(USF)=0,0
Exp/Cntr=0.3,0.1