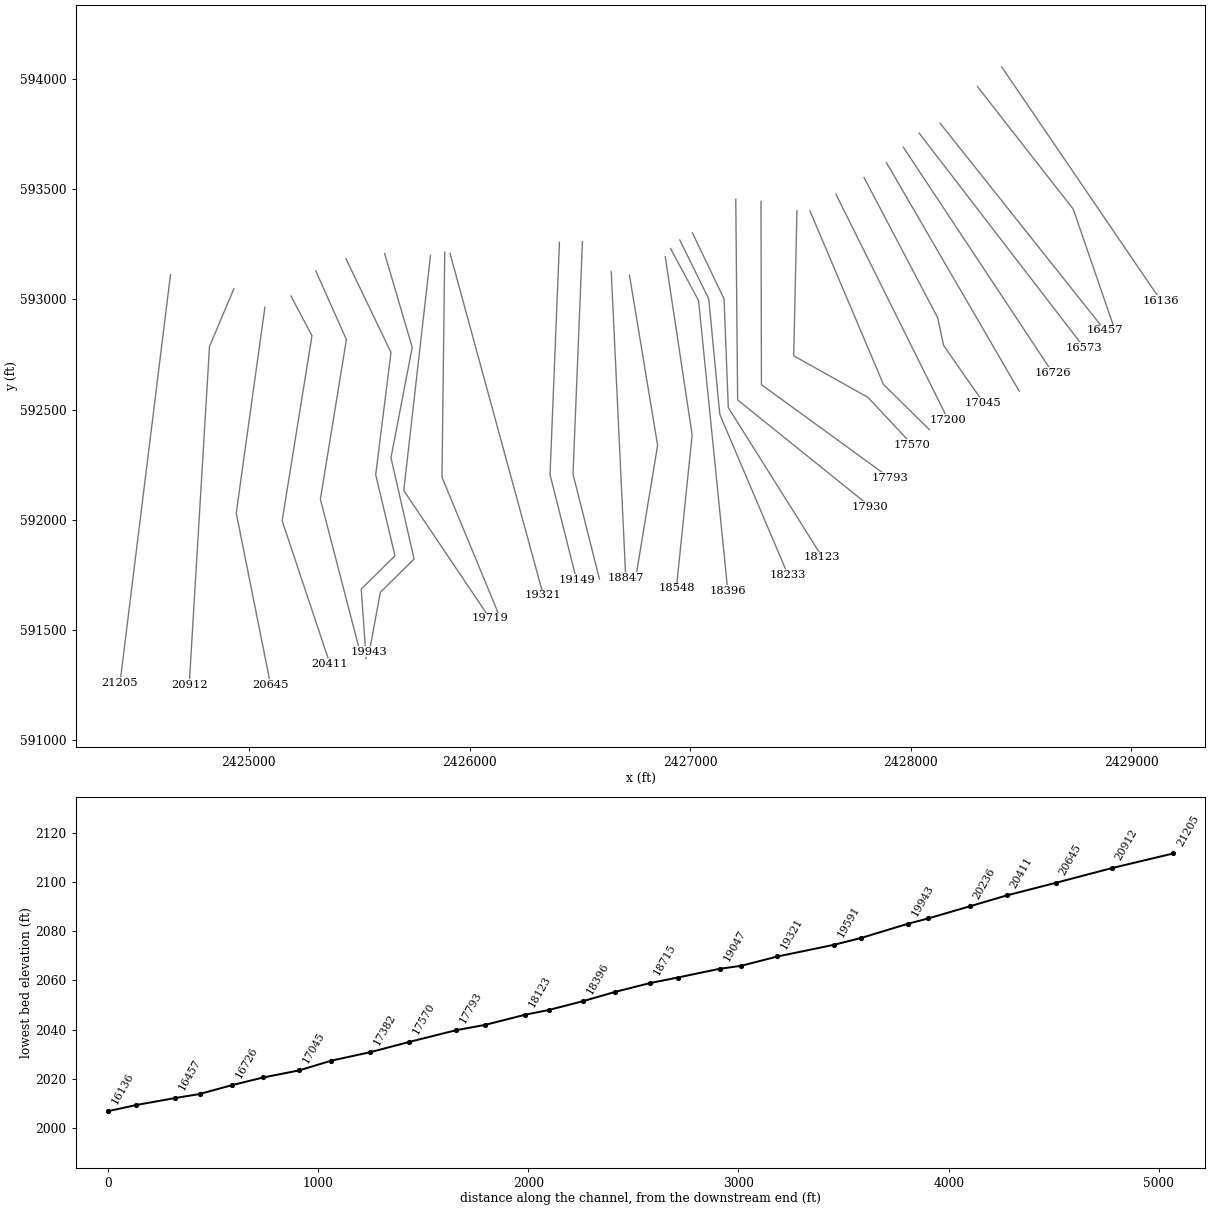
HEC-RAS study SMITHCK.prj: SMITHCK

--- SMITHCK.g01 (geometry) --- (continued)

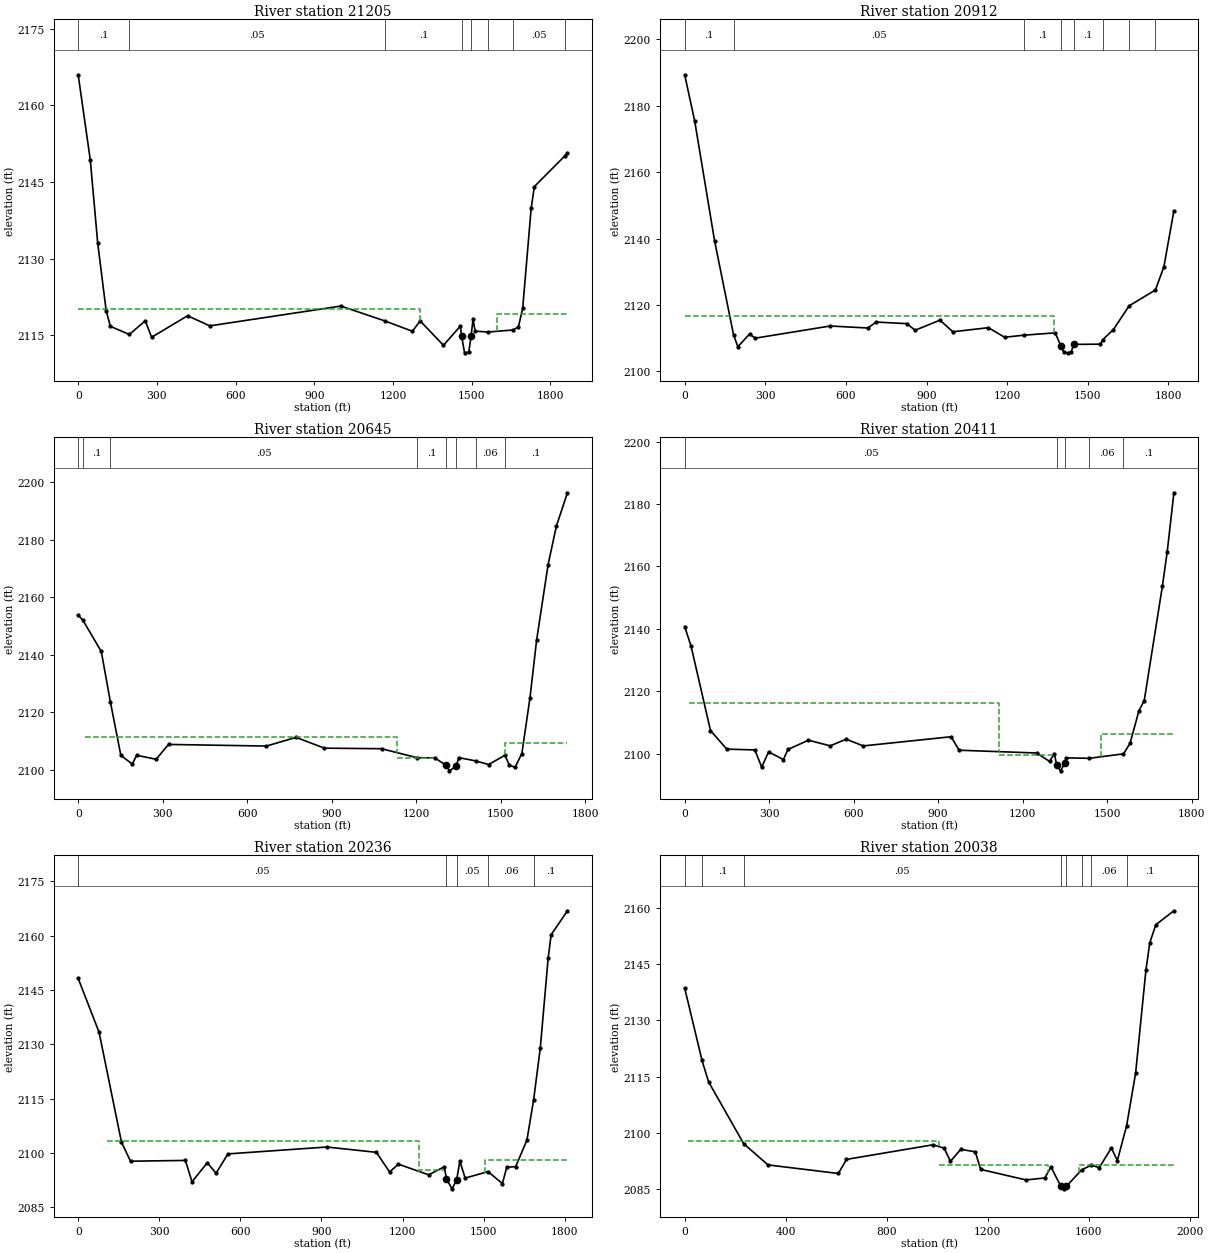
Type RM Length L Ch R = 1 ,21205   ,291.9,292.7,293.6
XS GIS Cut Line= 2
2424644.58790231593112.5500830962424415.85331209591261.879307681
#Sta/Elev= 30
       0 2165.95    46.2 2149.24    74.4 2133.01   106.6 2119.81   122.7 2116.73
  195.012115.145   255.7 2117.82   279.9  2114.6   416.9  2118.8   501.6 2116.83
  1001.3  2120.7 1170.78 2117.76  1273.9 2115.77  1303.5 2117.79  1392.2 2113.02
  1456.7 2116.78 1461.49 2114.78  1472.8 2111.55  1488.9 2111.72 1497.462114.776
    1505  2118.1  1513.1  2115.8 1561.092115.617 1658.662116.029  1678.3 2116.68
  1694.4 2120.31  1726.7 2139.89  1738.8 2144.08 1853.822150.013  1864.8 2150.65
#Mann= 8 ,-1 , 0
       0      .1       0  195.01     .05       0 1170.78      .1       0
 1461.49    .045       0 1497.46      .1       0 1561.09     .06       0
 1658.66     .05       0 1853.82      .1       0
#XS Ineff= 2 , 0
         1303.27 2120.08  1594.7         2119.11
Permanent Ineff=
       F       F
Bank Sta=1461.49,1497.46
XS Rating Curve= 0 ,0
Exp/Cntr(USF)=0,0
Exp/Cntr=0.3,0.1

Type RM Length L Ch R = 1 ,20912   ,260.7,267.2,273.4
XS GIS Cut Line= 3
2424932.12396414593049.0990815132424821.39589884 592786.81369929
 2424729.4780739591253.813208446
#Sta/Elev= 30
       0 2189.31    37.3 2175.41   111.1 2139.39  181.812111.044   197.9 2107.41
   241.3 2111.23     263    2110   541.2 2113.66   681.4 2113.06   712.9 2114.85
   826.3 2114.37   857.7 2112.38   949.9 2115.42   997.9 2111.92  1130.2 2113.16
  1190.3 2110.28 1262.052110.891  1378.6  2111.6 1400.262107.639  1410.6 2105.72
  1426.7 2105.58  1438.7 2105.87 1447.162108.128  1546.9 2108.19 1555.942109.572
    1595 2112.54  1653.9 2119.73 1751.872124.516  1783.3 2131.53  1820.5 2148.37
#Mann= 8 ,-1 , 0
       0      .1       0  181.81     .05       0 1262.05      .1       0
 1400.26    .045       0 1447.16      .1       0 1555.94     .06       0
  1653.9     .05       0 1751.87      .1       0
#XS Ineff= 2 , 0
         1375.42  2116.6
Permanent Ineff=
       F       F
Bank Sta=1400.26,1447.16
XS Rating Curve= 0 ,0
Exp/Cntr(USF)=0,0
Exp/Cntr=0.3,0.1

Type RM Length L Ch R = 1 ,20645   ,231,233.7,236.8
XS GIS Cut Line= 3
2425072.43613256592964.8181687042424942.63600472592031.259292966
2425098.33094721591252.256780996
#Sta/Elev= 30
       0  2153.8    17.12151.926      82 2141.12  114.64 2123.39   151.5 2104.97
   191.9 2101.94   207.6    2105   276.7 2103.61   320.7 2108.78   668.2 2108.21
   773.4 2111.23   874.1 2107.48  1076.9 2107.29 1203.512104.152  1265.2 2104.11
 1306.03 2101.55  1318.2 2099.59 1342.732101.331  1350.8  2104.2 1411.262103.039
  1456.9 2101.79 1515.14 2105.01  1530.3 2101.65  1550.7 2100.78  1575.2 2105.61
    1604 2125.06  1627.5 2145.05  1668.3 2171.34  1697.5 2184.67  1736.9 2196.33
#Mann= 8 ,-1 , 0
       0     .05       0    17.1      .1       0  114.64     .05       0
 1203.51      .1       0 1306.03    .045       0 1342.73      .1       0
 1411.26     .06       0 1515.14      .1       0
#XS Ineff= 4 ,-1
       0   24.35 2104.19   24.35 1130.33 2111.44 1130.33 1264.64 2104.19
 1513.87  1736.9 2109.28
Permanent Ineff=
       F       F       F       F
Bank Sta=1306.03,1342.73
XS Rating Curve= 0 ,0
Exp/Cntr(USF)=0,0
Exp/Cntr=0.3,0.1

Type RM Length L Ch R = 1 ,20411   ,177.5,175.4,173.5
XS GIS Cut Line= 4
2425190.55029909 593015.84626751 2425285.7964305592835.333157821
2425150.63508173591996.6396603482425366.96208446591348.395635896
#Sta/Elev= 30
       0 2140.71    22.8 2134.38    91.7 2107.39   149.4 2101.42   249.2 2101.16
   273.5 2095.64   297.9 2100.55   350.5 2098.06   366.7 2101.32   439.6 2104.28
   516.6 2102.47   573.3 2104.61   634.1 2102.45     946 2105.39   974.4 2101.07
  1249.5 2100.18  1295.8 2097.47  1312.4 2099.99  1321.1 2096.22  1334.5 2094.46
  1350.6 2097.02  1354.9 2098.62 1436.492098.478 1558.03 2099.91  1581.1 2103.24
  1612.7 2113.67  1631.7    2117  1696.4 2153.82  1713.3 2164.72    1737  2183.6
#Mann= 5 ,-1 , 0
       0     .05       0  1321.1    .045       0  1350.6      .1       0
 1436.49     .06       0 1558.03      .1       0
#XS Ineff= 3 ,-1
   14.21 1116.12 2116.24 1116.12 1309.34 2099.69 1477.34    1737 2106.16
Permanent Ineff=
       F       F       F
Bank Sta=1321.1,1350.6
XS Rating Curve= 0 ,0
Exp/Cntr(USF)=0,0
Exp/Cntr=0.3,0.1

Type RM Length L Ch R = 1 ,20236   ,218.5,197.7,178.4
XS GIS Cut Line= 4
2425303.18307176 593129.253263662425441.75183292592818.004779774
 2425323.9188622592093.678577411 2425508.5931938591381.743157376
#Sta/Elev= 30
       0 2148.15    77.2 2133.31   160.2 2102.92   193.6 2097.68   396.7  2097.9
     421 2091.99   477.7 2097.26   510.1 2094.36     554  2099.7   919.9  2101.6
  1103.4 2100.13  1151.9 2094.72  1184.9 2096.86  1296.5 2093.92  1354.3 2096.13
 1362.542092.786  1383.2 2090.05 1399.842092.438  1412.2 2097.71  1431.5 2093.02
 1516.482094.801  1569.3  2091.5  1585.7 2096.03  1618.5 2096.19  1660.1 2103.48
 1684.942114.626  1709.7 2128.98  1738.6 2153.67  1749.7 2160.23    1810 2166.85
#Mann= 5 ,-1 , 0
       0     .05       0 1362.54    .045       0 1399.84     .05       0
 1516.48     .06       0 1684.94      .1       0
#XS Ineff= 3 ,-1
  105.98 1262.68 2103.22 1262.68 1353.36 2095.17 1504.43    1810  2098.1
Permanent Ineff=
       F       F       F
Bank Sta=1362.54,1399.84
XS Rating Curve= 0 ,0
Exp/Cntr(USF)=0,0
Exp/Cntr=0.5,0.3

Type RM Length L Ch R = 1 ,20038   ,109.4,95.4,88.9
XS GIS Cut Line= 6
2425440.08901692593184.1792779872425643.91624347592759.858444551
2425574.60273128592205.3503470472425661.93462034591837.561037243
2425509.06504508591686.5332640982425531.16667042591371.585103026
#Sta/Elev= 30
       0 2138.65   68.642119.369    94.8 2113.62  233.882097.149     330  2091.5
   608.9 2089.21   641.1 2092.97   984.3 2096.87  1028.1 2095.95  1052.7 2092.45
  1093.8 2095.65  1151.4 2094.99  1172.5  2090.3  1352.8 2087.49  1426.9 2088.03
  1451.2 2090.98 1489.892085.841  1502.5 2085.12 1512.49 2085.83 1572.622090.158
  1611.72091.476  1642.2 2090.74  1690.3 2096.03  1714.3 2092.66 1750.952102.001
  1786.5 2115.95  1827.4 2143.46  1842.6 2150.71  1866.7 2155.54  1938.2 2159.25
#Mann= 8 ,-1 , 0
       0     .05       0   68.64      .1       0  233.88     .05       0
 1489.89    .045       0 1512.49     .06       0 1572.62     .05       0
  1611.7     .06       0 1750.95      .1       0
#XS Ineff= 4 ,-1
       0   11.27  2091.5   11.27 1005.64 2097.92 1005.64  1437.5  2091.5
  1562.5  1938.2  2091.5
Permanent Ineff=
       F       F       F       F
Bank Sta=1489.89,1512.49
XS Rating Curve= 0 ,0
Exp/Cntr(USF)=0,0
Exp/Cntr=0.5,0.3

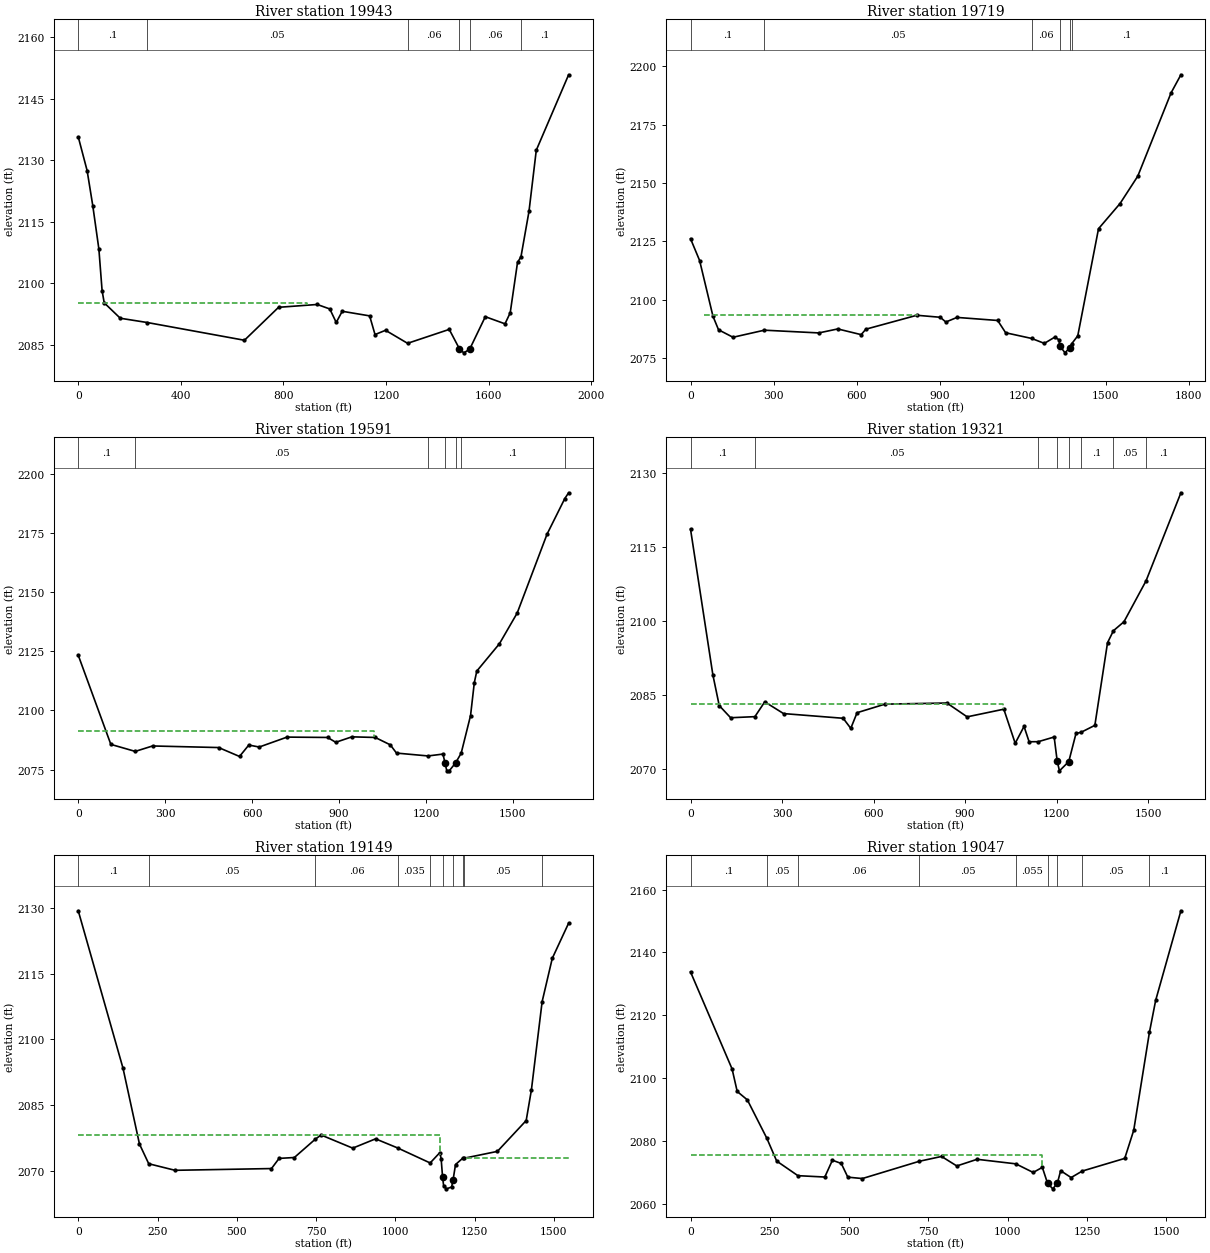
Type RM Length L Ch R = 1 ,19943   ,187.6,223.7,247
XS GIS Cut Line= 6
2425615.22098173593207.952367866 2425740.1850104592782.962948613
2425643.91624347 592282.365360592425748.49931958591822.826620351
2425595.62974432591671.7988472062425545.90108731591402.895738922
#Sta/Elev= 30
       0 2135.69    34.6 2127.46    56.6 2118.93    80.5 2108.29      93 2098.16
   101.3 2095.19   163.9 2091.43  268.762090.393   648.1 2086.06   781.2  2094.1
   931.9 2094.79     981  2093.7  1006.1  2090.4  1029.5 2093.13  1136.4 2092.01
  1157.4 2087.45  1198.4 2088.49 1284.392085.313  1446.8 2088.71  1486.3 2084.01
  1503.6 2082.99  1526.4 2083.86  1587.5 2091.81  1664.3 2090.07  1684.6 2092.75
  1713.1 2105.04 1726.582106.426  1757.8 2117.48  1786.3 2132.43  1912.4 2150.84
#Mann= 6 ,-1 , 0
       0      .1       0  268.76     .05       0 1284.39     .06       0
  1486.3    .045       0  1526.4     .06       0 1726.58      .1       0
#XS Ineff= 2 ,-1
       0  890.64  2095.2 1179.28 1390.542086.645
Permanent Ineff=
       F       F
Bank Sta=1486.3,1526.4
XS Rating Curve= 0 ,0
Exp/Cntr(USF)=0,0
Exp/Cntr=0.5,0.3

Type RM Length L Ch R = 1 ,19719   ,132.2,128,123.3
XS GIS Cut Line= 3
2425822.91331457593199.2985344572425701.78887209592133.580164486
     2426091.952      591553.583
#Sta/Elev= 30
       0 2126.14    32.8 2116.79    81.1 2092.88   101.2 2087.08   153.5 2083.88
   266.72086.913   463.5 2085.74   531.9 2087.45   616.5    2085   633.4 2087.34
   817.7 2093.31   902.3 2092.45   922.4 2090.41   962.6 2092.39  1109.6 2091.08
  1138.5 2085.81 1232.492083.367  1278.3 2081.26  1315.5  2083.9  1329.9 2082.91
  1335.6 2079.97  1352.9  2077.2  1370.2 2079.44 1377.742081.194    1399  2084.5
    1474 2130.43  1551.8 2141.23  1615.8 2152.96  1736.1 2188.69  1771.6 2196.44
#Mann= 6 ,-1 , 0
       0      .1       0   266.7     .05       0 1232.49     .06       0
  1335.6    .045       0  1370.2     .06       0 1377.74      .1       0
#XS Ineff= 3 ,-1
       0   49.24 2084.61   49.24   820.5 2093.61 1219.34 1300.51 2082.42
Permanent Ineff=
       F       F       F
Bank Sta=1335.6,1370.2
XS Rating Curve= 0 ,0
Exp/Cntr(USF)=0,0
Exp/Cntr=0.3,0.1

Type RM Length L Ch R = 1 ,19591   ,272.6,270,266.7
XS GIS Cut Line= 3
2425887.56276151593215.2499050572425874.96128409592193.798095016
      2426131.34      591574.153
#Sta/Elev= 30
       0 2123.33   112.5 2085.63  196.612082.663   256.5 2084.96   484.5 2084.29
   556.5 2080.52   588.5 2085.35   624.5 2084.51   720.5 2088.71   860.5 2088.56
   888.5 2086.51   944.2 2088.82  1024.8 2088.56  1076.7 2085.44  1098.2 2081.95
 1207.222080.739  1258.5 2081.53 1265.432077.872  1271.5 2074.58  1280.1 2074.44
 1301.812077.751 1321.382081.899  1353.7 2097.81  1366.7 2111.75  1375.3 2116.64
  1453.3 2128.19  1514.6 2141.17  1617.7 2174.55  1678.92189.602  1692.1 2192.05
#Mann= 7 ,-1 , 0
       0      .1       0  196.61     .05       0 1207.22     .06       0
 1265.43    .045       0 1301.81     .06       0 1321.38      .1       0
  1678.9      .1       0
#XS Ineff= 2 , 0
         1020.74 2091.08
Permanent Ineff=
       F       F
Bank Sta=1265.43,1301.81
XS Rating Curve= 0 ,0
Exp/Cntr(USF)=0,0
Exp/Cntr=0.3,0.1

Type RM Length L Ch R = 1 ,19321   ,172.7,172.3,172.5
XS GIS Cut Line= 2
2425911.42959325593209.4758326552426334.19239105591658.906232425
#Sta/Elev= 30
       0 2118.58    73.3 2089.07    94.1 2082.88   131.4 2080.42  210.962080.639
   243.3 2083.64   304.9 2081.26   500.3 2080.31   525.2 2078.27   545.9 2081.44
   637.1 2083.17   840.3  2083.4   906.6  2080.6  1026.8 2082.15  1064.1 2075.25
  1093.1 2078.66  1109.7 2075.56  1139.6 2075.57  1191.8 2076.52  1201.92071.581
  1209.2 2069.67 1239.682071.543  1263.5 2077.26 1279.242077.447  1325.2 2078.88
  1366.7  2095.6 1386.072098.035  1420.6 2099.85 1492.892108.118  1607.2 2125.96
#Mann= 8 ,-1 , 0
       0      .1       0  210.96     .05       0  1139.6     .06       0
  1201.9    .045       0 1239.68     .06       0 1279.24      .1       0
 1386.07     .05       0 1492.89      .1       0
#XS Ineff= 2 , 0
          1024.8  2083.1
Permanent Ineff=
       F       F
Bank Sta=1201.9,1239.68
XS Rating Curve= 0 ,0
Exp/Cntr(USF)=0,0
Exp/Cntr=0.5,0.3

Type RM Length L Ch R = 1 ,19149   ,101.8,101.8,101.8
XS GIS Cut Line= 3
2426407.43422978593259.6846782522426364.71875301592205.421579386
2426484.80754379591729.062857042
#Sta/Elev= 30
       0 2129.36   141.1 2093.44   193.1 2076.11  222.26 2071.62   305.2 2070.12
   609.4 2070.52   633.4 2072.84   681.5 2073.04   747.12077.199   765.8 2078.18
   865.6 2075.18   937.6  2077.3 1007.562075.213 1109.732071.796  1140.3 2074.16
  1144.4 2072.78 1148.992068.508  1152.3 2066.58  1160.9 2065.89  1177.4  2066.3
 1181.992067.916  1189.8 2071.44 1212.412072.872 1215.672072.861  1321.8 2074.44
  1412.6 2081.48    1429 2088.44  1462.92108.628  1494.9 2118.51  1546.4 2126.53
#Mann= 10 ,-1 , 0
       0      .1       0  222.26     .05       0   747.1     .06       0
 1007.56    .035       0 1109.73     .06       0 1148.99    .045       0
 1181.99     .06       0 1212.41      .1       0 1215.67     .05       0
  1462.9      .1       0
#XS Ineff= 2 , 0
         1141.83  2078.2  1222.5            2073
Permanent Ineff=
       F       F
Bank Sta=1148.99,1181.99
XS Rating Curve= 0 ,0
Exp/Cntr(USF)=0,0
Exp/Cntr=0.5,0.3

Type RM Length L Ch R = 1 ,19047   ,204.6,200.3,196
XS GIS Cut Line= 3
2426511.60089645593261.7680115852426468.88541968592207.504912719
2426588.97421046591731.146190375
#Sta/Elev= 30
       0  2133.8   131.1 2102.87   147.2 2095.71   179.2 2093.03  240.432080.846
   271.7 2073.54  338.592068.887   423.4 2068.45   447.4 2073.81   475.4 2072.77
     496 2068.41   541.9 2067.97  720.65 2073.45   791.6 2075.01   839.7 2071.98
   903.7  2074.1 1025.732072.655  1080.6 2069.91  1109.4 2071.53 1125.892066.472
  1142.4 2064.69 1156.932066.506  1167.2 2070.47  1200.2 2068.28 1235.282070.353
  1369.3 2074.39  1397.7 2083.37 1447.152114.555  1466.8 2124.73  1546.4 2153.28
#Mann= 9 ,-1 , 0
       0      .1       0  240.43     .05       0  338.59     .06       0
  720.65     .05       0 1025.73    .055       0 1125.89    .045       0
 1156.93      .1       0 1235.28     .05       0 1447.15      .1       0
#XS Ineff= 2 , 0
         1107.55  2075.4
Permanent Ineff=
       F       F
Bank Sta=1125.89,1156.93
XS Rating Curve= 0 ,0
Exp/Cntr(USF)=0,0
Exp/Cntr=0.5,0.3

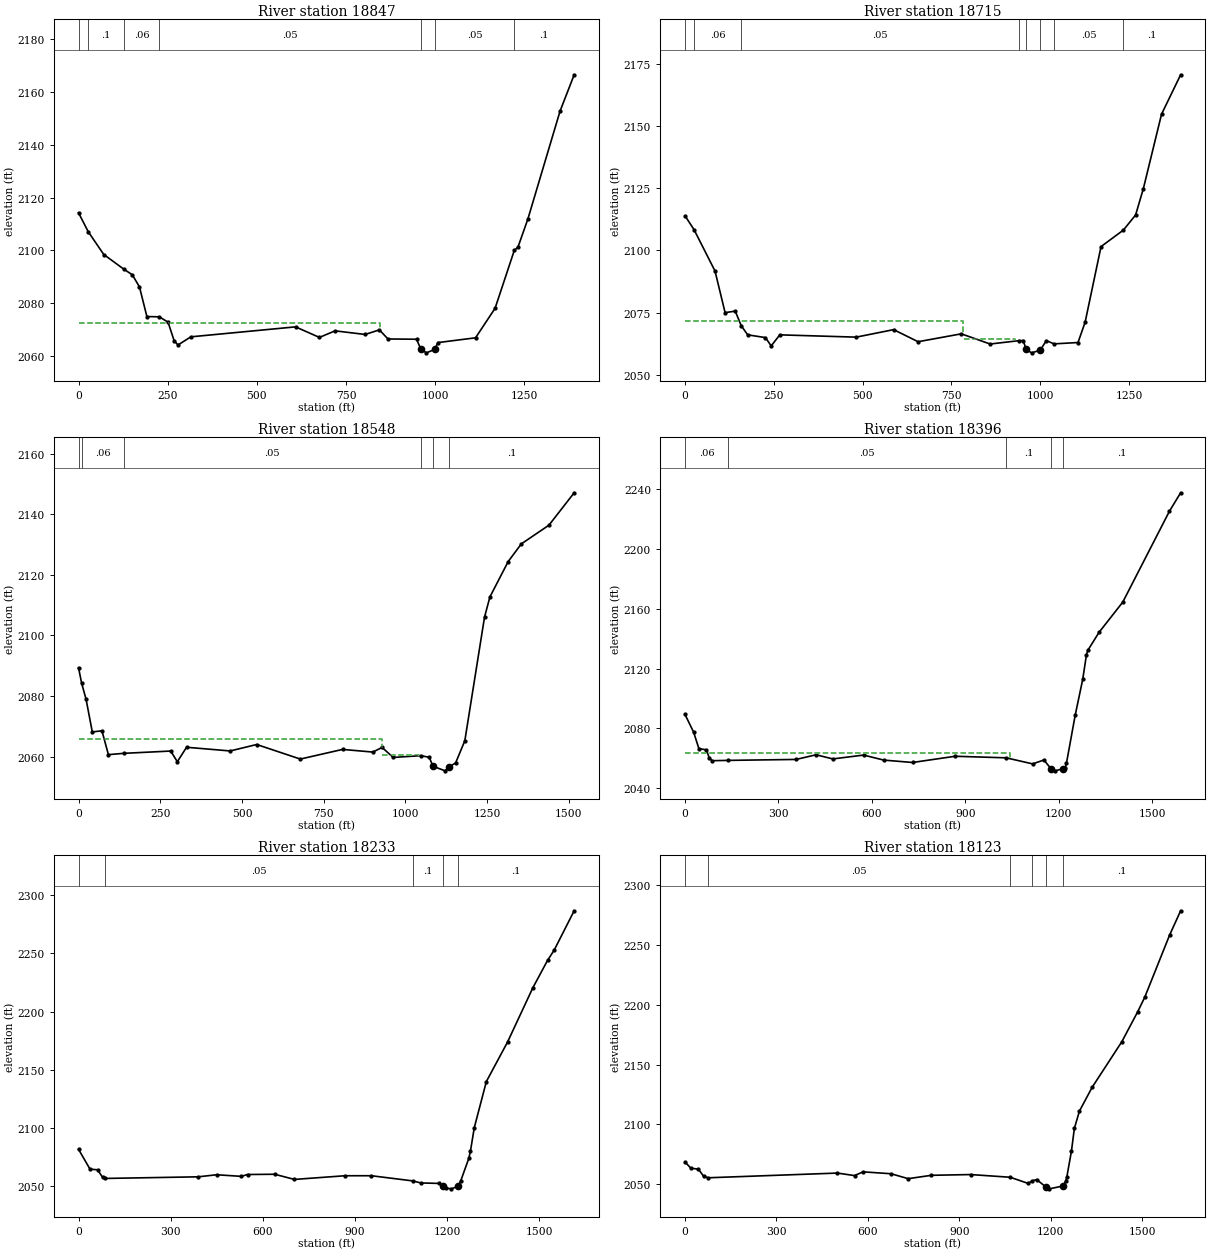
Type RM Length L Ch R = 1 ,18847   ,137.2,131.7,126.8
XS GIS Cut Line= 2
2426642.18974526593125.426100211     2426707.913       591737.36
#Sta/Elev= 30
       0 2114.24   27.222107.056    70.8 2098.41  126.772092.874   150.8 2090.72
   170.9 2086.13   191.7 2074.88  226.31 2074.78     251 2072.76   268.2 2065.67
     279 2064.11     315 2067.19   608.4 2070.97   675.4 2066.97   719.3 2069.46
   803.5 2068.09   843.5 2069.83   867.6 2066.38   947.7 2066.28  959.712062.537
   975.4 2061.12  998.412062.413  1007.7 2065.01  1113.1 2066.82  1167.9 2078.02
 1221.732099.966  1231.9 2101.16    1260 2111.94    1350 2152.77  1389.6 2166.56
#Mann= 7 ,-1 , 0
       0     .05       0   27.22      .1       0  126.77     .06       0
  226.31     .05       0  959.71    .045       0  998.41     .05       0
 1221.73      .1       0
#XS Ineff= 2 , 0
          844.42 2072.48
Permanent Ineff=
       F       F
Bank Sta=959.71,998.41
XS Rating Curve= 0 ,0
Exp/Cntr(USF)=0,0
Exp/Cntr=0.3,0.1

Type RM Length L Ch R = 1 ,18715   ,164,166.5,169.3
XS GIS Cut Line= 3
2426724.69834921 593110.097543362426852.35301056592338.285430157
     2426752.495      591733.877
#Sta/Elev= 30
       0 2113.89   25.472108.324    84.5 2091.71   112.9 2075.01   141.5 2075.61
   158.22069.805   176.3  2066.1   226.4 2064.99   242.6 2061.66   266.9 2066.09
   481.8 2065.17   587.2 2068.18   656.1 2063.33   777.7  2066.5   858.8 2062.41
   941.22063.779     952 2063.77   960.1 2060.22   975.6 2058.87   999.8 2059.93
  1016.9 2063.78 1038.732062.469  1106.1 2063.01  1126.1 2071.16  1170.9 2101.52
  1233.82108.145  1268.2  2114.2    1290 2124.79  1341.2 2154.68  1394.9 2170.48
#Mann= 8 ,-1 , 0
       0     .05       0   25.47     .06       0   158.2     .05       0
   941.2      .1       0   960.1    .045       0   999.8      .1       0
 1038.73     .05       0  1233.8      .1       0
#XS Ineff= 2 ,-1
       0  781.29 2071.64  784.69  928.97 2064.46
Permanent Ineff=
       F       F
Bank Sta=960.1,999.8
XS Rating Curve= 0 ,0
Exp/Cntr(USF)=0,0
Exp/Cntr=0.3,0.1

Type RM Length L Ch R = 1 ,18548   ,149.5,152,158.1
XS GIS Cut Line= 3
2426887.02486004593193.6746662652427008.79340323592385.572760857
     2426937.222      591690.028
#Sta/Elev= 30
       0 2089.34    9.582084.246    23.2 2078.87    42.2 2068.11    71.7 2068.51
    91.4 2060.62  138.022061.049   282.1 2061.81   302.3 2058.28   330.6 2063.06
     464 2061.84   545.2 2063.97   678.5 2059.16   807.9 2062.35   900.6 2061.47
   928.6    2063   962.9  2059.7 1047.172060.275  1073.3 2059.75 1083.93 2056.81
  1121.6 2055.27 1133.932056.592  1153.7 2057.88  1181.9 2065.22  1242.2 2106.07
  1258.7 2112.75  1314.5 2124.41  1354.8 2130.26  1439.2 2136.43  1516.4 2147.14
#Mann= 6 ,-1 , 0
       0     .05       0    9.58     .06       0  138.02     .05       0
 1047.17      .1       0 1083.93    .045       0 1133.93      .1       0
#XS Ineff= 2 ,-1
       0  929.45 2065.92  929.45 1041.28 2060.47
Permanent Ineff=
       F       F
Bank Sta=1083.93,1133.93
XS Rating Curve= 0 ,0
Exp/Cntr(USF)=0,0
Exp/Cntr=0.3,0.1

Type RM Length L Ch R = 1 ,18396   ,157.2,163.1,172
XS GIS Cut Line= 3
2426910.92090307593231.1185106072427037.88798858592994.754235854
     2427170.491      591678.011
#Sta/Elev= 30
       0  2089.3    27.7 2077.44    44.7  2066.4    68.6 2065.59    77.9 2060.25
    86.9 2058.31  139.19 2058.53   356.8 2059.16   421.1 2062.28   474.8  2059.5
   573.8 2062.08   638.1 2058.72   730.8 2057.12   867.3 2061.28 1031.422060.237
  1116.5 2056.18  1152.7 2058.79 1176.01 2052.77  1188.9 2051.53 1212.512052.901
    1221  2053.7    1225 2056.56  1253.2 2088.85  1277.3 2112.78  1289.3 2129.18
  1293.4 2132.07  1329.7  2144.2  1405.9 2164.43  1555.8 2225.27  1591.7 2237.58
#Mann= 5 ,-1 , 0
       0     .06       0  139.19     .05       0 1031.42      .1       0
 1176.01    .045       0 1212.51      .1       0
#XS Ineff= 2 ,-1
       0 1043.62 2063.68 1043.62 1145.97 2057.78
Permanent Ineff=
       F       F
Bank Sta=1176.01,1212.51
XS Rating Curve= 0 ,0
Exp/Cntr(USF)=0,0
Exp/Cntr=0.3,0.1

Type RM Length L Ch R = 1 ,18233   ,106.4,110.6,115.3
XS GIS Cut Line= 4
2426952.71785841593269.5556188932427084.09699671593002.455737208
2427134.15675551592478.753645122     2427443.195      591751.034
#Sta/Elev= 30
       0 2081.88    37.5 2064.79    61.9 2064.28    78.9 2057.68   85.522056.843
   389.8 2058.24   450.1 2060.01   530.4 2058.63   550.6 2060.22   638.9 2060.44
   703.2 2056.01   867.9 2059.16   954.1 2059.17 1088.462054.744  1114.8 2052.98
  1172.9  2052.6 1188.082050.654  1197.4 2048.54  1214.8 2047.93 1236.482050.216
  1245.2 2054.95  1271.3 2074.12  1276.6 2080.31    1289  2100.3  1328.4 2139.97
  1397.3  2173.8  1479.8 2220.37  1527.6 2243.83  1549.4 2252.74  1614.4 2286.43
#Mann= 5 ,-1 , 0
       0     .06       0   85.52     .05       0 1088.46      .1       0
 1188.08    .045       0 1236.48      .1       0
Bank Sta=1188.08,1236.48
XS Rating Curve= 0 ,0
Exp/Cntr(USF)=0,0
Exp/Cntr=0.3,0.1

Type RM Length L Ch R = 1 ,18123   ,175.6,192.5,197.8
XS GIS Cut Line= 4
2427009.83017243 593302.423119172427153.41050889593002.455737208
2427172.66426228592509.559650539     2427598.563      591831.467
#Sta/Elev= 30
       0 2068.59    19.4  2063.3      44 2062.55    61.4 2056.49   76.312055.314
   500.3 2059.25   556.4 2057.14   584.4 2060.27   676.5 2058.68   732.5 2054.56
   808.6 2057.38   937.6    2058 1067.192055.751  1126.2  2050.6 1139.772052.741
  1154.1 2053.83 1183.292047.841  1195.8 2046.05 1239.992048.417  1249.4 2052.38
  1253.3 2056.21  1268.4 2077.81  1277.8 2096.56  1294.4 2111.08    1336 2130.97
  1433.8 2169.28  1485.6 2194.22    1509 2206.54  1590.3  2258.4  1626.6 2278.81
#Mann= 6 ,-1 , 0
       0     .06       0   76.31     .05       0 1067.19      .1       0
 1139.77     .05       0 1183.29    .045       0 1239.99      .1       0
Bank Sta=1183.29,1239.99
XS Rating Curve= 0 ,0
Exp/Cntr(USF)=0,0
Exp/Cntr=0.3,0.1

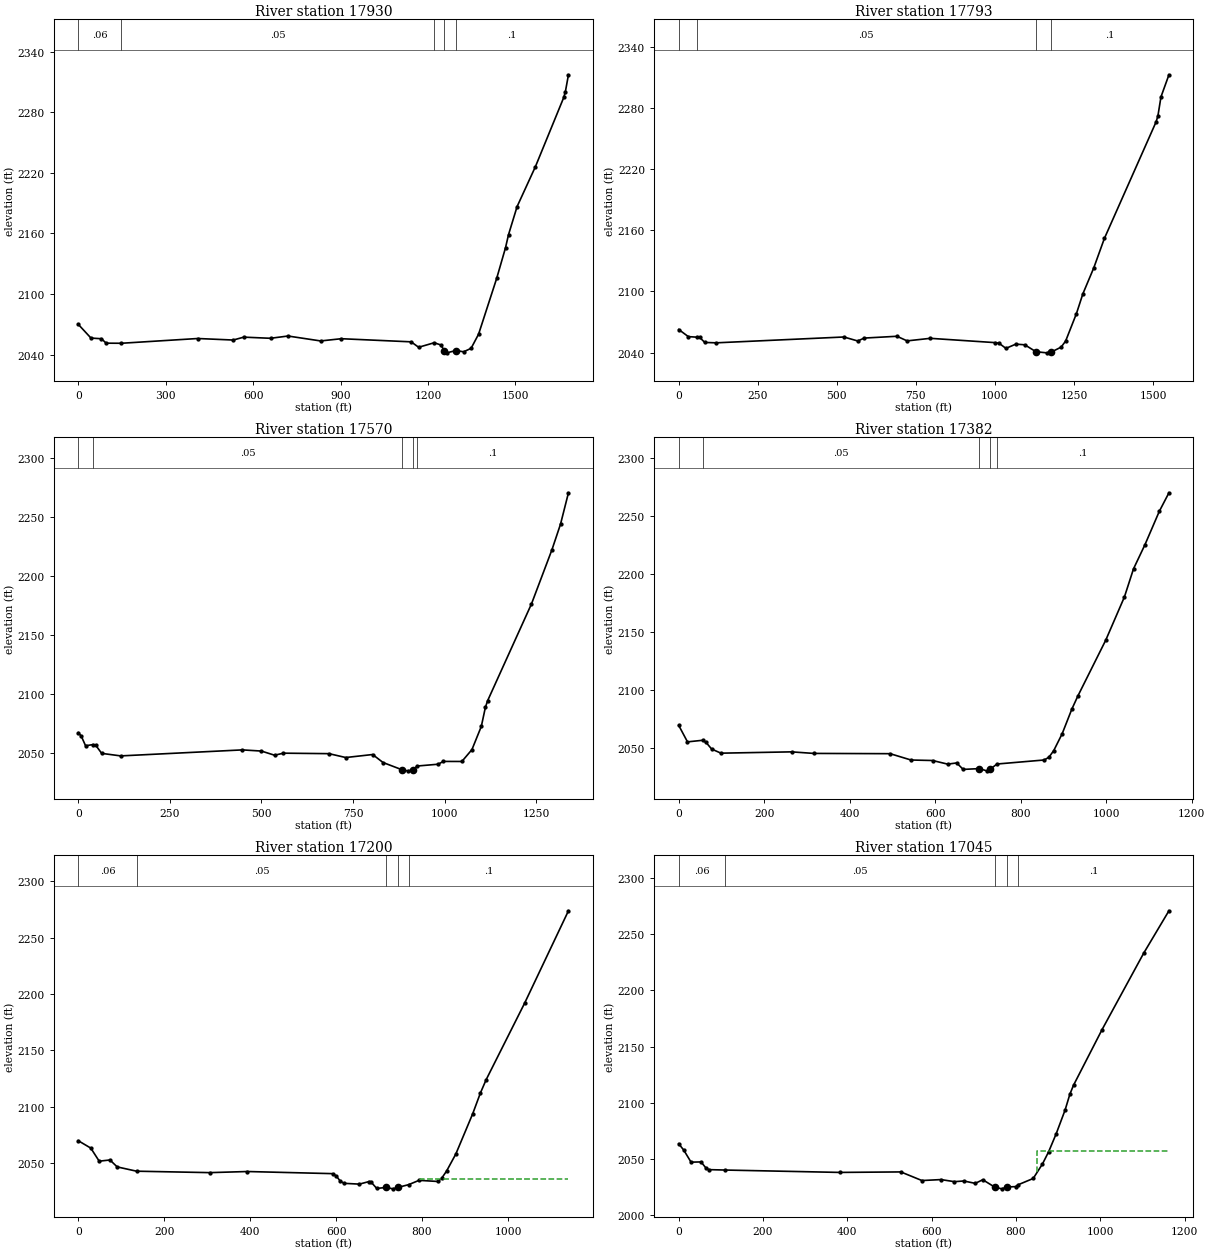
Type RM Length L Ch R = 1 ,17930   ,136.3,137.4,138.8
XS GIS Cut Line= 3
2427206.51283271593454.4360777672427215.02251973592544.216406633
2427816.28995777592060.364134543
#Sta/Elev= 30
       0 2070.11    43.7 2056.49    79.7 2055.84    95.7 2051.45   147.8 2051.35
     410 2056.06   531.7 2054.55   567.9 2057.41   659.7 2056.28   719.7 2058.52
   831.7 2053.65   902.6 2055.86  1142.2 2052.77    1168 2047.39 1221.312051.857
  1244.3 2049.67 1256.222043.901  1264.7 2041.88 1296.022044.171  1322.3 2042.91
  1347.9 2046.34  1373.6 2060.32  1435.7 2115.54    1466 2145.85  1476.3  2158.8
  1505.8 2186.63  1568.7 2226.17  1665.8 2294.56  1671.4 2300.26    1682 2317.04
#Mann= 5 ,-1 , 0
       0     .06       0   147.8     .05       0 1221.31      .1       0
 1256.22    .045       0 1296.02      .1       0
Bank Sta=1256.22,1296.02
XS Rating Curve= 0 ,0
Exp/Cntr(USF)=0,0
Exp/Cntr=0.3,0.1

Type RM Length L Ch R = 1 ,17793   ,221.1,222.9,229.8
XS GIS Cut Line= 3
2427320.78201354593445.1091354212427322.84353869 592613.52991882
     2427904.303      592190.756
#Sta/Elev= 30
       0 2062.62    30.4 2055.64   57.332055.102    66.4 2054.81    82.4 2049.92
   118.4 2049.55   522.4 2055.27   566.4 2051.35   586.4 2054.21   690.3 2055.98
   722.3 2051.46   795.6 2053.96  1001.2 2049.74  1013.1 2049.17  1034.8 2044.11
  1066.3 2048.28  1094.7  2047.6 1129.692040.842  1163.7 2039.73 1177.992040.428
  1209.5 2045.35  1223.7 2051.27  1257.9  2078.2  1278.3 2097.64  1312.7 2123.04
  1346.3 2151.94  1509.6 2266.09  1515.5 2271.92  1525.3 2290.79  1550.5 2312.47
#Mann= 4 ,-1 , 0
       0     .06       0   57.33     .05       0 1129.69    .045       0
 1177.99      .1       0
Bank Sta=1129.69,1177.99
XS Rating Curve= 0 ,0
Exp/Cntr(USF)=0,0
Exp/Cntr=0.3,0.1

Type RM Length L Ch R = 1 ,17570   ,200.3,187.4,175.6
XS GIS Cut Line= 4
2427483.78376071593402.6981543532427469.17206442592744.455441842
2427805.79227816592555.8638607392428006.69420845592341.018197889
#Sta/Elev= 30
       0 2067.29       8 2064.57      20 2056.24   40.092057.211      48 2056.54
      64 2049.77     116 2047.63   448.1 2052.72   500.1 2051.73     536  2048.2
   560.1 2049.94   684.6 2049.53   730.4 2046.25   803.8  2048.8   832.1 2042.03
     885 2035.77   899.2 2034.97   914.4 2035.53  924.792039.035   982.6 2040.58
   996.7 2042.95  1047.4 2042.91  1074.9 2052.97  1100.5 2072.64  1111.6 2088.76
  1117.7  2094.4  1237.4  2176.4  1293.4  2222.4  1316.8 2244.09  1338.4 2270.61
#Mann= 5 ,-1 , 0
       0     .06       0   40.09     .05       0     885    .045       0
   914.4     .05       0  924.79      .1       0
Bank Sta=885,914.4
XS Rating Curve= 0 ,0
Exp/Cntr(USF)=0,0
Exp/Cntr=0.3,0.1

Type RM Length L Ch R = 1 ,17382   ,181.7,182.8,183.8
XS GIS Cut Line= 3
2427542.72981754593401.620865484 2427875.7807584592614.801528308
2428083.99362534592409.692208446
#Sta/Elev= 30
       0  2069.8    20.5 2055.67   56.142057.039      64 2055.17      77 2049.51
    98.7 2045.95   263.8 2047.08   315.9 2045.74   494.5 2045.51   543.3 2040.07
   593.8 2039.64   629.1 2036.53   650.3 2037.55   665.4 2031.99  703.482032.682
   720.3 2030.76  728.482032.144  744.472036.624   854.7 2040.08   865.9 2042.41
   877.2 2048.15     897 2062.71   919.6 2083.85   933.7 2095.14   998.8 2143.05
  1042.5  2180.2  1063.8 2204.42  1090.5 2225.11  1124.1 2253.83  1146.7 2269.82
#Mann= 5 ,-1 , 0
       0     .06       0   56.14     .05       0  703.48    .045       0
  728.48     .05       0  744.47      .1       0
Bank Sta=703.48,728.48
XS Rating Curve= 0 ,0
Exp/Cntr(USF)=0,0
Exp/Cntr=0.3,0.1

Type RM Length L Ch R = 1 ,17200   ,159,154.6,149.4
XS GIS Cut Line= 2
2427660.64822224593476.819799429     2428168.638      592455.311
#Sta/Elev= 30
       0 2070.02    29.2 2063.45    48.8 2051.87    73.8 2052.95    90.6 2046.81
  135.772042.999   306.1 2041.73   393.7 2042.71     592 2040.83   600.7 2038.65
   609.9 2034.12   618.8 2032.24   654.2 2031.55   676.9 2033.83   681.3 2033.41
   694.7 2027.72  717.032028.656     732 2027.37  743.732028.616  768.952031.075
     793 2034.89   836.4  2033.9   845.4 2036.55   857.3 2043.21   878.8 2058.32
   918.1    2094   935.9 2112.29   949.3 2124.09  1038.7 2191.78  1140.8 2273.69
#Mann= 5 ,-1 , 0
       0     .06       0  135.77     .05       0  717.03    .045       0
  743.73     .05       0  768.95      .1       0
#XS Ineff= 2 , 0
                           795.8         2036.21
Permanent Ineff=
       F       F
Bank Sta=717.03,743.73
XS Rating Curve= 0 ,0
Exp/Cntr(USF)=0,0
Exp/Cntr=0.3,0.1

Type RM Length L Ch R = 1 ,17045   ,162.9,168.7,175.4
XS GIS Cut Line= 4
2427787.47378222593553.563801457 2428121.6636124592916.905640308
 2428148.3674709592791.6145310152428328.72391825592532.572063346
#Sta/Elev= 30
       0 2063.51    12.3 2057.63    29.2 2047.12    52.9 2047.33    64.7 2041.88
      71 2040.47  109.15 2040.11   381.7 2037.99   526.8 2038.43   576.9 2030.76
   622.1 2031.62   653.7 2029.77   676.3 2030.36   703.4 2028.26   721.2 2031.47
  749.092025.024   766.2 2023.38  778.492025.049   798.9 2025.35  804.682026.939
   840.8  2032.6   862.8  2045.5   877.4 2056.33   895.4 2072.41   916.4 2093.42
   927.9 2107.66   936.5 2115.59  1004.1 2164.99  1103.1 2233.15  1162.8 2270.74
#Mann= 5 ,-1 , 0
       0     .06       0  109.15     .05       0  749.09    .045       0
  778.49     .05       0  804.68      .1       0
#XS Ineff= 2 , 0
          720.42 2028.89   849.9         2057.15
Permanent Ineff=
       F       F
Bank Sta=749.09,778.49
XS Rating Curve= 0 ,0
Exp/Cntr(USF)=0,0
Exp/Cntr=0.3,0.1

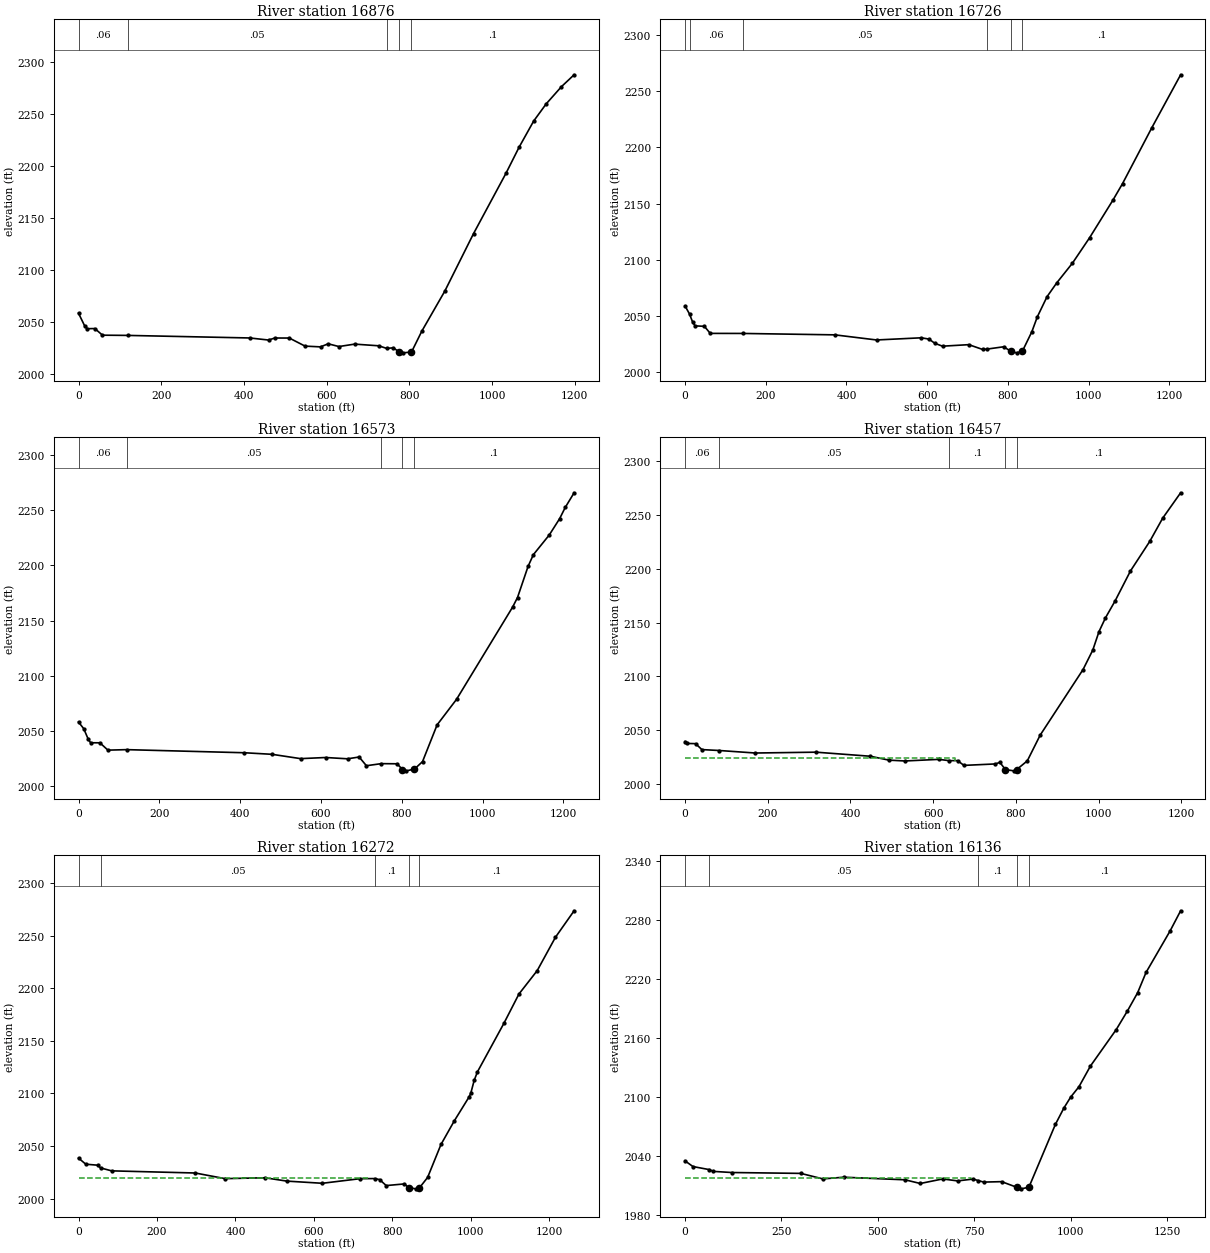
Type RM Length L Ch R = 1 ,16876   ,149,149.9,151.1
XS GIS Cut Line= 2
 2427889.1319675593620.825558231     2428491.128      592584.323
#Sta/Elev= 30
       0 2058.66    15.3 2046.14      21 2043.79    39.5 2043.91      58 2037.53
  118.712037.316   414.1 2034.85   459.6 2032.86   474.7 2034.81   509.8 2034.78
   547.9 2027.01   585.3 2026.28   603.8 2029.24   629.8  2026.6   667.8 2028.93
   726.3 2027.31  745.15 2024.81     761 2025.36  774.922021.706   784.1 2020.54
  805.332021.289   830.4 2041.48   885.9 2079.95   955.3 2135.23  1033.9 2193.39
  1065.7 2218.55  1100.8 2243.59    1131  2260.1    1168  2276.7  1198.6 2288.13
#Mann= 5 ,-1 , 0
       0     .06       0  118.71     .05       0  745.15      .1       0
  774.92    .045       0  805.33      .1       0
#XS Ineff= 2 , 0
          722.57 2025.98
Permanent Ineff=
       F       F
Bank Sta=774.92,805.33
XS Rating Curve= 0 ,0
Exp/Cntr(USF)=0,0
Exp/Cntr=0.3,0.1

Type RM Length L Ch R = 1 ,16726   ,152.9,154,155.6
XS GIS Cut Line= 2
 2427965.7162114593690.813810262     2428643.364      592666.696
#Sta/Elev= 30
       0 2059.14   11.242051.806    18.5 2045.03    24.8 2041.38    47.9 2040.99
    62.5  2034.7  143.152034.653   371.1  2033.4   474.6 2028.85   585.3 2030.78
   604.5 2029.64   618.8  2025.9     638 2023.33   703.1 2024.68   737.7 2020.38
  748.272020.748   789.6  2022.8  807.012018.838   821.4 2017.41  835.812018.806
   859.3 2036.13     873 2049.49     897 2067.34     921  2079.6   959.9 2097.12
  1002.5 2119.77  1060.1 2153.08    1084 2167.82  1156.5 2217.44    1228 2264.58
#Mann= 6 ,-1 , 0
       0      .1       0   11.24     .06       0  143.15     .05       0
  748.27      .1       0  807.01    .045       0  835.81      .1       0
Bank Sta=807.01,835.81
XS Rating Curve= 0 ,0
Exp/Cntr(USF)=0,0
Exp/Cntr=0.3,0.1

Type RM Length L Ch R = 1 ,16573   ,115.3,115.5,115.8
XS GIS Cut Line= 2
2428037.51721141593754.363560939     2428785.277      592781.941
#Sta/Elev= 30
       0 2058.02    12.9 2052.02    24.3 2042.27      30 2039.23    52.9 2039.21
    72.8 2032.56  119.072033.011   410.8 2030.19   478.9 2028.78   549.6 2024.86
   611.9 2025.88   666.1 2024.71   694.6 2026.33   712.6 2018.43   749.52020.326
   788.7 2020.19  801.792014.985   811.5  2013.8  831.492015.377   851.5 2022.17
   887.6 2055.46   935.7  2078.6  1074.3 2162.07  1086.6 2170.84  1112.8 2199.13
  1125.9 2209.72  1165.2 2227.53  1190.9 2242.33  1204.7 2252.47  1226.7 2265.78
#Mann= 5 ,-1 , 0
       0     .06       0  119.07     .05       0   749.5      .1       0
  801.79    .045       0  831.49      .1       0
Bank Sta=801.79,831.49
XS Rating Curve= 0 ,0
Exp/Cntr(USF)=0,0
Exp/Cntr=0.3,0.1

Type RM Length L Ch R = 1 ,16457   ,192.1,185.2,176.9
XS GIS Cut Line= 2
2428133.25395937593798.537552814     2428878.609      592860.496
#Sta/Elev= 30
       0 2039.44     4.7 2037.64    25.4 2037.46    40.7 2031.93   83.022031.085
   169.8 2028.75   316.6 2029.53   447.9 2025.75   492.9 2022.12   531.5 2021.35
   613.8 2022.85  638.612021.631   658.8 2021.69   674.2 2017.25   750.5  2018.6
     761 2020.08  774.66 2013.31   795.1 2012.18   801.7 2013.35   827.4 2021.45
   858.6 2045.42   962.2 2106.35   985.8  2124.5  1000.8 2141.67  1016.4 2154.42
  1039.4 2169.94  1076.8 2197.98  1123.4 2225.45  1154.7 2247.06  1198.1 2270.67
#Mann= 5 ,-1 , 0
       0     .06       0   83.02     .05       0  638.61      .1       0
  774.66    .045       0   801.7      .1       0
#XS Ineff= 2 , 0
           652.6 2024.41
Permanent Ineff=
       F       F
Bank Sta=774.66,801.7
XS Rating Curve= 0 ,0
Exp/Cntr(USF)=0,0
Exp/Cntr=0.3,0.1

Type RM Length L Ch R = 1 ,16272   ,130.4,136,141.8
XS GIS Cut Line= 3
2428301.87731702593965.1942374032428735.93426977593409.713108895
     2428917.662       592881.87
#Sta/Elev= 30
       0  2038.6    18.5 2032.77    48.9 2031.81   56.222029.223    84.5 2026.44
   297.6  2024.4   373.6 2019.03   475.3 2019.87   531.1 2016.69   621.6 2014.63
     717 2018.98  754.542019.116   767.4 2018.15   784.3 2012.45   830.8 2014.03
  841.34 2010.47   860.4 2009.35   868.9 2010.27   889.8 2020.18   923.9 2051.51
   957.7 2073.86   995.8 2096.85    1000 2100.39  1008.5 2112.42  1016.9 2120.57
  1084.1  2166.5  1122.6 2194.47  1169.2 2216.73  1215.7 2248.43  1263.2 2273.56
#Mann= 5 ,-1 , 0
       0     .06       0   56.22     .05       0  754.54      .1       0
  841.34    .045       0   868.9      .1       0
#XS Ineff= 2 , 0
          741.35 2019.78
Permanent Ineff=
       F       F
Bank Sta=841.34,868.9
XS Rating Curve= 0 ,0
Exp/Cntr(USF)=0,0
Exp/Cntr=0.3,0.1

Type RM Length L Ch R = 1 ,16136   ,144.7,147,149.1
XS GIS Cut Line= 2
2428411.48595396 594054.80306771     2429134.561      592992.804
#Sta/Elev= 30
       0 2035.26    20.6 2029.46   63.392026.332    72.8 2024.57   121.3 2023.41
   300.2 2022.52   357.4 2016.92   411.5 2018.64   570.4 2015.99   609.9 2012.25
   667.9 2016.87   706.6 2014.88   746.9 2016.76  760.312015.179   774.4 2013.67
   820.8 2014.12   861.1 2008.23   871.2 2006.81  891.45 2008.43   960.1 2072.34
     982 2088.91   999.7 2100.11  1021.2 2110.65  1051.1 2131.79  1117.9 2168.82
    1147 2187.83  1173.3 2206.26  1195.1 2226.88  1257.5 2269.14  1284.8 2289.62
#Mann= 5 ,-1 , 0
       0     .06       0   63.39     .05       0  760.31      .1       0
   861.1    .045       0  891.45      .1       0
#XS Ineff= 2 , 0
          740.25 2017.58
Permanent Ineff=
       F       F
Bank Sta=861.1,891.45
XS Rating Curve= 0 ,0
Exp/Cntr(USF)=0,0
Exp/Cntr=0.3,0.1