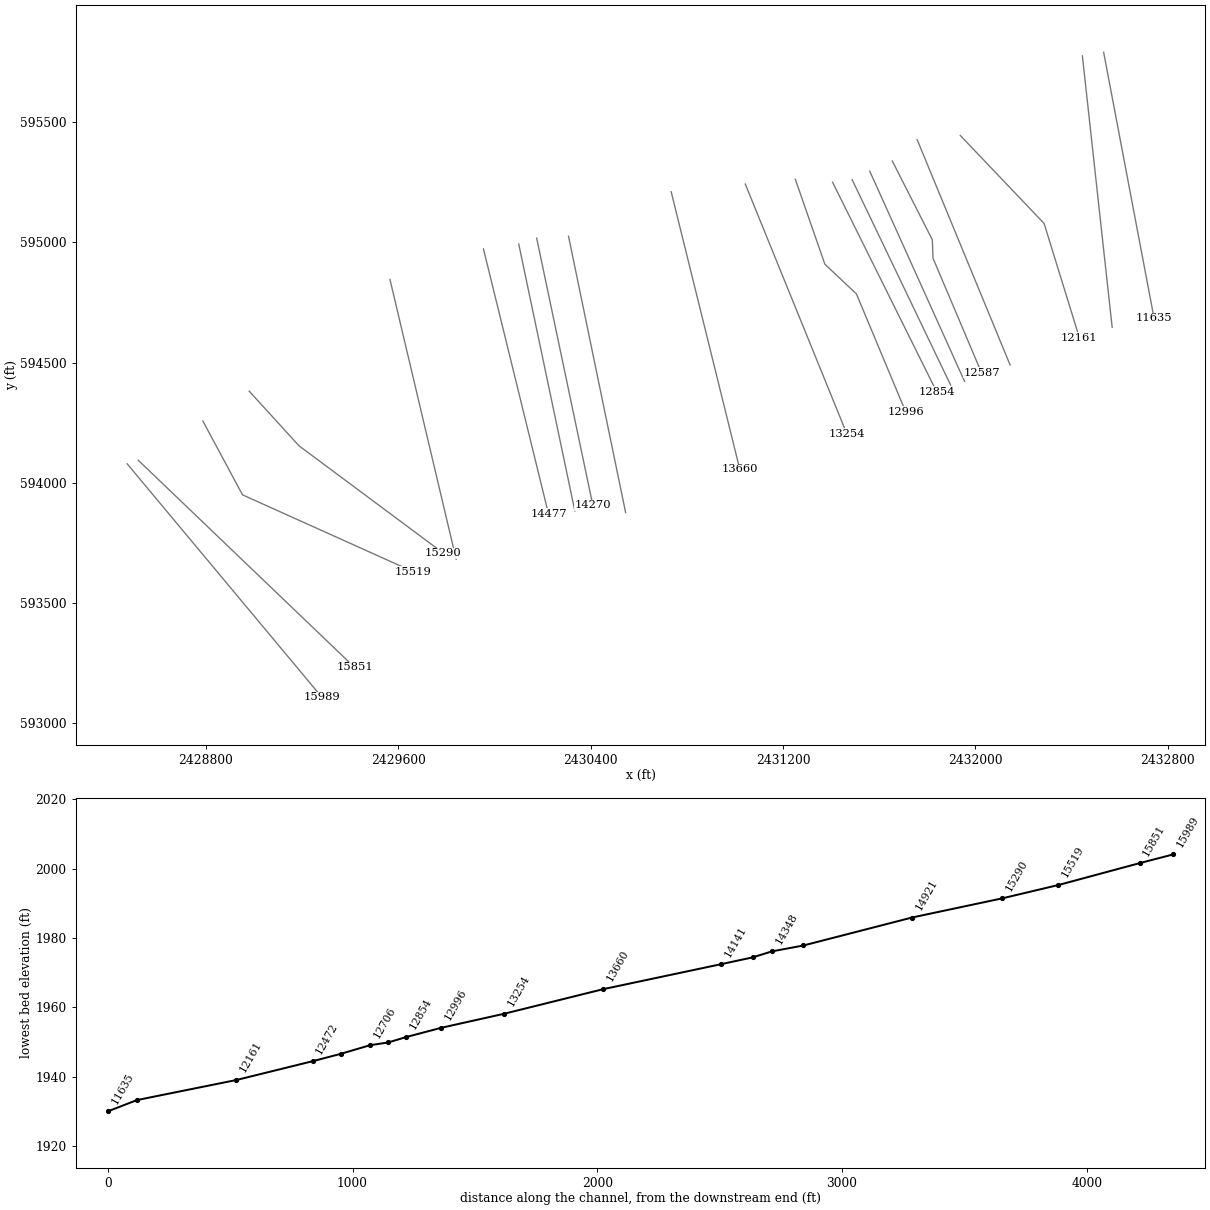
HEC-RAS study SMITHCK.prj: SMITHCK

--- SMITHCK.g01 (geometry) --- (continued)

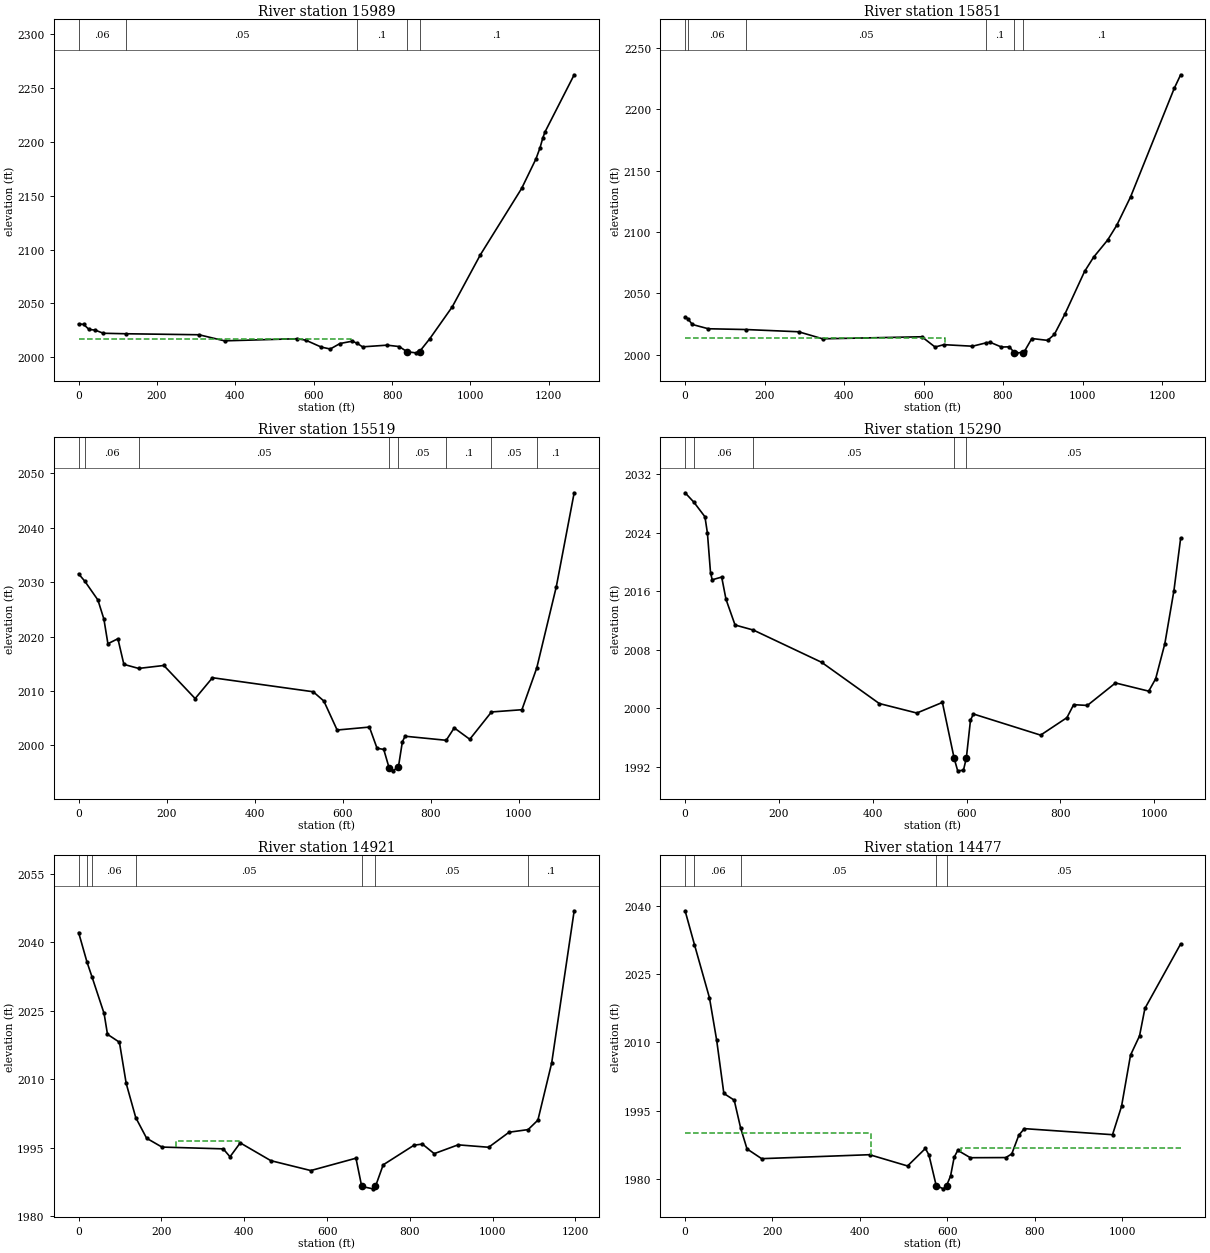
Type RM Length L Ch R = 1 ,15989   ,136.9,138.4,140.4
XS GIS Cut Line= 2
2428471.73544989594079.029810262     2429281.735      593107.738
#Sta/Elev= 30
       0 2031.05    12.7 2030.51    26.6 2025.87    42.2 2025.26      63 2022.33
  120.342021.872   307.1 2020.95   372.4 2015.29   557.8 2017.26   579.7 2015.91
   619.5 2009.47   642.2 2007.73   667.1 2012.82   698.4 2014.98  710.922012.996
   724.5 2009.73   787.1 2011.29   818.2    2010  838.112005.228   859.8 2004.17
  870.212005.394   896.3 2017.32   953.6 2046.88  1025.5 2095.25  1130.6 2156.66
  1167.1 2184.03  1177.5 2194.31  1184.6 2203.44  1190.2 2209.05  1264.7  2262.1
#Mann= 5 ,-1 , 0
       0     .06       0  120.34     .05       0  710.92      .1       0
  838.11    .045       0  870.21      .1       0
#XS Ineff= 2 , 0
          696.05  2016.8
Permanent Ineff=
       F       F
Bank Sta=838.11,870.21
XS Rating Curve= 0 ,0
Exp/Cntr(USF)=0,0
Exp/Cntr=0.3,0.1

Type RM Length L Ch R = 1 ,15851   ,326.5,331.3,336.9
XS GIS Cut Line= 2
2428517.68719515 594094.04705146     2429418.003      593231.528
#Sta/Elev= 30
       0 2030.54    6.73 2029.49    18.1 2024.71    58.4 2021.23  153.582020.594
   285.5 2018.78   346.1 2013.04   595.7 2014.71   628.9 2006.36   651.1 2008.28
   723.1 2007.02  756.592009.707   767.4 2010.24     796 2006.35   815.8 2006.53
   828.3 2001.78   831.7 2001.63     849 2001.85   854.8  2003.4   872.4 2013.28
     912 2011.78     929 2016.56   955.7 2033.21  1005.1 2067.86  1027.7 2079.42
    1063 2093.36  1086.1 2105.43  1120.8 2128.51  1230.6 2216.78  1246.8  2227.9
#Mann= 6 ,-1 , 0
       0      .1       0    6.73     .06       0  153.58     .05       0
  756.59      .1       0   828.3    .045       0     849      .1       0
#XS Ineff= 2 , 0
          654.85 2013.99
Permanent Ineff=
       F       F
Bank Sta=828.3,849
XS Rating Curve= 0 ,0
Exp/Cntr(USF)=0,0
Exp/Cntr=0.3,0.1

Type RM Length L Ch R = 1 ,15519   ,232.7,229.6,225.8
XS GIS Cut Line= 3
2428786.55298104594257.153308908 2428951.7110751593949.740403776
     2429660.043      593630.751
#Sta/Elev= 30
       0 2031.52   14.092030.165    43.8 2026.72    57.4 2023.21    66.5 2018.69
    89.2  2019.6   102.8 2014.89  136.342014.146   193.6 2014.69   264.7 2008.61
   304.1 2012.44   532.9 2009.86   557.1 2008.16   587.3 2002.83   660.6 2003.37
   677.9 1999.49   693.2 1999.26  705.311995.889   713.2 1995.33  726.411995.993
   735.5 2000.67   741.6 2001.69   835.12000.943   853.3 2003.22   888.6 2001.13
  937.942006.148  1007.1 2006.56 1040.772014.227  1085.2 2029.16  1125.8 2046.42
#Mann= 8 ,-1 , 0
       0      .1       0   14.09     .06       0  136.34     .05       0
  705.31    .045       0  726.41     .05       0   835.1      .1       0
  937.94     .05       0 1040.77      .1       0
Bank Sta=705.31,726.41
XS Rating Curve= 0 ,0
Exp/Cntr(USF)=0,0
Exp/Cntr=0.3,0.1

Type RM Length L Ch R = 1 ,15290   ,380.7,368.5,353.5
XS GIS Cut Line= 3
2428979.32153867 594381.29612693 2429186.6068664594153.830189662
2429787.20248445593706.952283282
#Sta/Elev= 30
       0 2029.48    18.8 2028.19    42.3  2026.2    47.6 2023.97    54.2 2018.56
    57.8 2017.59      78 2017.96    87.2 2014.92   106.5 2011.41  145.612010.718
   291.1 2006.31   413.9 2000.68     494 1999.38   548.5 2000.83  573.481993.226
   581.1 1991.48   593.4 1991.56  599.581993.243   608.4  1998.4   614.6 1999.25
   757.9 1996.36     814 1998.75   828.3 2000.52   857.6 2000.42   917.5 2003.49
   988.4 2002.37  1003.2 2004.07  1022.7 2008.85  1042.1 2016.11  1056.4 2023.26
#Mann= 5 ,-1 , 0
       0      .1       0    18.8     .06       0  145.61     .05       0
  573.48    .045       0  599.58     .05       0
Bank Sta=573.48,599.58
XS Rating Curve= 0 ,0
Exp/Cntr(USF)=0,0
Exp/Cntr=0.3,0.1

Type RM Length L Ch R = 1 ,14921   ,441.8,444,445.7
XS GIS Cut Line= 2
2429564.87246275 594846.393644462429840.25851235593681.687508089
#Sta/Elev= 30
       0 2042.16   20.242035.676   32.692032.332    61.5 2024.41    69.7 2019.84
    98.5 2018.11   114.9 2009.06  137.982001.569   164.2 1997.05   201.2 1995.11
   349.2 1994.72   365.6 1992.98   390.3 1996.03   464.2 1992.13   560.7 1989.96
   669.8 1992.67  683.711986.468   710.9 1985.95  716.911986.482   735.5 1991.21
     810 1995.52   830.2 1995.77   858.8 1993.67   916.5  1995.6   990.3 1995.07
  1039.6 1998.37 1085.571998.943  1109.2 2001.02  1142.5 2013.56  1196.8 2046.94
#Mann= 7 ,-1 , 0
       0      .1       0   20.24     .05       0   32.69     .06       0
  137.98     .05       0  683.71    .045       0  716.91     .05       0
 1085.57      .1       0
#XS Ineff= 3 ,-1
       0   236.1 1991.35   236.1  388.44 1996.55  388.44  659.93 1991.35
Permanent Ineff=
       F       F       F
Bank Sta=683.71,716.91
XS Rating Curve= 0 ,0
Exp/Cntr(USF)=0,0
Exp/Cntr=0.3,0.1

Type RM Length L Ch R = 1 ,14477   ,129.3,128.8,128
XS GIS Cut Line= 2
2429953.95000072594972.7175204232430224.28309528593871.173322032
#Sta/Elev= 30
       0 2038.89   21.422031.462    55.8 2019.78    72.3 2010.47    88.7 1998.81
   112.4 1997.34  127.081991.246   141.7 1986.64   175.2  1984.5   422.3 1985.37
   509.2  1982.9     550 1986.74   558.2 1985.28  574.721978.597   591.2 1977.88
  598.521978.604   607.6  1980.7   615.9 1984.82   624.1 1986.33   652.9 1984.71
   734.1 1984.74   747.7 1985.55   763.8 1989.65   776.5 1991.09   978.3 1989.76
   998.9 1995.97  1019.5 2007.22  1040.1 2011.43  1052.4 2017.46  1134.2 2031.61
#Mann= 5 ,-1 , 0
       0      .1       0   21.42     .06       0  127.08     .05       0
  574.72    .045       0  598.52     .05       0
#XS Ineff= 2 , 0
           424.8 1990.16  630.69         1986.87
Permanent Ineff=
       F       F
Bank Sta=574.72,598.52
XS Rating Curve= 0 ,0
Exp/Cntr(USF)=0,0
Exp/Cntr=0.5,0.3

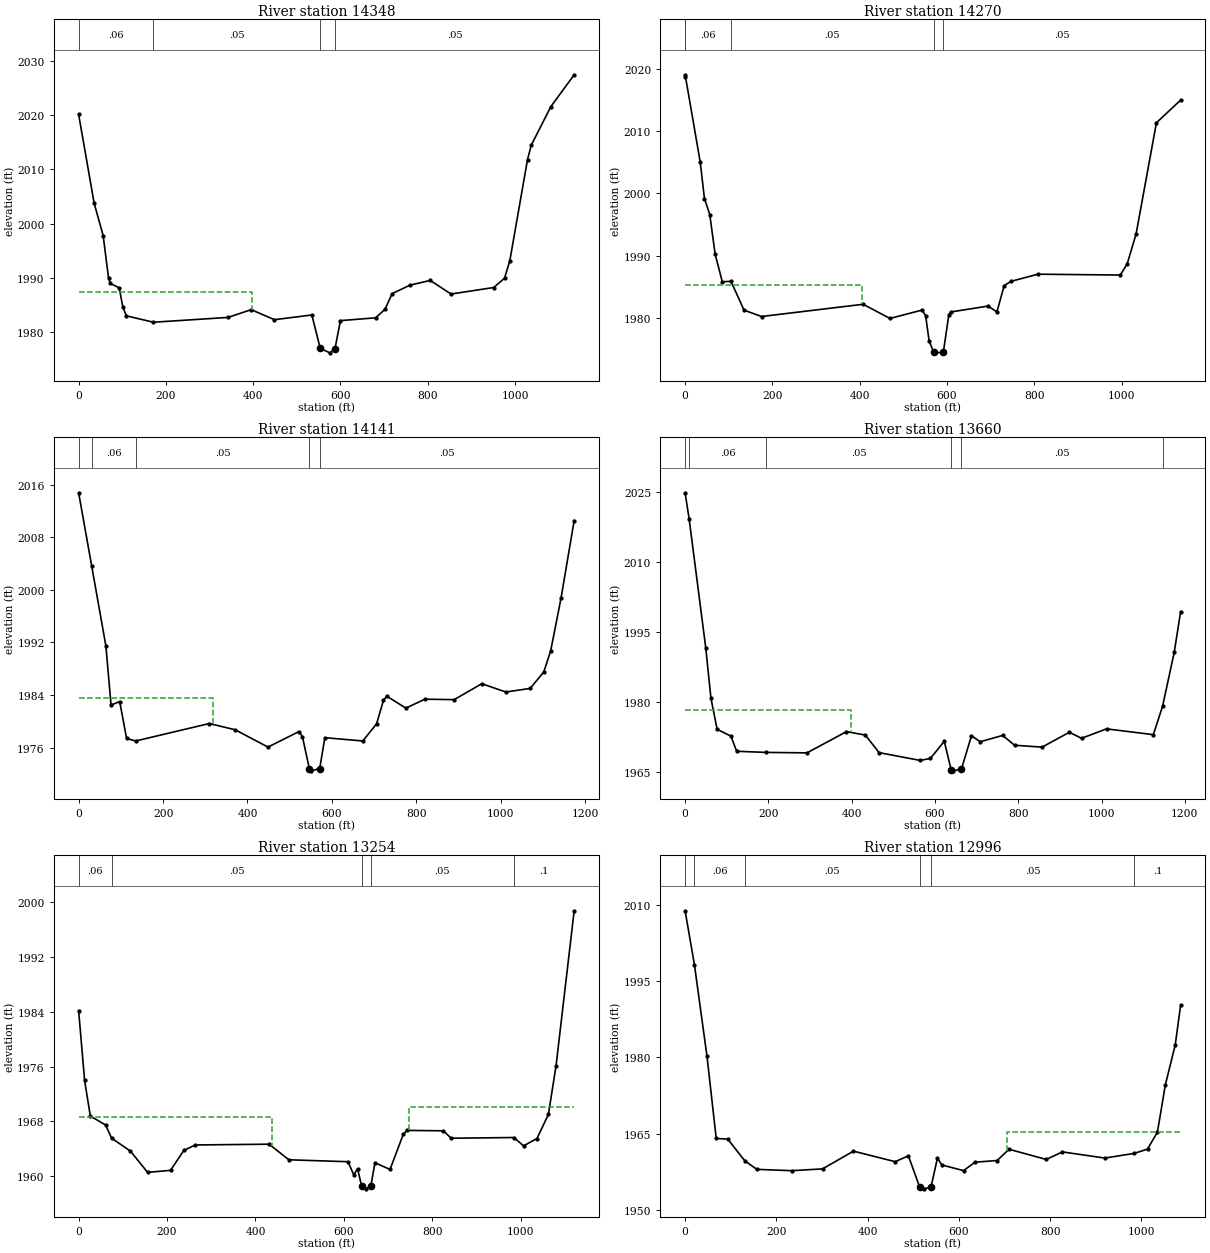
Type RM Length L Ch R = 1 ,14348   ,78.5,78.1,78.2
XS GIS Cut Line= 2
2430100.53092341594993.5593848232430334.03786789593882.448273733
#Sta/Elev= 30
       0 2020.13    35.6 2003.74    56.2 1997.79    68.5 1990.02    72.6 1988.97
      93 1988.16   101.2 1984.64   109.4    1983  171.471981.822   342.3 1982.71
   395.4 1984.14   448.6 1982.29   534.4 1983.16  553.491977.021   575.3 1976.18
  587.491976.978   599.8 1982.12   680.7 1982.64     702 1984.21   718.3 1987.09
   759.2 1988.66   805.6 1989.53   853.2 1987.02   950.9 1988.22   975.8 1989.93
   987.9 1993.14  1028.5  2011.8  1037.1 2014.47    1082 2021.57  1135.4 2027.44
#Mann= 4 ,-1 , 0
       0     .06       0  171.47     .05       0  553.49    .045       0
  587.49     .05       0
#XS Ineff= 2 , 0
          397.75  1987.4  603.09         1981.85
Permanent Ineff=
       F       F
Bank Sta=553.49,587.49
XS Rating Curve= 0 ,0
Exp/Cntr(USF)=0,0
Exp/Cntr=0.5,0.3

Type RM Length L Ch R = 1 ,14270   ,129.5,129.4,129.3
XS GIS Cut Line= 2
2430175.18370119595017.8649403782430408.69064567593906.753829289
#Sta/Elev= 30
       0    2019     .882018.689    34.7    2005    44.3 1999.18    56.5 1996.61
    68.8 1990.27    85.2 1985.85  105.141985.907     135  1981.3   175.1 1980.28
     408 1982.24   469.3 1979.97   542.9 1981.31   551.1 1980.42   559.2 1976.34
  569.491974.598   587.8 1974.46  591.891974.639   604.2 1980.55   608.3    1981
   694.1 1981.95   714.5 1981.01   730.9  1985.2   746.2  1985.9   808.5 1987.06
   997.1 1986.92  1012.9 1988.71  1033.3 1993.48  1079.9 2011.31  1135.4 2014.95
#Mann= 5 ,-1 , 0
       0      .1       0     .88     .06       0  105.14     .05       0
  569.49    .045       0  591.89     .05       0
#XS Ineff= 2 , 0
          405.86  1985.4
Permanent Ineff=
       F       F
Bank Sta=569.49,591.89
XS Rating Curve= 0 ,0
Exp/Cntr(USF)=0,0
Exp/Cntr=0.5,0.3

Type RM Length L Ch R = 1 ,14141   ,480.6,481.2,481.9
XS GIS Cut Line= 2
2430307.65685341595025.7735483272430545.14574022593876.226277071
#Sta/Elev= 30
       0 2014.75   30.932003.627    64.6 1991.45    76.8  1982.5    97.3 1983.01
   113.6 1977.42  135.061977.027   309.6 1979.68   370.9 1978.73   448.5  1976.1
     522 1978.46   530.2 1977.66  546.511972.819   551.1 1972.49  571.011972.843
   583.3 1977.53   673.1 1977.03   705.8 1979.64   722.1 1983.21   729.9 1983.84
   775.2 1982.02   820.1 1983.38   889.6 1983.31   954.9 1985.73  1012.1 1984.47
  1069.7 1985.02  1101.9 1987.53  1118.3 1990.77  1142.8 1998.78  1173.8 2010.53
#Mann= 5 ,-1 , 0
       0      .1       0   30.93     .06       0  135.06     .05       0
  546.51    .045       0  571.01     .05       0
#XS Ineff= 2 , 0
          317.93  1983.6
Permanent Ineff=
       F       F
Bank Sta=546.51,571.01
XS Rating Curve= 0 ,0
Exp/Cntr(USF)=0,0
Exp/Cntr=0.3,0.1

Type RM Length L Ch R = 1 ,13660   ,403.7,405.1,407.7
XS GIS Cut Line= 2
2430734.70944057595210.7110586432431020.12351384594055.606180937
#Sta/Elev= 30
       0 2024.85    9.69 2019.26    49.7 1991.55      62 1980.85    76.9 1974.18
     110 1972.73   123.8 1969.48  194.861969.239   292.7 1969.14   387.5 1973.69
   432.8 1972.95   465.8 1969.19   564.6 1967.52     589 1967.95   622.3 1971.62
  638.821965.499   642.9 1965.29  663.521965.653   687.5  1972.8   708.8 1971.53
   762.4 1972.87   791.2 1970.77   857.1 1970.37   922.6 1973.55   951.9 1972.26
  1011.8 1974.28  1124.2 1973.04 1146.391979.111  1174.4 1990.67  1189.8 1999.41
#Mann= 6 ,-1 , 0
       0      .1       0    9.69     .06       0  194.86     .05       0
  638.82    .045       0  663.52     .05       0 1146.39      .1       0
#XS Ineff= 2 , 0
          397.75 1978.34
Permanent Ineff=
       F       F
Bank Sta=638.82,663.52
XS Rating Curve= 0 ,0
Exp/Cntr(USF)=0,0
Exp/Cntr=0.3,0.1

Type RM Length L Ch R = 1 ,13254   ,252.3,258.2,265.9
XS GIS Cut Line= 2
2431042.86181151595243.0506149822431464.78355722594204.668354573
#Sta/Elev= 30
       0 1984.14    13.5 1973.98    26.5 1968.78      61 1967.49   74.561965.572
   117.2 1963.68     156 1960.59   207.8 1960.88     238 1963.79   263.9 1964.58
   430.8 1964.69   475.5 1962.42   609.3 1962.14   622.3 1960.23   630.9  1961.1
  640.011958.635   650.1 1958.19  661.021958.624   670.2 1961.99   704.3 1961.01
   734.5 1966.17   743.1  1966.7   825.2 1966.64   842.4 1965.56  984.281965.662
  1006.5 1964.45  1036.7 1965.52  1062.6 1969.04  1079.9 1976.15  1120.8 1998.68
#Mann= 5 ,-1 , 0
       0     .06       0   74.56     .05       0  640.01    .045       0
  661.02     .05       0  984.28      .1       0
#XS Ineff= 2 , 0
          436.98  1968.6  748.14          1970.1
Permanent Ineff=
       F       F
Bank Sta=640.01,661.02
XS Rating Curve= 0 ,0
Exp/Cntr(USF)=0,0
Exp/Cntr=0.3,0.1

Type RM Length L Ch R = 1 ,12996   ,147.5,142.4,136.7
XS GIS Cut Line= 4
2431251.00493794 595262.950889512431373.83036653594909.555582442
2431505.20719753594785.7581839992431709.85187659594295.621545265
#Sta/Elev= 30
       0 2008.79   20.431998.188      48 1980.15    68.2 1964.03    93.6 1963.89
  130.881959.624   157.1 1957.95   233.4 1957.69   301.1 1958.04   368.9 1961.53
   460.2 1959.46   489.3 1960.61   513.9 1954.46   524.3 1954.12   538.8 1954.47
   552.9 1960.16   562.5 1958.82   610.1  1957.7   635.3 1959.36   683.8 1959.69
   709.8  1961.9   791.3  1959.9   826.8 1961.38   919.7 1960.17  983.591961.082
  1013.2 1961.93  1034.9 1965.26  1052.2 1974.52  1073.9 1982.39  1085.8 1990.22
#Mann= 6 ,-1 , 0
       0      .1       0   20.43     .06       0  130.88     .05       0
   513.9    .045       0   538.8     .05       0  983.59      .1       0
#XS Ineff= 2 , 0
                           706.2         1965.36
Permanent Ineff=
       F       F
Bank Sta=513.9,538.8
XS Rating Curve= 0 ,0
Exp/Cntr(USF)=0,0
Exp/Cntr=0.3,0.1

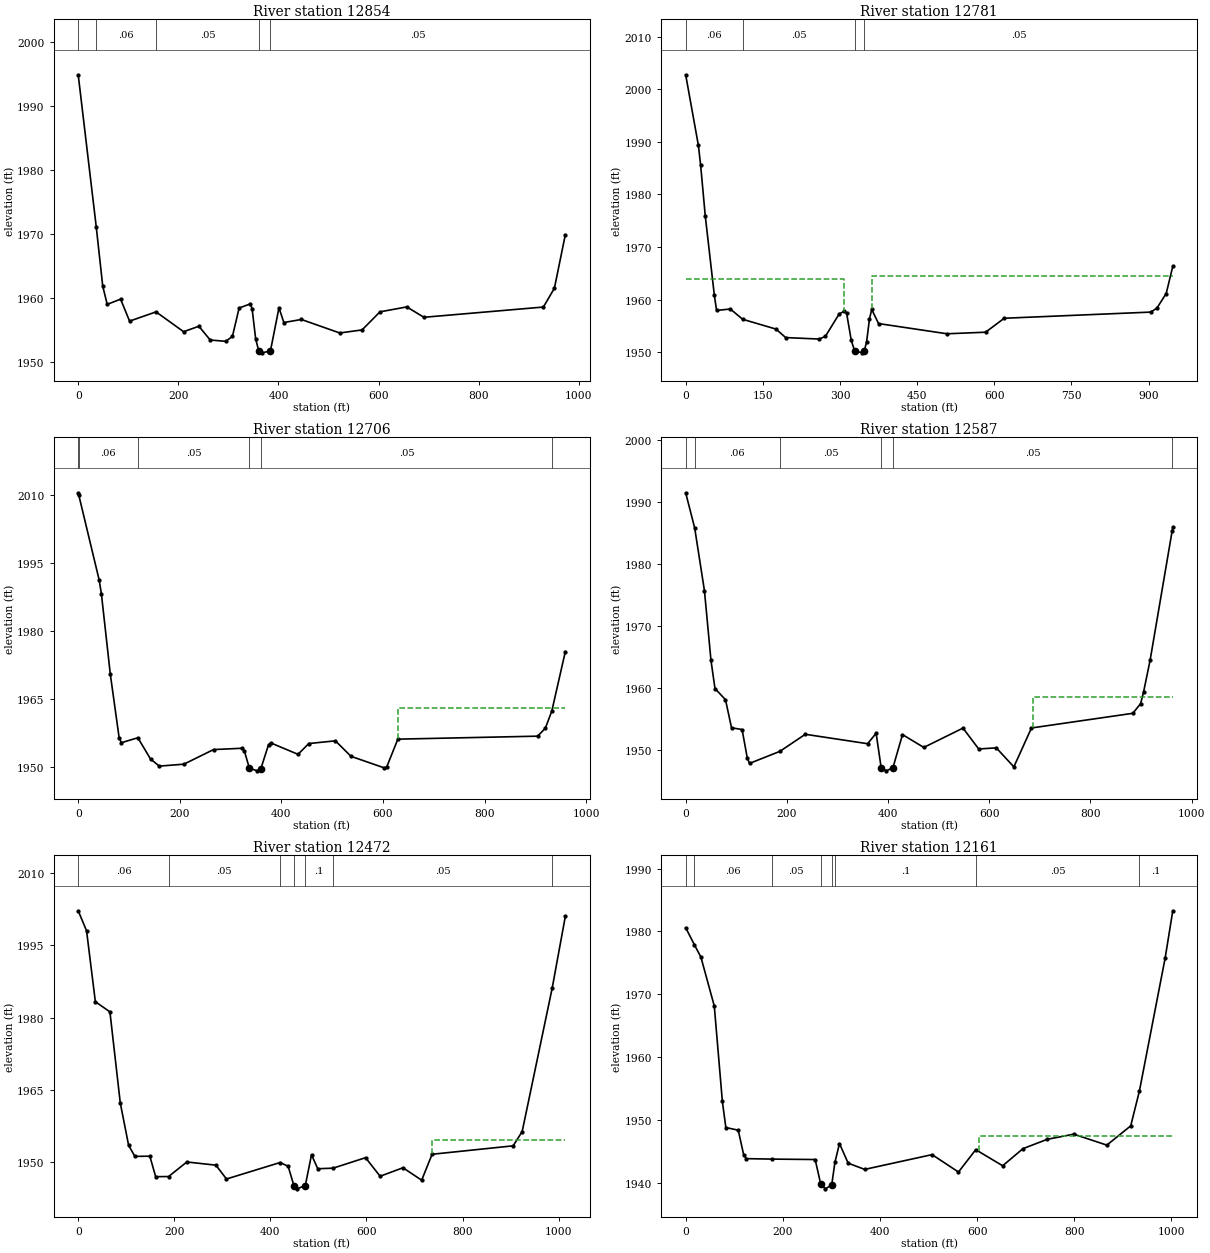
Type RM Length L Ch R = 1 ,12854   ,73.6,73.1,73.1
XS GIS Cut Line= 2
2431405.93626365 595250.396388322431838.70223007  594378.9953034
#Sta/Elev= 30
       0 1994.87   36.021971.129      49 1961.87    57.9 1959.03    84.7 1959.84
   102.6 1956.41  155.431957.855   210.5 1954.76     241 1955.61   263.7 1953.46
   294.6 1953.26     308 1954.02   321.4 1958.46   343.7  1959.1   347.3 1958.37
   354.4 1953.65   360.6 1951.76   366.1 1951.46   383.9 1951.74     401  1958.5
   410.7 1956.19   445.7 1956.67   522.4 1954.56     567 1955.04   602.7 1957.86
   656.3 1958.63   690.4 1957.01   929.1 1958.61   951.1 1961.55   972.9 1969.89
#Mann= 5 ,-1 , 0
       0      .1       0   36.02     .06       0  155.43     .05       0
   360.6    .045       0   383.9     .05       0
Bank Sta=360.6,383.9
XS Rating Curve= 0 ,0
Exp/Cntr(USF)=0,0
Exp/Cntr=0.5,0.3

Type RM Length L Ch R = 1 ,12781   ,74.9,74.7,74.9
XS GIS Cut Line= 2
 2431487.5218549595260.7359576162431896.81121301594406.786556112
#Sta/Elev= 30
       0 2002.73    24.7 1989.32    29.1 1985.54      38 1975.99    55.7 1960.87
    60.1 1957.96    86.8 1958.24  110.751956.285   175.6 1954.42   194.4 1952.81
   259.7 1952.53   271.6 1953.04   298.5 1957.31   308.5 1957.82   312.9 1957.43
   321.8 1952.34   328.3 1950.31   343.5 1949.91   347.21950.256   351.8 1952.03
   357.3 1956.34   361.7 1958.15     375 1955.47   508.1 1953.53   583.1 1953.83
   619.3 1956.48   904.2 1957.65   916.1  1958.4   934.2 1961.18     947 1966.33
#Mann= 4 ,-1 , 0
       0     .06       0  110.75     .05       0   328.3    .045       0
   347.2     .05       0
#XS Ineff= 2 , 0
          307.29    1964  361.72         1964.57
Permanent Ineff=
       F       F
Bank Sta=328.3,347.2
XS Rating Curve= 0 ,0
Exp/Cntr(USF)=0,0
Exp/Cntr=0.5,0.3

Type RM Length L Ch R = 1 ,12706   ,126.1,119.4,111.9
XS GIS Cut Line= 2
2431560.78970296595296.1066428862431954.92019596594421.945421228
#Sta/Elev= 30
       0 2010.45     .99 2010.01    41.3 1991.18    45.6 1988.19    63.2 1970.42
    80.7  1956.3    85.1 1955.32  117.411956.409   142.4 1951.71   159.7 1950.15
     208 1950.58   266.4  1953.8     322 1954.09   326.9 1953.57  336.96 1949.68
   352.8 1949.11  359.66 1949.61   374.7 1954.89   379.1 1955.27   432.7 1952.75
   453.9 1955.13   506.3 1955.73     537 1952.31   602.8 1949.75   607.2 1949.93
   629.2  1956.1   904.4 1956.76   919.6 1958.51  932.371962.326   958.9 1975.41
#Mann= 6 ,-1 , 0
       0      .1       0     .99     .06       0  117.41     .05       0
  336.96    .045       0  359.66     .05       0  932.37      .1       0
#XS Ineff= 2 , 0
                          630.21         1962.88
Permanent Ineff=
       F       F
Bank Sta=336.96,359.66
XS Rating Curve= 0 ,0
Exp/Cntr(USF)=0,0
Exp/Cntr=0.5,0.3

Type RM Length L Ch R = 1 ,12587   ,109.3,114.8,120.8
XS GIS Cut Line= 4
2431654.26937117595339.0567607132431821.01688744595010.614683211
2431823.54336496594934.820357634 2432025.6615665594457.316106497
#Sta/Elev= 30
       0 1991.51    17.81985.827    37.1  1975.7      50 1964.45    57.9 1959.91
    78.7  1958.1    90.6 1953.57   111.5 1953.29   121.7 1948.71   126.2 1947.82
  186.251949.767   236.4 1952.52   359.5    1951   376.4 1952.68   386.4 1947.11
   396.4 1946.62   409.6 1947.12   428.5 1952.47   470.6  1950.4   548.1 1953.52
   579.1 1950.15   613.9 1950.33   648.6 1947.26   683.4 1953.54   883.8 1955.91
   899.1 1957.47   904.9 1959.32   917.9 1964.48  961.471985.363   962.7 1985.96
#Mann= 6 ,-1 , 0
       0      .1       0    17.8     .06       0  186.25     .05       0
   386.4    .045       0   409.6     .05       0  961.47      .1       0
#XS Ineff= 2 , 0
                          686.58         1958.48
Permanent Ineff=
       F       F
Bank Sta=386.4,409.6
XS Rating Curve= 0 ,0
Exp/Cntr(USF)=0,0
Exp/Cntr=0.3,0.1

Type RM Length L Ch R = 1 ,12472   ,306.1,311.2,317.6
XS GIS Cut Line= 2
2431757.85494946595427.483473887 2432144.4060099594490.160314247
#Sta/Elev= 30
       0 2002.16    17.4    1998    35.7  1983.3      66  1981.2    87.6 1962.29
   104.9 1953.53   117.9 1951.23   149.1 1951.27   161.2 1947.02  188.191947.054
   226.1 1950.07   286.6 1949.41   308.6 1946.54  420.261949.957     437 1949.17
   449.3 1945.05   455.4  1944.5   472.7 1945.18   485.6 1951.57   498.6 1948.67
  530.411948.786   598.1 1950.96   628.4 1947.11     676 1948.87   714.9 1946.29
   736.6 1951.67   905.3 1953.42   924.1 1956.38  986.691986.182  1013.9 2000.98
#Mann= 7 ,-1 , 0
       0     .06       0  188.19     .05       0  420.26      .1       0
   449.3    .045       0   472.7      .1       0  530.41     .05       0
  986.69      .1       0
#XS Ineff= 2 , 0
                          737.32          1954.7
Permanent Ineff=
       F       F
Bank Sta=449.3,472.7
XS Rating Curve= 0 ,0
Exp/Cntr(USF)=0,0
Exp/Cntr=0.3,0.1

Type RM Length L Ch R = 1 ,12161   ,418.4,407.1,393.5
XS GIS Cut Line= 3
2431937.23485332595445.1688165212432285.88875098595078.829576231
2432432.42444709594603.851802613
#Sta/Elev= 30
       0  1980.6   17.791977.906    31.3 1975.94    58.9 1968.15    75.5    1953
    82.7 1948.83   108.2  1948.4   119.5 1944.46   125.1 1943.88  177.691943.809
   266.6 1943.74   277.9 1939.87   287.6 1939.08   300.6 1939.69  307.291943.304
   316.6 1946.28   334.5 1943.16   368.5 1942.17   507.3 1944.52   561.6 1941.75
  597.151945.304   652.6 1942.75   694.4 1945.47   744.6 1946.96     799 1947.77
     867 1946.03   916.2 1949.09   934.11954.638   987.1 1975.78  1002.8 1983.29
#Mann= 8 ,-1 , 0
       0      .1       0   17.79     .06       0  177.69     .05       0
   277.9    .045       0   300.6     .05       0  307.29      .1       0
  597.15     .05       0   934.1      .1       0
#XS Ineff= 2 , 0
                          603.38         1947.52
Permanent Ineff=
       F       F
Bank Sta=277.9,300.6
XS Rating Curve= 0 ,0
Exp/Cntr(USF)=0,0
Exp/Cntr=0.3,0.1

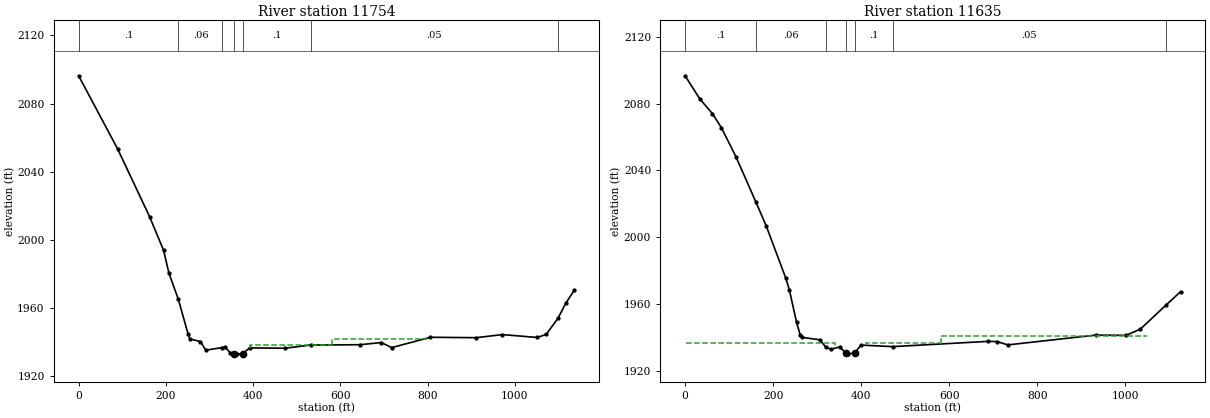
Type RM Length L Ch R = 1 ,11754   ,117.9,118.7,120.2
XS GIS Cut Line= 2
2432445.05683469595776.1373715422432568.85423313 594646.80192044
#Sta/Elev= 30
       0 2096.31    89.6 2053.33   162.6 2013.74   194.8 1993.95   206.9 1980.72
  228.68 1965.16   251.2 1944.68   255.2 1941.99   279.4 1940.48   291.4 1935.45
  329.691936.961   335.7 1937.19   347.7 1933.91   355.4 1933.41   363.8 1933.28
   375.9 1933.37     392 1936.75   473.7 1936.59  531.711938.433   645.5 1938.63
   693.8 1939.91   717.9 1936.94   806.4 1942.99     911 1942.75   971.4 1944.56
  1051.8 1942.88    1072 1944.71 1098.861954.066  1116.9 1963.02  1136.1 1970.43
#Mann= 7 ,-1 , 0
       0      .1       0  228.68     .06       0  329.69      .1       0
   355.4    .045       0   375.9      .1       0  531.71     .05       0
 1098.86      .1       0
#XS Ineff= 2 ,-1
  392.74  581.741938.745  581.89  799.57 1941.97
Permanent Ineff=
       F       F
Bank Sta=355.4,375.9
XS Rating Curve= 0 ,0
Exp/Cntr(USF)=0,0
Exp/Cntr=0.5,0.3

Type RM Length L Ch R = 1 ,11635   ,64.2,65,64.1
XS GIS Cut Line= 2
2432533.48354786595791.2962366582432743.18118196594684.699083229
#Sta/Elev= 30
       0 2096.69    33.4 2082.82    61.9 2074.08    82.3 2065.67   115.4 2048.25
  161.122020.893   184.1 2006.87   228.8 1975.46     237 1968.35   253.3 1948.93
   261.4 1941.57   265.5 1939.91   306.2 1938.43  319.171934.249   330.6 1932.75
     351  1934.1   365.2 1930.68   365.2 1930.66   371.3 1930.02   385.3 1930.53
   399.8 1935.26  471.631934.345   688.8  1937.5   709.2 1937.36   733.6 1935.39
   933.3 1941.25  1002.3 1941.09  1034.8 1944.84 1092.65 1959.15  1126.3 1967.32
#Mann= 7 ,-1 , 0
       0      .1       0  161.12     .06       0  319.17      .1       0
   365.2    .045       0   385.3      .1       0  471.63     .05       0
 1092.65      .1       0
#XS Ineff= 4 ,-1
    2.14  339.631936.554  411.41  580.381936.519  581.47 1050.271940.841
 1050.27  1126.3    1937
Permanent Ineff=
       F       F       F       F
Bank Sta=365.2,385.3
XS Rating Curve= 0 ,0
Exp/Cntr(USF)=0,0
Exp/Cntr=0.5,0.3