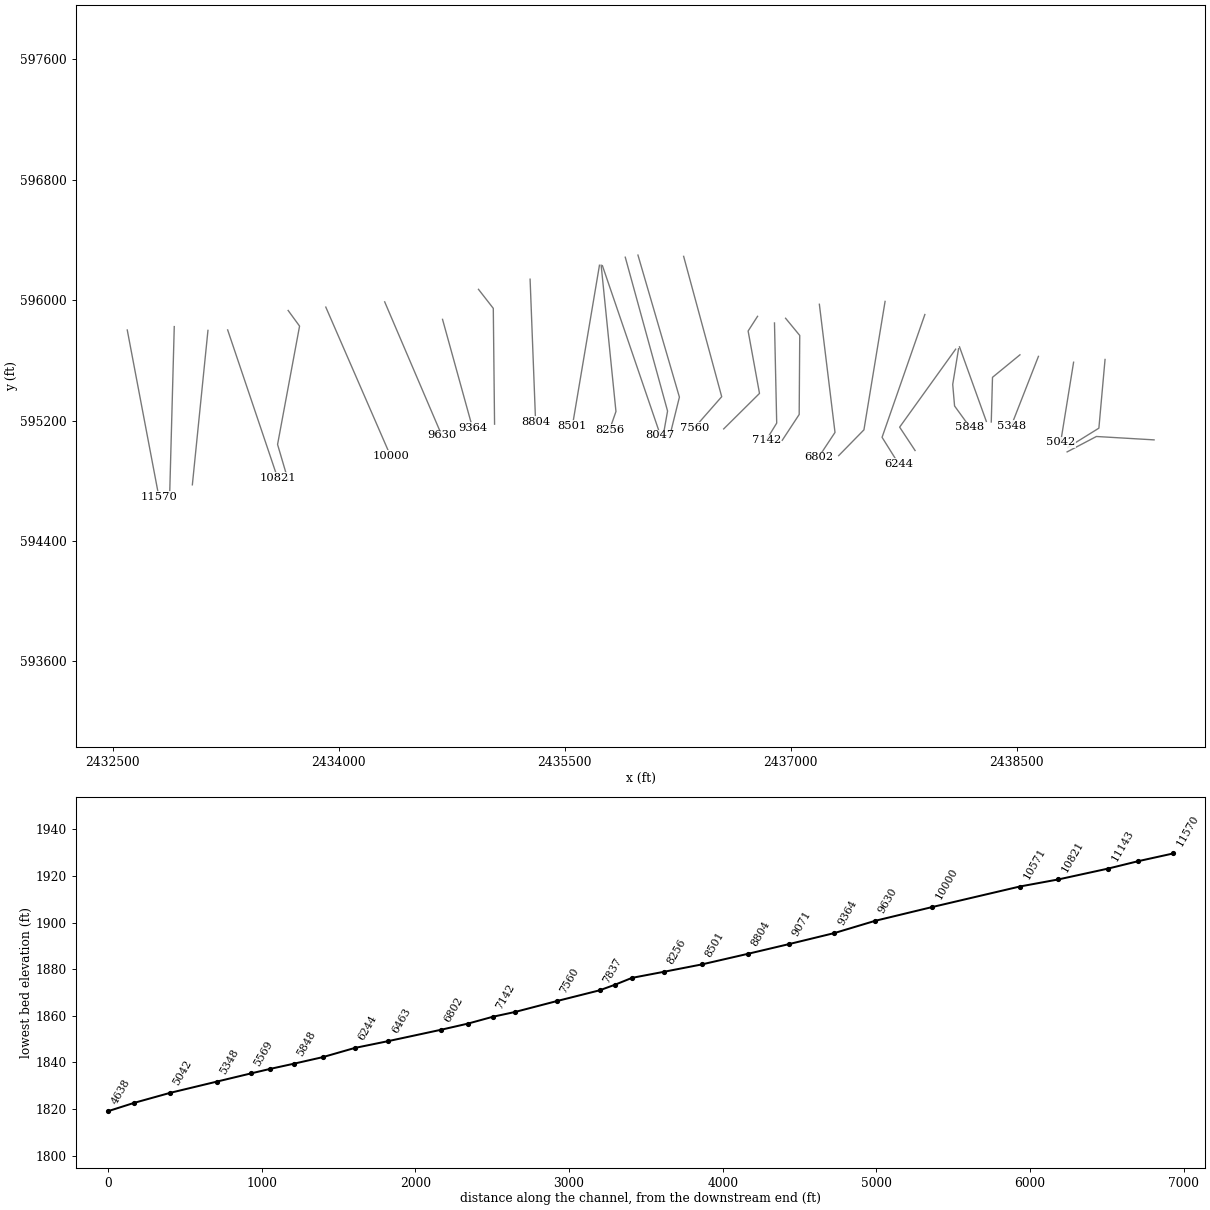
HEC-RAS study SMITHCK.prj: SMITHCK

--- SMITHCK.g01 (geometry) --- (continued)

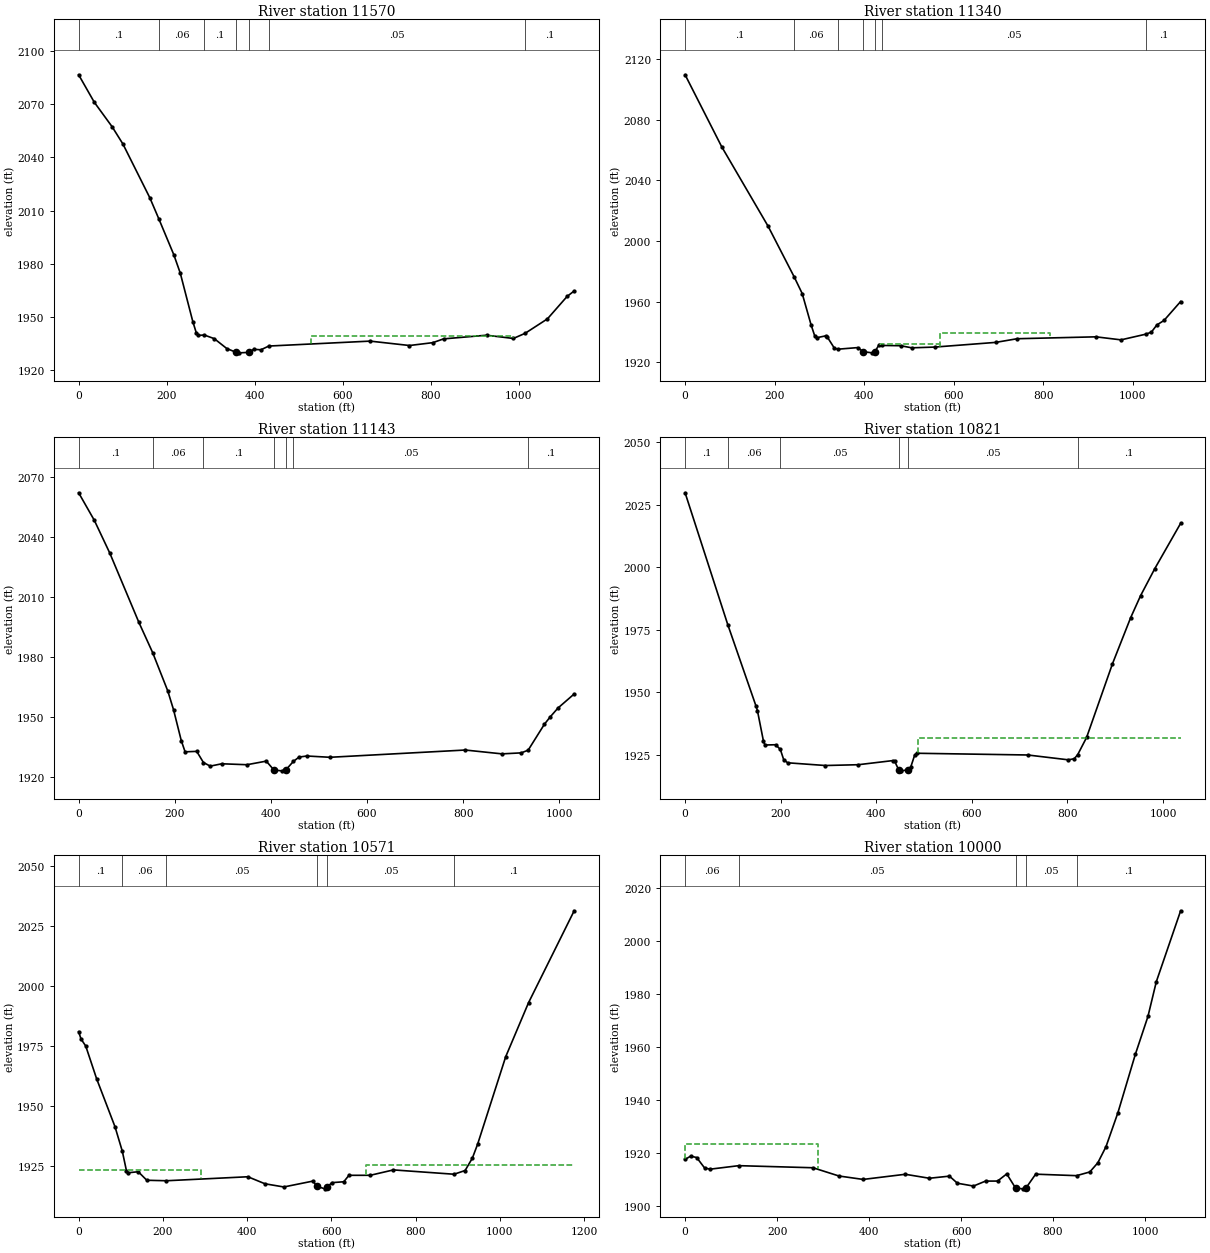
Type RM Length L Ch R = 1 ,11570   ,237.1,230,228.4
XS GIS Cut Line= 2
2432596.64548584595801.4021467342432806.34311994594694.804993306
#Sta/Elev= 30
       0 2086.65    35.6 2071.13    76.3 2057.24   100.7 2047.54   161.8  2017.2
  182.012005.446   216.2  1985.1     231 1974.66   259.5 1947.29   267.6 1940.78
   271.7 1939.44  285.511939.692   308.3 1937.63   336.8 1932.04   357.4 1929.97
   365.3 1929.62   386.9 1929.88   397.9 1931.63   414.2 1931.33  432.321933.457
   662.5 1936.24     752 1933.76     805 1935.37   829.4  1937.5   927.1 1939.57
   988.1 1937.74 1014.751940.636  1065.5  1948.8  1110.3 1961.49  1126.3 1964.56
#Mann= 7 ,-1 , 0
       0      .1       0  182.01     .06       0  285.51      .1       0
   357.4    .045       0   386.9      .1       0  432.32     .05       0
 1014.75      .1       0
#XS Ineff= 2 ,-1
  528.35  987.251939.268  987.25  1126.3 1934.76
Permanent Ineff=
       F       F
Bank Sta=357.4,386.9
XS Rating Curve= 0 ,0
Exp/Cntr(USF)=0,0
Exp/Cntr=0.5,0.3

Type RM Length L Ch R = 1 ,11340   ,197.8,196.7,195.1
XS GIS Cut Line= 2
     2432908.596      595824.0052432878.40304496594717.372562806
#Sta/Elev= 30
       0 2109.69    81.6 2062.31   185.5 2009.75  243.691976.373   261.6 1965.39
   281.6 1944.57   289.6 1937.45   293.6 1936.23   313.7 1937.45   317.7 1936.69
   333.7 1929.24  342.011928.699   385.7 1929.74  397.721927.047   417.7 1926.28
  423.321926.724   433.7 1931.78  440.331931.157   481.7 1930.97   506.3 1929.59
   557.7 1930.08   693.8 1933.17   741.8 1935.59   917.8 1936.84   973.8 1934.84
 1030.251938.662  1041.8    1940  1053.8 1944.65  1069.9 1947.66    1107 1960.13
#Mann= 7 ,-1 , 0
       0      .1       0  243.69     .06       0  342.01      .1       0
  397.72    .045       0  423.32      .1       0  440.33     .05       0
 1030.25      .1       0
#XS Ineff= 2 ,-1
  436.02   568.71931.878   568.7  815.32 1939.18
Permanent Ineff=
       F       F
Bank Sta=397.72,423.32
XS Rating Curve= 0 ,0
Exp/Cntr(USF)=0,0
Exp/Cntr=0.3,0.1

Type RM Length L Ch R = 1 ,11143   ,314.7,321.7,327.3
XS GIS Cut Line= 2
2433132.25871992595798.8756692152433028.67314163594773.125796402
#Sta/Elev= 30
       0 2062.19    32.6 2048.43    64.8 2032.04   125.3 1997.39  153.921982.279
   185.4 1963.11   197.4 1953.71   213.5 1938.25   221.5  1932.6   245.7 1932.83
  259.631927.258   273.8 1925.45   297.9 1926.62   350.2 1926.15   390.4 1927.95
  406.391923.482   422.5 1923.09  430.591923.429  446.931927.835   458.7 1929.98
   474.8 1930.51     523 1929.87   804.4  1933.5   880.8 1931.58     921 1932.08
  935.281933.439   969.2 1946.45   981.3 1950.12   997.4 1954.53    1031 1961.54
#Mann= 7 ,-1 , 0
       0      .1       0  153.92     .06       0  259.63      .1       0
  406.39    .045       0  430.59      .1       0  446.93     .05       0
  935.28      .1       0
Bank Sta=406.39,430.59
XS Rating Curve= 0 ,0
Exp/Cntr(USF)=0,0
Exp/Cntr=0.3,0.1

Type RM Length L Ch R = 1 ,10821   ,260.3,250.8,244.3
XS GIS Cut Line= 2
2433262.96895387595801.9311911272433594.21822861594819.412155866
#Sta/Elev= 30
       0 2029.69   89.321976.935   148.3 1944.43   151.4  1942.5     164 1930.32
   167.2  1928.8   189.3 1928.91  199.241927.065   206.3 1922.95   214.6 1921.69
   293.5  1920.6   362.4 1920.92   434.2 1922.56   438.4 1922.31  446.881918.928
   451.1 1918.47  465.881918.829   472.2 1920.01   480.6 1924.88   484.9  1925.5
     717 1924.81   801.7 1922.88   814.3  1923.3  821.471924.942   840.1 1931.81
   894.3 1961.31   932.3 1979.72   953.2 1988.58   982.9 1999.38  1036.9 2017.47
#Mann= 6 ,-1 , 0
       0      .1       0   89.32     .06       0  199.24     .05       0
  446.88    .045       0  465.88     .05       0  821.47      .1       0
#XS Ineff= 2 , 0
                          487.03         1931.64
Permanent Ineff=
       F       F
Bank Sta=446.88,465.88
XS Rating Curve= 0 ,0
Exp/Cntr(USF)=0,0
Exp/Cntr=0.3,0.1

Type RM Length L Ch R = 1 ,10571   ,560.2,570.6,579.2
XS GIS Cut Line= 4
 2433664.3981597595931.0622643332433740.19248528595827.195966319
2433594.21822861 595041.18073811 2433664.3981597594802.568972404
#Sta/Elev= 30
       0 1980.86     5.7  1977.8    16.9 1974.87    42.6 1961.32    86.4 1941.26
  103.741931.093   113.5 1923.01   117.1 1922.12   141.6 1922.55   161.9    1919
  208.571918.798   401.9 1920.46   442.6 1917.53   487.3 1916.21   556.5 1918.66
  565.681916.473     585 1915.43  589.98 1916.05   601.2    1918   629.7 1918.38
   641.9 1921.06   692.6 1921.07   747.5 1923.31  891.571921.512   917.8 1923.06
     935  1928.2   947.5 1934.01  1014.2 1970.43  1068.4 1992.91  1176.8 2031.19
#Mann= 6 ,-1 , 0
       0      .1       0  103.74     .06       0  208.57     .05       0
  565.68    .045       0  589.98     .05       0  891.57      .1       0
#XS Ineff= 2 , 0
           289.7  1923.3  681.76         1925.23
Permanent Ineff=
       F       F
Bank Sta=565.68,589.98
XS Rating Curve= 0 ,0
Exp/Cntr(USF)=0,0
Exp/Cntr=0.3,0.1

Type RM Length L Ch R = 1 ,10000   ,370.1,370.3,370
XS GIS Cut Line= 2
2433914.23871438595953.5198422812434343.73989266594965.386412533
#Sta/Elev= 30
       0 1917.71    12.1 1918.96    25.2 1918.42    42.6 1914.44    54.8 1914.04
  116.581915.358   278.1 1914.57   334.5 1911.46   387.1 1910.17   478.7 1912.11
   531.1 1910.61   574.7 1911.41   592.1 1908.73     627 1907.67   653.2 1909.54
   679.3 1909.55   699.3 1912.25  718.631906.888   735.1 1906.62  740.431906.774
   762.2 1912.15  851.011911.589   879.9 1912.98   897.4 1916.45   915.1 1922.51
     941 1935.31   978.9 1957.32  1006.3  1971.6  1024.5 1984.71  1077.4 2011.46
#Mann= 5 ,-1 , 0
       0     .06       0  116.58     .05       0  718.63    .045       0
  740.43     .05       0  851.01      .1       0
#XS Ineff= 2 , 0
          288.16 1923.52
Permanent Ineff=
       F       F
Bank Sta=718.63,740.43
XS Rating Curve= 0 ,0
Exp/Cntr(USF)=0,0
Exp/Cntr=0.3,0.1

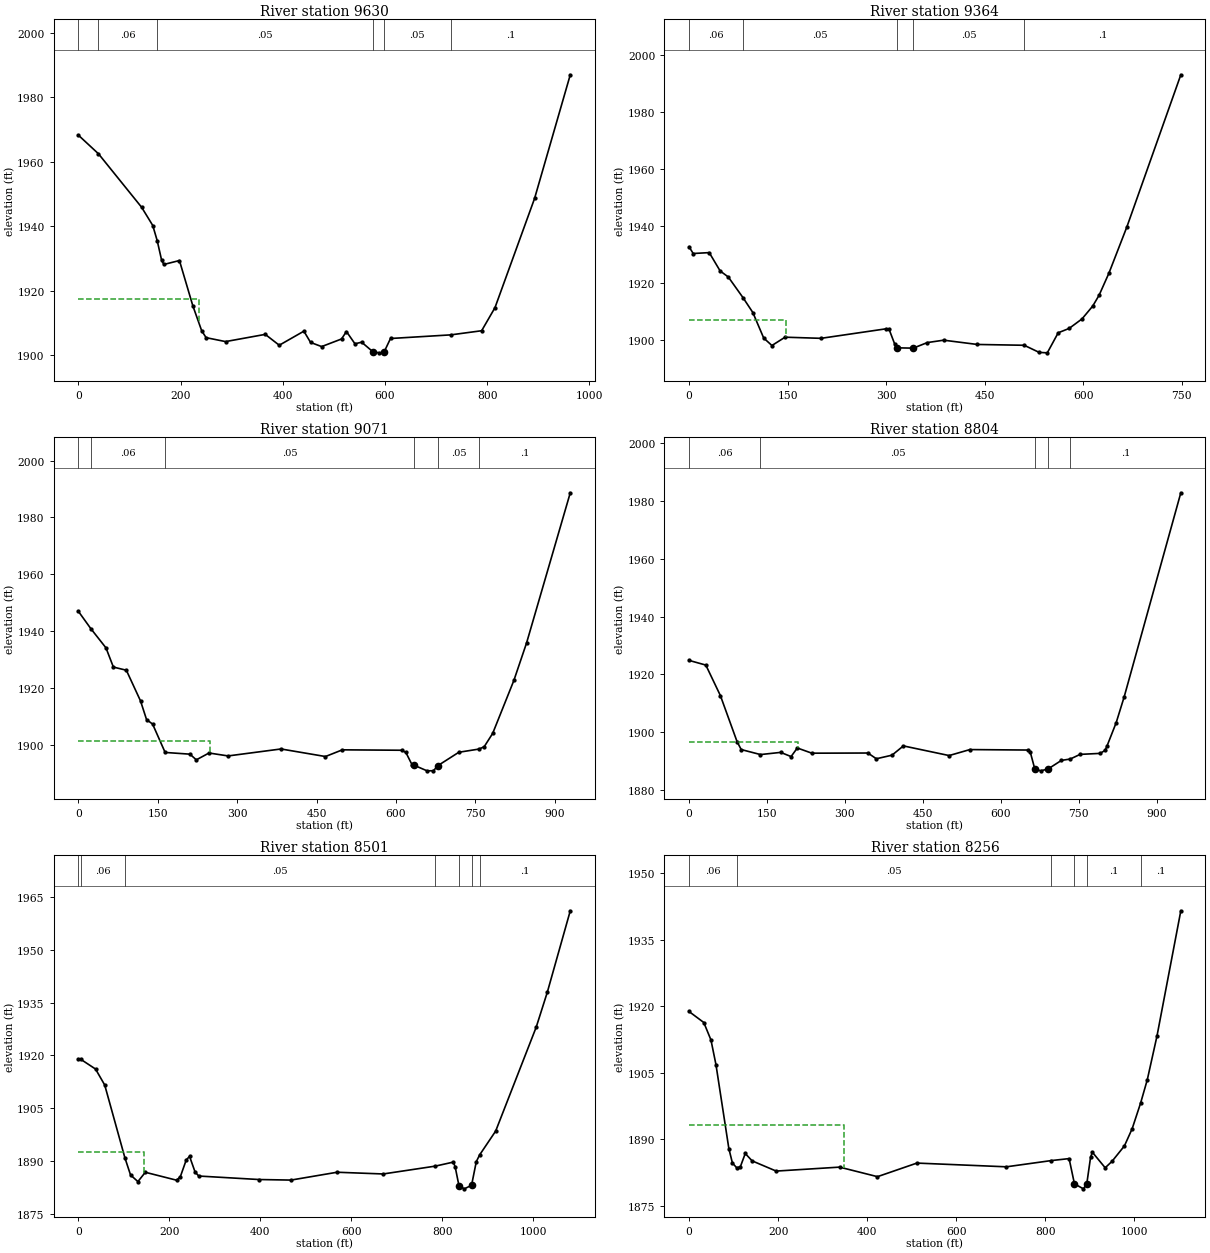
Type RM Length L Ch R = 1 ,9630    ,267.5,265.3,263
XS GIS Cut Line= 2
2434305.10198971595988.2739558282434683.41075913 595102.93907747
#Sta/Elev= 30
       0 1968.25   39.191962.495   123.8 1945.87   145.5 1940.24  154.161935.547
   162.9 1929.42   167.3 1928.16   197.7 1929.37   223.8 1915.39   241.2  1907.6
   249.9 1905.44     288 1904.22   365.7 1906.46   393.1 1903.09   441.3 1907.45
   454.4 1903.96   476.1 1902.67     515 1905.03   524.6 1907.34   541.3 1903.54
   554.4 1904.03  576.591901.041   589.2 1900.73  597.891900.839   610.9 1905.18
  728.981906.307   789.3 1907.59   815.4 1914.75   892.9 1948.63   962.8 1987.01
#Mann= 6 ,-1 , 0
       0     .05       0   39.19     .06       0  154.16     .05       0
  576.59    .045       0  597.89     .05       0  728.98      .1       0
#XS Ineff= 2 , 0
          236.75  1917.4
Permanent Ineff=
       F       F
Bank Sta=576.59,597.89
XS Rating Curve= 0 ,0
Exp/Cntr(USF)=0,0
Exp/Cntr=0.3,0.1

Type RM Length L Ch R = 1 ,9364    ,289.4,293.2,290.2
XS GIS Cut Line= 2
2434689.02515362595872.1111222172434888.33615791595150.661430611
#Sta/Elev= 30
       0 1932.71     6.4 1930.33    30.8 1930.64    47.4 1924.21    59.8 1922.09
    82.21914.837    97.2 1909.61   113.7 1900.67   126.2 1898.05   146.2 1900.97
   200.9 1900.57   300.5 1903.93   304.6 1903.67   312.9 1898.66  317.091897.233
  341.29 1897.13   362.7 1899.08   387.6 1899.92   438.8 1898.42  510.151898.134
   532.9 1895.64   545.3 1895.48   561.9 1902.52   578.5 1904.04   598.1 1907.38
   614.4 1911.88   624.1 1915.68   639.1 1923.44   666.4 1939.66   748.5 1993.03
#Mann= 5 ,-1 , 0
       0     .06       0    82.2     .05       0  317.09    .045       0
  341.29     .05       0  510.15      .1       0
#XS Ineff= 2 , 0
          147.91 1907.12
Permanent Ineff=
       F       F
Bank Sta=317.09,341.29
XS Rating Curve= 0 ,0
Exp/Cntr(USF)=0,0
Exp/Cntr=0.3,0.1

Type RM Length L Ch R = 1 ,9071    ,265.7,267.5,267.7
XS GIS Cut Line= 3
2434927.63691932596071.4221265132435025.88882285595945.098250551
2435034.31041458595175.926205803
#Sta/Elev= 30
       0 1946.92   23.211940.899      52 1934.09      66 1927.32    90.5 1926.21
   117.3  1915.4   128.7 1908.82   140.1 1907.25  163.791897.258   210.7 1896.65
   222.7 1894.65   246.7 1897.06   282.8 1896.03   382.7 1898.48   466.7 1895.82
   498.7 1898.18   610.7 1898.03   618.7 1897.25   630.5 1892.85  634.571892.721
   658.7 1890.78   670.7 1890.81  679.071892.604   718.7 1897.32  757.031898.453
   766.7 1899.29   782.7 1903.97   822.7  1922.6   846.7  1935.8   929.3  1988.7
#Mann= 6 ,-1 , 0
       0     .05       0   23.21     .06       0  163.79     .05       0
  634.57    .045       0  679.07     .05       0  757.03      .1       0
#XS Ineff= 2 , 0
          248.99 1901.21
Permanent Ineff=
       F       F
Bank Sta=634.57,679.07
XS Rating Curve= 0 ,0
Exp/Cntr(USF)=0,0
Exp/Cntr=0.3,0.1

Type RM Length L Ch R = 1 ,8804    ,307,302.6,299.8
XS GIS Cut Line= 2
2435270.11498304596138.7948603592435306.60854721595192.769389265
#Sta/Elev= 30
       0 1924.85    32.4 1923.22    60.4 1912.67    92.5 1896.73   100.5 1893.98
  137.611892.244   176.5    1893   196.5 1891.55   208.5 1894.52   236.5 1892.72
   344.4 1892.78   360.6 1890.79   390.7 1892.03   412.7 1895.24   500.7  1891.9
   540.7 1893.97   652.8 1893.81   656.8 1893.18  665.421887.386   676.8 1886.61
  691.221887.263   716.8 1890.22  733.821890.697   752.9 1892.31   791.4 1892.65
   800.9 1893.69   804.9 1895.33   822.3  1903.3   837.7 1912.24   946.7 1982.87
#Mann= 5 ,-1 , 0
       0     .06       0  137.61     .05       0  665.42    .045       0
  691.22     .05       0  733.82      .1       0
#XS Ineff= 2 , 0
          209.12 1896.56
Permanent Ineff=
       F       F
Bank Sta=665.42,691.22
XS Rating Curve= 0 ,0
Exp/Cntr(USF)=0,0
Exp/Cntr=0.3,0.1

Type RM Length L Ch R = 1 ,8501    ,240.9,245.2,250.9
XS GIS Cut Line= 2
2435730.49533099596231.432369398 2435550.8347074595164.697416829
#Sta/Elev= 30
       0 1918.84    4.691918.891    37.6 1916.09    57.8 1911.54  102.231890.817
   114.6 1885.96   130.8 1884.08   147.1 1886.73     216 1884.47   224.1 1885.47
   237.1 1890.23   244.4 1891.25   256.6 1886.79   264.7 1885.66   397.1 1884.67
   467.5 1884.51   568.9 1886.74   670.3 1886.25  784.991888.482   824.4 1889.62
   828.5 1888.35  836.871882.967   848.7 1882.02  864.671883.023   875.1 1889.76
  882.531891.688   917.7 1898.45  1006.9 1928.01  1031.3 1937.94  1081.8  1961.1
#Mann= 7 ,-1 , 0
       0     .05       0    4.69     .06       0  102.23     .05       0
  784.99      .1       0  836.87    .045       0  864.67      .1       0
  882.53      .1       0
#XS Ineff= 2 , 0
          144.39 1892.52
Permanent Ineff=
       F       F
Bank Sta=836.87,864.67
XS Rating Curve= 0 ,0
Exp/Cntr(USF)=0,0
Exp/Cntr=0.3,0.1

Type RM Length L Ch R = 1 ,8256    ,205.6,208.5,213.4
XS GIS Cut Line= 3
2435741.72411997596231.4323693982435839.97602349595260.142123111
2435797.86806484595139.432641636
#Sta/Elev= 30
       0 1918.82    33.2 1916.34    49.3 1912.41    60.6 1906.82    89.5 1887.93
    97.5 1884.69  107.411883.595   115.4 1883.88   126.3 1886.84   141.7 1885.18
   195.7 1882.88   338.1 1883.77   423.1 1881.62   511.6 1884.68   712.6 1883.84
  812.92 1885.24   853.3 1885.69  865.291880.005   885.4 1878.88  892.991880.017
   901.5 1885.99   905.5 1887.13   934.3 1883.62   949.8 1885.09   977.5 1888.55
   994.9 1892.43 1013.881898.214  1028.8 1903.44  1050.5 1913.25  1104.1  1941.5
#Mann= 6 ,-1 , 0
       0     .06       0  107.41     .05       0  812.92      .1       0
  865.29    .045       0  892.99      .1       0 1013.88      .1       0
#XS Ineff= 2 , 0
          347.47 1893.36
Permanent Ineff=
       F       F
Bank Sta=865.29,892.99
XS Rating Curve= 0 ,0
Exp/Cntr(USF)=0,0
Exp/Cntr=0.3,0.1

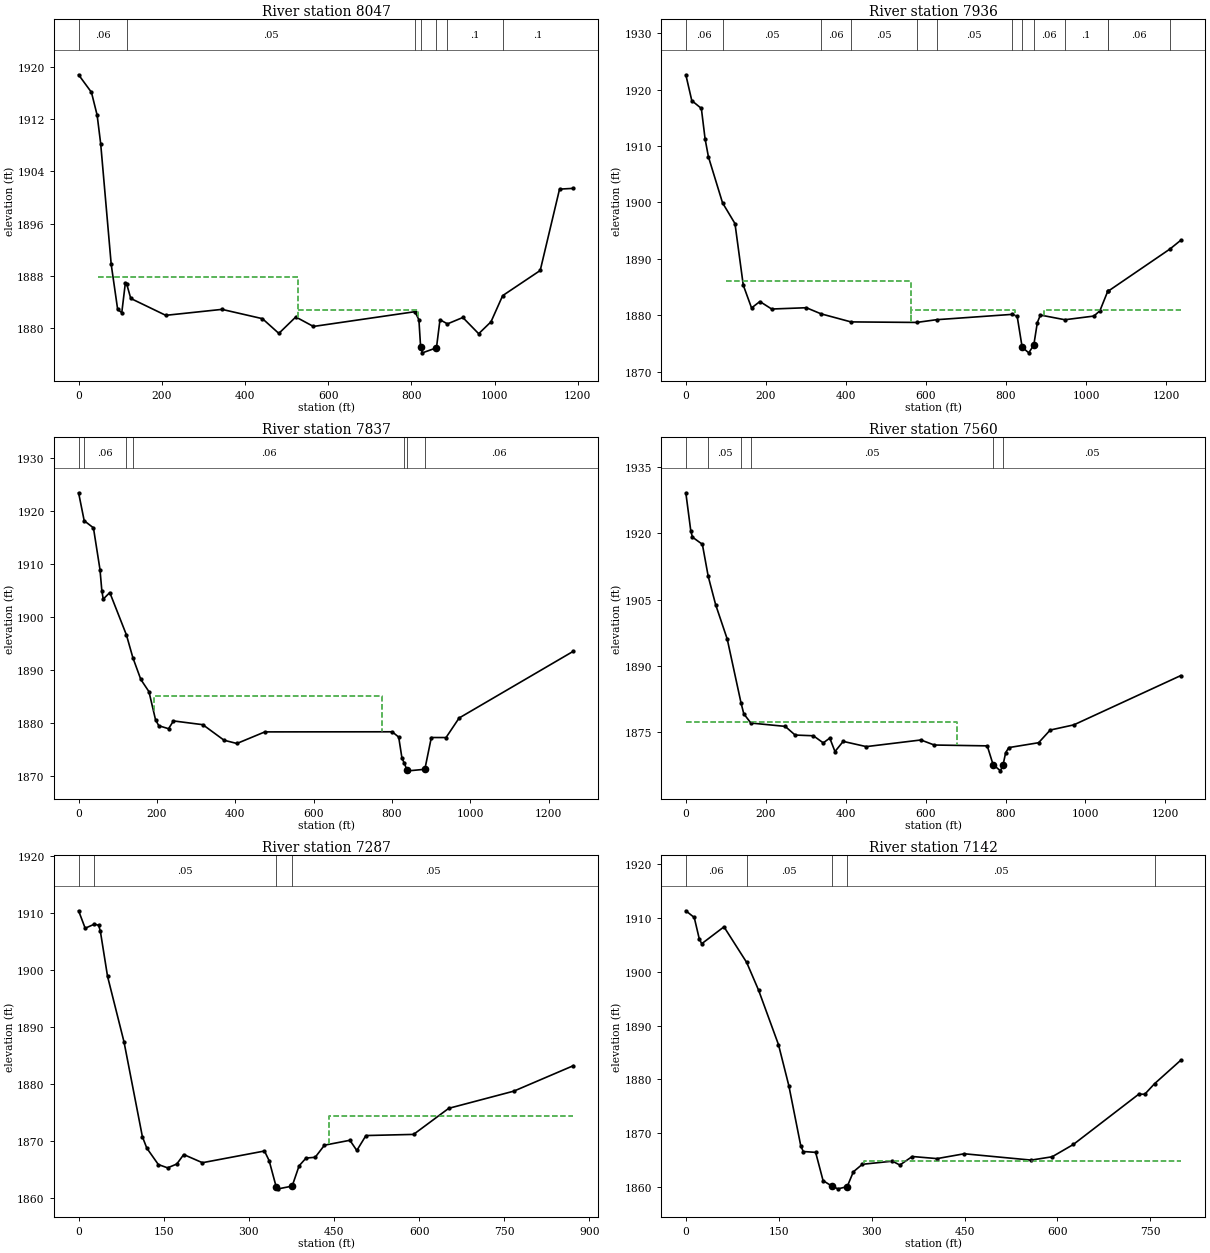
Type RM Length L Ch R = 1 ,8047    ,112.3,111,109.3
XS GIS Cut Line= 2
 2435750.1457117596228.6251721552436134.73173407 595102.93907747
#Sta/Elev= 30
       0 1918.75    30.9 1916.07    44.6 1912.57    53.1 1908.22    78.4 1889.78
    93.9 1882.91   103.8  1882.4   112.3 1886.89  115.71 1886.77   125.4 1884.58
   209.5    1882   344.7 1882.91   441.9 1881.49   481.4 1879.24   522.1 1881.75
   564.5  1880.3  808.431882.555   818.1 1881.33  822.281877.096   826.5 1876.27
  860.281877.037   868.8 1881.33  886.741880.694   923.7 1881.67   961.8 1879.19
   991.4 1881.01 1019.481885.011  1109.7 1888.85  1156.2 1901.28  1189.6  1901.4
#Mann= 7 ,-1 , 0
       0     .06       0  115.71     .05       0  808.43      .1       0
  822.28    .045       0  860.28      .1       0  886.74      .1       0
 1019.48      .1       0
#XS Ineff= 3 ,-1
       0   47.35 1882.87   47.35  527.62  1887.8  527.62  816.28 1882.87
Permanent Ineff=
       F       F       F
Bank Sta=822.28,860.28
XS Rating Curve= 0 ,0
Exp/Cntr(USF)=0,0
Exp/Cntr=0.5,0.3

Type RM Length L Ch R = 1 ,7936    ,98.2,99.8,101.6
XS GIS Cut Line= 3
2435901.73436285596284.7691170272436182.45408721595262.949320355
2436151.57491753595088.903091252
#Sta/Elev= 30
       0 1922.63    14.9 1918.05    38.8 1916.66    48.1 1911.27    56.4  1908.1
   91.731899.918   122.8 1896.24   143.5 1885.33   164.2 1881.28     185 1882.42
   214.5 1881.09   301.1 1881.32  337.821880.237  412.491878.807  576.661878.711
  626.331879.195   815.51880.143   827.9  1879.8  840.331874.315   856.9 1873.32
  869.431874.713   878.3  1878.7   885.9 1880.02  947.091879.189  1019.4 1879.84
  1034.5 1880.77 1054.01 1884.21 1054.33 1884.21 1209.411891.721  1236.4 1893.27
#Mann= 13 ,-1 , 0
       0     .06       0   91.73     .05       0  337.82     .06       0
  412.49     .05       0  576.66     .06       0  626.33     .05       0
   815.5     .06       0  840.33    .045       0  869.43     .06       0
  947.09      .1       0 1054.01      .1       0 1054.33     .06       0
 1209.41      .1       0
#XS Ineff= 4 ,-1
       0  101.01    1881  101.01  563.47 1886.08  563.47   823.1    1881
  895.34  1236.4    1881
Permanent Ineff=
       F       F       F       F
Bank Sta=840.33,869.43
XS Rating Curve= 0 ,0
Exp/Cntr(USF)=0,0
Exp/Cntr=0.5,0.3

Type RM Length L Ch R = 1 ,7837    ,276.5,276.8,275.3
XS GIS Cut Line= 3
2435985.95028016596298.8051032452436261.05561003595355.586829394
2436193.68287619595083.288696764
#Sta/Elev= 30
       0 1923.41   14.291918.132    37.9 1916.79    54.6 1908.92    59.3 1904.94
    62.9 1903.34    79.6 1904.58  121.991896.599  138.571892.273   158.8 1888.18
   179.6 1885.87   196.3 1880.59   204.6 1879.45   229.6 1878.88   242.1 1880.35
   317.1 1879.64   371.2 1876.71     404 1876.09   475.4 1878.28   800.4  1878.3
     817  1877.3   825.3 1873.34  831.411872.364  837.821871.139     842 1870.93
  883.721871.225   900.3 1877.22   937.8 1877.21   971.2  1880.9    1263 1893.51
#Mann= 7 ,-1 , 0
       0     .05       0   14.29     .06       0  121.99     .05       0
  138.57     .06       0  831.41     .05       0  837.82    .045       0
  883.72     .06       0
#XS Ineff= 1 ,-1
  191.41  775.411885.002
Permanent Ineff=
       F
Bank Sta=837.82,883.72
XS Rating Curve= 0 ,0
Exp/Cntr(USF)=0,0
Exp/Cntr=0.5,0.3

Type RM Length L Ch R = 1 ,7560    ,274.9,273.1,272.7
XS GIS Cut Line= 3
2436289.12758247596290.383511514 2436541.7753344595358.394026638
 2436362.1147108595153.468627854
#Sta/Elev= 30
       0 1929.13    12.4 1920.53    16.6 1919.11    41.4 1917.49      561910.262
    74.6 1903.86   103.6 1896.09  137.921881.761     145 1879.22  162.761877.134
   248.6 1876.38   273.5 1874.42   319.1 1874.26   343.9 1872.65   360.2 1873.74
   373.2 1870.69   393.7 1872.99   451.5 1871.81   588.2 1873.31   621.6 1872.17
   754.2 1871.98  768.891867.734   787.3 1866.34  793.771867.678   800.3 1870.45
   808.1 1871.59   882.7 1872.69   911.7 1875.55   970.8 1876.72  1238.2 1887.84
#Mann= 6 ,-1 , 0
       0     .06       0      56     .05       0  137.92     .06       0
  162.76     .05       0  768.89    .045       0  793.77     .05       0
#XS Ineff= 2 , 0
          679.15 1877.43
Permanent Ineff=
       F       F
Bank Sta=768.89,793.77
XS Rating Curve= 0 ,0
Exp/Cntr(USF)=0,0
Exp/Cntr=0.3,0.1

Type RM Length L Ch R = 1 ,7287    ,146.8,144.7,142
XS GIS Cut Line= 4
2436779.71157754 595892.208082952436717.09030575595794.592571039
2436792.60419232595380.1870959452436555.01171994595144.436425669
#Sta/Elev= 30
       0 1910.38    11.6 1907.32   27.991908.043    35.4 1907.83    38.4 1906.76
      51 1898.89      80 1887.41   112.4 1870.79   120.2 1868.78   140.5 1865.91
   156.8 1865.33     173    1866   185.2 1867.66   218.2 1866.23   327.5 1868.28
   335.7  1866.6   348.1 1862.02   351.9 1861.65   376.3 1862.13   388.5 1865.68
   400.7 1867.04   416.9 1867.18   433.2  1869.3     478 1870.16   490.2 1868.37
   506.3 1870.99   590.2 1871.19   652.2 1875.76   766.8 1878.77   871.9 1883.24
#Mann= 4 ,-1 , 0
       0     .06       0   27.99     .05       0   348.1    .045       0
   376.3     .05       0
#XS Ineff= 2 , 0
                          440.85         1874.33
Permanent Ineff=
       F       F
Bank Sta=348.1,376.3
XS Rating Curve= 0 ,0
Exp/Cntr(USF)=0,0
Exp/Cntr=0.3,0.1

Type RM Length L Ch R = 1 ,7142    ,162.3,161.8,161.1
XS GIS Cut Line= 3
2436892.06150635595848.0048322732436906.79592324595183.114270011
  2436836.807443595068.922539097
#Sta/Elev= 30
       0 1911.36    13.6 1910.11    21.6 1906.18    25.6 1905.22    61.6 1908.37
   98.231901.744   117.6 1896.54   149.6 1886.44   166.4 1878.76   185.6 1867.59
   189.6 1866.54   209.6 1866.38   221.6 1861.12   235.9 1860.09   245.6 1859.59
   260.5 1859.99   270.5 1862.76     285 1864.16   333.6 1864.74   345.6 1864.02
   365.6 1865.61   405.6 1865.22   449.6 1866.12   557.6 1864.94   591.5 1865.56
   625.7 1867.85   731.4 1877.22     741  1877.2  756.751879.155     799 1883.52
#Mann= 5 ,-1 , 0
       0     .06       0   98.23     .05       0   235.9    .045       0
   260.5     .05       0  756.75      .1       0
#XS Ineff= 2 , 0
                          286.95         1864.79
Permanent Ineff=
       F       F
Bank Sta=235.9,260.5
XS Rating Curve= 0 ,0
Exp/Cntr(USF)=0,0
Exp/Cntr=0.3,0.1

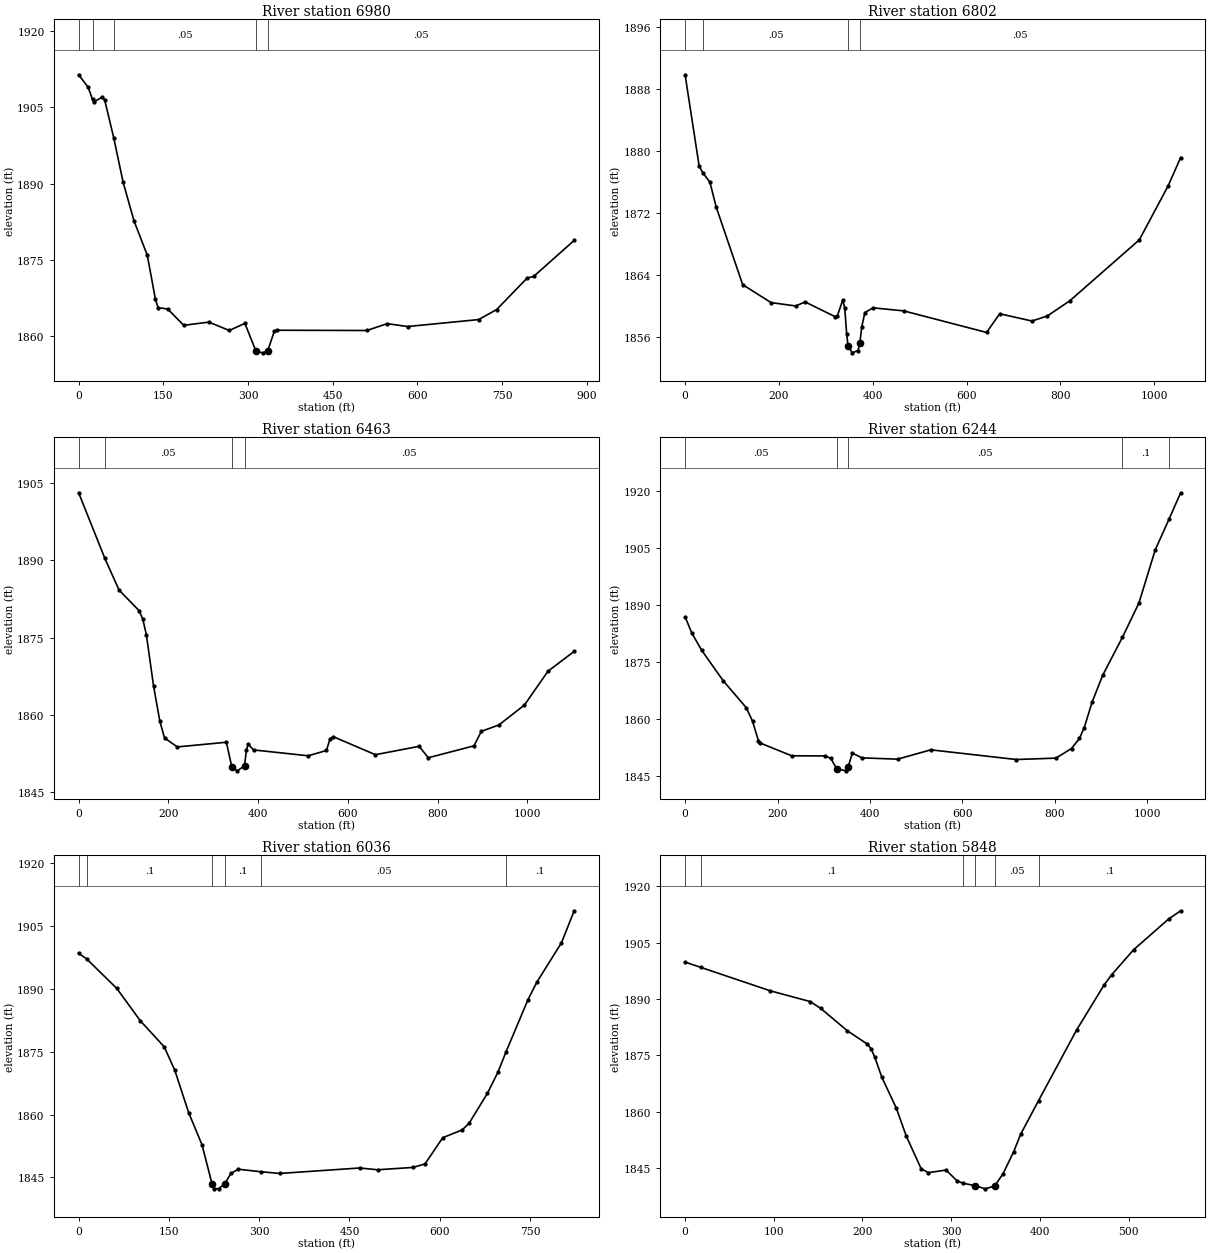
Type RM Length L Ch R = 1 ,6980    ,176.3,177.8,179.8
XS GIS Cut Line= 4
2436965.73359081595879.315468169 2437059.6654985595765.123737254
2437055.98189427595240.2101354692436943.63196547595068.922539097
#Sta/Elev= 30
       0 1911.42    16.7    1909    24.61906.554      27 1906.04    41.3 1907.01
      46 1906.52   62.231898.983    78.8 1890.26    98.1 1882.63   121.6 1875.89
   135.8 1867.32   140.7 1865.56   157.9 1865.28   186.1 1862.08   230.7 1862.71
   266.7 1861.07   294.5 1862.46  314.111856.957     326 1856.66  334.511856.943
   346.5 1860.89   350.5 1861.11   510.5 1861.06   546.5 1862.41   582.5 1861.84
   708.3 1863.21   740.3 1865.18   794.4  1871.4   805.9 1871.71   877.6  1878.8
#Mann= 5 ,-1 , 0
       0    .055       0    24.6     .06       0   62.23     .05       0
  314.11    .045       0  334.51     .05       0
Bank Sta=314.11,334.51
XS Rating Curve= 0 ,0
Exp/Cntr(USF)=0,0
Exp/Cntr=0.3,0.1

Type RM Length L Ch R = 1 ,6802    ,345.2,339.3,334.6
XS GIS Cut Line= 3
2437189.90499073595972.2304635212437293.68707282595121.060187288
2437184.15023638594955.351333998
#Sta/Elev= 30
       0 1889.83      30 1878.05   38.421877.129    52.8    1876    66.3 1872.77
   122.7 1862.77   183.1 1860.46     236 1860.02   255.7 1860.55   320.1 1858.63
   324.2  1858.7   336.2 1860.82   340.3 1859.72   344.3 1856.45   347.3 1854.87
   356.4 1853.98   368.5 1854.28   372.6 1855.31   376.5 1857.35   383.2 1859.18
   400.7 1859.78   465.8 1859.39   642.5 1856.61   670.5 1859.02   739.2 1858.08
   771.8 1858.73   819.7 1860.68   968.1 1868.55  1029.3 1875.49  1056.1 1879.15
#Mann= 4 ,-1 , 0
       0     .06       0   38.42     .05       0   347.3    .045       0
   372.6     .05       0
Bank Sta=347.3,372.6
XS Rating Curve= 0 ,0
Exp/Cntr(USF)=0,0
Exp/Cntr=0.3,0.1

Type RM Length L Ch R = 1 ,6463    ,221.9,218.6,215.5
XS GIS Cut Line= 3
2437626.03115449 595991.347476752437485.66104885595138.207254986
 2437318.0570567594966.919658614
#Sta/Elev= 30
       0 1903.13   58.431890.399    90.1 1884.25   134.7 1880.26   142.9 1878.64
   150.9 1875.61   167.1 1865.57     181 1858.78   191.4 1855.56   219.8 1853.81
   329.3 1854.72  341.391849.883   353.6 1849.17  369.791850.158   373.8 1853.17
   377.9 1854.34   389.9 1853.23   511.7 1852.09   552.2 1853.12   560.4 1855.41
   567.4  1855.8   661.4  1852.3   758.8 1853.93   779.2 1851.71     881 1854.02
   897.4 1856.83   936.9 1858.09   993.6 1861.95  1045.8 1868.49  1104.3 1872.35
#Mann= 4 ,-1 , 0
       0     .06       0   58.43     .05       0  341.39    .045       0
  369.79     .05       0
Bank Sta=341.39,369.79
XS Rating Curve= 0 ,0
Exp/Cntr(USF)=0,0
Exp/Cntr=0.3,0.1

Type RM Length L Ch R = 1 ,6244    ,212.5,208.9,203.2
XS GIS Cut Line= 3
2437890.02279048595904.1915817692437606.02145254595088.637059125
2437716.52957923594911.824056418
#Sta/Elev= 30
       0 1886.79    14.6 1882.49    35.7 1878.01    82.3 1869.97   132.7  1862.8
   145.9 1859.28   158.6 1854.19   162.8 1853.54   230.6 1850.19   302.6 1850.16
   315.3 1849.51     328 1846.76   349.1 1846.23   352.5 1847.21   361.9 1850.89
     383 1849.64   459.6 1849.31   531.6 1851.76   716.9 1849.21   802.3 1849.58
     836 1852.11   853.1 1854.75   863.6 1857.62   880.3 1864.25   903.8 1871.48
  946.181881.396   981.9 1890.43    1017 1904.38 1046.841912.463  1072.1 1919.45
#Mann= 5 ,-1 , 0
       0     .05       0     328    .045       0   352.5     .05       0
  946.18      .1       0 1046.84     .05       0
Bank Sta=328,352.5
XS Rating Curve= 0 ,0
Exp/Cntr(USF)=0,0
Exp/Cntr=0.3,0.1

Type RM Length L Ch R = 1 ,6036    ,179.9,187.8,201.4
XS GIS Cut Line= 3
2438094.44072379595673.9462547892437722.68100197595156.176668678
2437825.11773179595000.940208813
#Sta/Elev= 30
       0 1898.41   13.17 1897.12    63.4 1890.06   102.5 1882.35   142.2 1876.14
   159.8 1870.54   182.8 1860.45     205 1852.79   221.91843.325   225.6 1842.36
   232.5 1842.28     243 1843.52     253 1845.97   265.3 1846.96  303.761846.341
   334.2 1845.95   467.1 1847.25   496.7 1846.83   555.3 1847.38   575.5 1848.21
     605 1854.47   637.4 1856.33     649 1857.97   679.2 1865.03   696.5 1870.02
  710.341874.997   746.7 1887.39   761.2  1891.5   802.3 1900.94   823.4 1908.57
#Mann= 6 ,-1 , 0
       0     .05       0   13.17      .1       0   221.9    .045       0
     243      .1       0  303.76     .05       0  710.34      .1       0
Bank Sta=221.9,243
XS Rating Curve= 0 ,0
Exp/Cntr(USF)=0,0
Exp/Cntr=0.3,0.1

Type RM Length L Ch R = 1 ,5848    ,153,154.5,161
XS GIS Cut Line= 4
2438113.81038477595677.3710354262438074.92789575595439.983207718
 2438087.2065765595296.7319323772438189.52891603595155.527103827
#Sta/Elev= 30
       0 1899.84   18.11  1898.4    96.2 1892.18   140.9 1889.34   152.9 1887.52
   182.7 1881.59   205.6 1877.98   209.7 1876.75   213.7 1874.62   221.8 1869.19
     238 1861.04   249.3 1853.56   266.1 1844.83   274.2 1843.78   294.2 1844.47
   306.3 1841.68  312.771840.984   326.9 1840.33   338.4 1839.47  349.111840.242
   358.5  1843.5   370.5 1849.38   378.5 1854.09  398.451862.932   441.4 1881.76
   472.3 1893.71   480.9 1896.46   505.6 1903.11   545.1  1911.3   558.7  1913.5
#Mann= 6 ,-1 , 0
       0     .05       0   18.11      .1       0  312.77     .05       0
   326.9    .045       0  349.11     .05       0  398.45      .1       0
Bank Sta=326.9,349.11
XS Rating Curve= 0 ,0
Exp/Cntr(USF)=0,0
Exp/Cntr=0.3,0.1

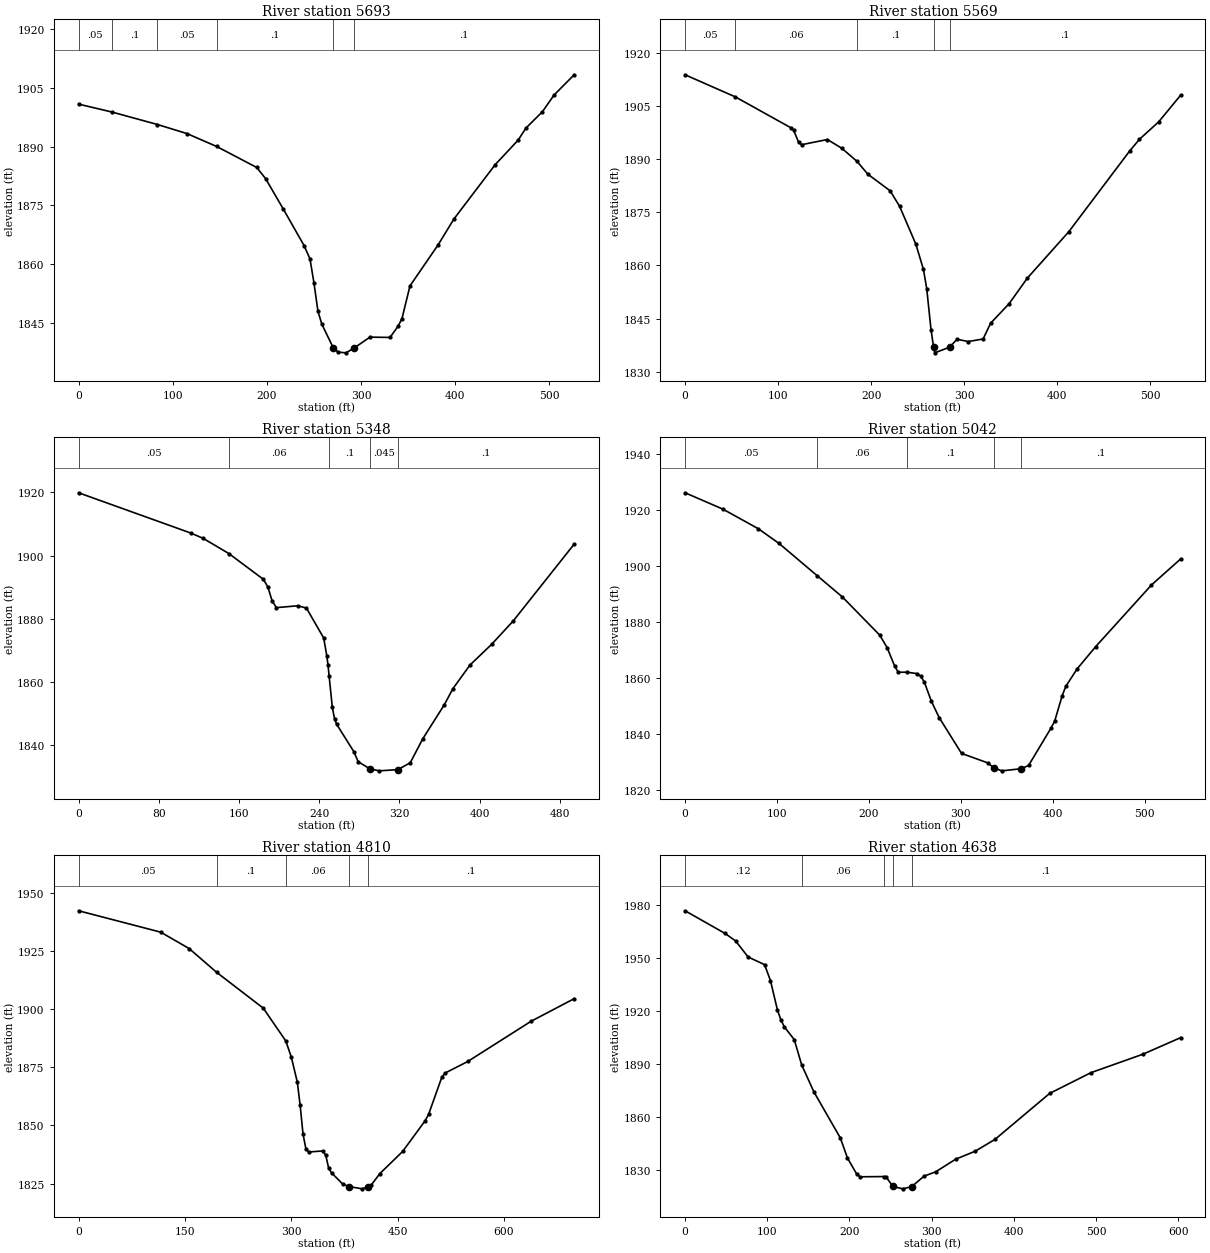
Type RM Length L Ch R = 1 ,5693    ,130.6,124,119.8
XS GIS Cut Line= 2
2438119.94972515 595689.649716172438297.99059593595194.409592848
#Sta/Elev= 30
       0 1900.87   35.521898.839   83.751895.657     115 1893.34  146.611890.035
   189.2 1884.66   198.6  1881.8   217.4 1874.02   239.4  1864.7   245.7 1861.29
   249.9 1855.19   254.2 1847.82   258.4 1844.52  270.391838.546   275.4 1837.43
   283.9 1837.24  292.381838.436   309.4 1841.26   330.7 1841.18   339.3 1844.06
   343.4 1845.99   351.9 1854.37   381.7 1864.83   398.6 1871.49   442.4 1885.38
   466.7 1891.64   475.2 1894.78   492.5 1898.91   504.9 1903.19   526.3 1908.38
#Mann= 6 ,-1 , 0
       0     .05       0   35.52      .1       0   83.75     .05       0
  146.61      .1       0  270.39    .045       0  292.38      .1       0
Bank Sta=270.39,292.38
XS Rating Curve= 0 ,0
Exp/Cntr(USF)=0,0
Exp/Cntr=0.3,0.1

Type RM Length L Ch R = 1 ,5569    ,227.2,221,219.5
XS GIS Cut Line= 3
 2438521.0532961595636.4420996152438338.91953174595487.051483902
2438330.73374458595190.316699267
#Sta/Elev= 30
       0 1913.87    53.91907.634   113.8 1898.88   116.7 1898.16   121.9 1894.82
   125.2 1894.12   152.9 1895.58   168.4  1893.1  184.751889.402   196.3 1885.79
   220.2 1881.11   230.4 1876.75   247.9 1866.03   256.1 1858.87   259.6 1853.46
   264.2 1841.91  266.971836.921   268.2 1835.32  284.211836.924   292.2 1839.16
   304.2 1838.51   320.2 1839.24   328.2 1843.67   348.2 1849.23   367.7 1856.43
   412.2 1869.52   477.6 1892.33   488.2 1895.66   508.8 1900.57   532.4  1908.1
#Mann= 5 ,-1 , 0
       0     .05       0    53.9     .06       0  184.75      .1       0
  266.97    .045       0  284.21      .1       0
Bank Sta=266.97,284.21
XS Rating Curve= 0 ,0
Exp/Cntr(USF)=0,0
Exp/Cntr=0.3,0.1

Type RM Length L Ch R = 1 ,5348    ,303.3,306.4,311.5
XS GIS Cut Line= 2
2438643.84010354595626.2098656622438463.75278596 595165.75933778
#Sta/Elev= 30
       0 1919.87   111.8 1907.13   124.3 1905.43  150.021900.595   184.4 1892.45
   188.7 1890.09     193 1885.69   197.3  1883.5   218.8 1884.09   227.3 1883.35
   244.5 1873.88   247.6 1868.24   248.8 1865.35  249.931861.813   253.1 1851.89
   255.4  1848.2   257.4 1846.58   274.6 1837.88   278.9 1834.71  290.811832.418
   300.1 1831.82  318.611832.211   330.9 1834.39   343.3 1841.95   364.8 1852.72
   373.4 1857.84   390.5 1865.34     412 1871.86   433.5 1879.25   494.4 1903.61
#Mann= 5 ,-1 , 0
       0     .05       0  150.02     .06       0  249.93      .1       0
  290.81    .045       0  318.61      .1       0
Bank Sta=290.81,318.61
XS Rating Curve= 0 ,0
Exp/Cntr(USF)=0,0
Exp/Cntr=0.3,0.1

Type RM Length L Ch R = 1 ,5042    ,230.6,231.9,233.2
XS GIS Cut Line= 2
2438877.13503766 595587.327376642438791.18427246595055.251211088
#Sta/Elev= 30
       0 1926.15    41.2  1920.3    79.6 1913.33   102.2 1908.08  143.841896.522
     171 1889.01   211.6 1875.41   219.7 1870.95   227.8 1864.44   231.8 1862.12
  241.371862.157   252.1 1861.65   256.1 1860.82   260.2 1858.63   267.9 1851.77
   276.4 1845.93   300.7 1833.18     329 1829.82  336.381827.906   344.6 1826.96
  365.581827.718   373.6 1828.87   397.9 1842.16     402  1844.7   410.1 1853.72
   414.1 1857.11   426.3 1863.28   446.5 1871.24   507.3 1893.27     539 1902.55
#Mann= 5 ,-1 , 0
       0     .05       0  143.84     .06       0  241.37      .1       0
  336.38    .045       0  365.58      .1       0
Bank Sta=336.38,365.58
XS Rating Curve= 0 ,0
Exp/Cntr(USF)=0,0
Exp/Cntr=0.3,0.1

Type RM Length L Ch R = 1 ,4810    ,202.3,172.4,149.9
XS GIS Cut Line= 3
 2439085.8726103595605.7453977562439044.94367449595149.387763455
2438840.29899543595022.508062439
#Sta/Elev= 30
       0 1942.19   115.7 1933.01   155.9 1925.96  194.481915.789   260.4 1900.36
  292.221886.277   300.1 1879.22   308.5 1868.53   312.5 1858.54   316.5  1846.3
   320.5    1840   324.5 1838.54   344.6    1839   348.7 1837.04   352.7 1831.53
   356.7  1829.6   372.7 1824.71  381.791823.672   400.2 1822.71  407.591823.569
   412.9 1824.41   424.9 1829.25   457.1  1838.8     489 1852.06   493.7 1854.76
   512.5 1870.83   517.2  1872.5     549 1877.45   638.2 1894.71     699 1904.42
#Mann= 5 ,-1 , 0
       0     .05       0  194.48      .1       0  292.22     .06       0
  381.79    .045       0  407.59      .1       0
Bank Sta=381.79,407.59
XS Rating Curve= 0 ,0
Exp/Cntr(USF)=0,0
Exp/Cntr=0.3,0.1

Type RM Length L Ch R = 1 ,4638    ,303.9,319.4,330.1
XS GIS Cut Line= 3
2439411.25765001595071.6227854132439028.57210017 595094.13370011
2438834.15965506 594991.81136058
#Sta/Elev= 30
       0 1976.87    48.6 1964.01    61.4 1959.78    76.7 1950.64    96.7 1946.31
   103.9 1937.23   112.4  1920.5   116.7 1914.83   120.7 1911.03   132.8  1903.8
  141.931889.307   156.8 1874.05   188.9 1847.97   197.6 1836.55   208.9 1827.41
   212.9 1825.93  241.771826.057   244.9 1825.64  252.921820.434     265 1819.09
  275.721820.355   290.8 1826.29     305 1828.77   329.1 1835.87   353.1 1840.47
   377.2 1847.18   443.6 1873.24     494 1885.03   557.2  1895.5     603 1904.89
#Mann= 5 ,-1 , 0
       0     .12       0  141.93     .06       0  241.77      .1       0
  252.92    .045       0  275.72      .1       0
Bank Sta=252.92,275.72
XS Rating Curve= 0 ,0
Exp/Cntr(USF)=0,0
Exp/Cntr=0.3,0.1