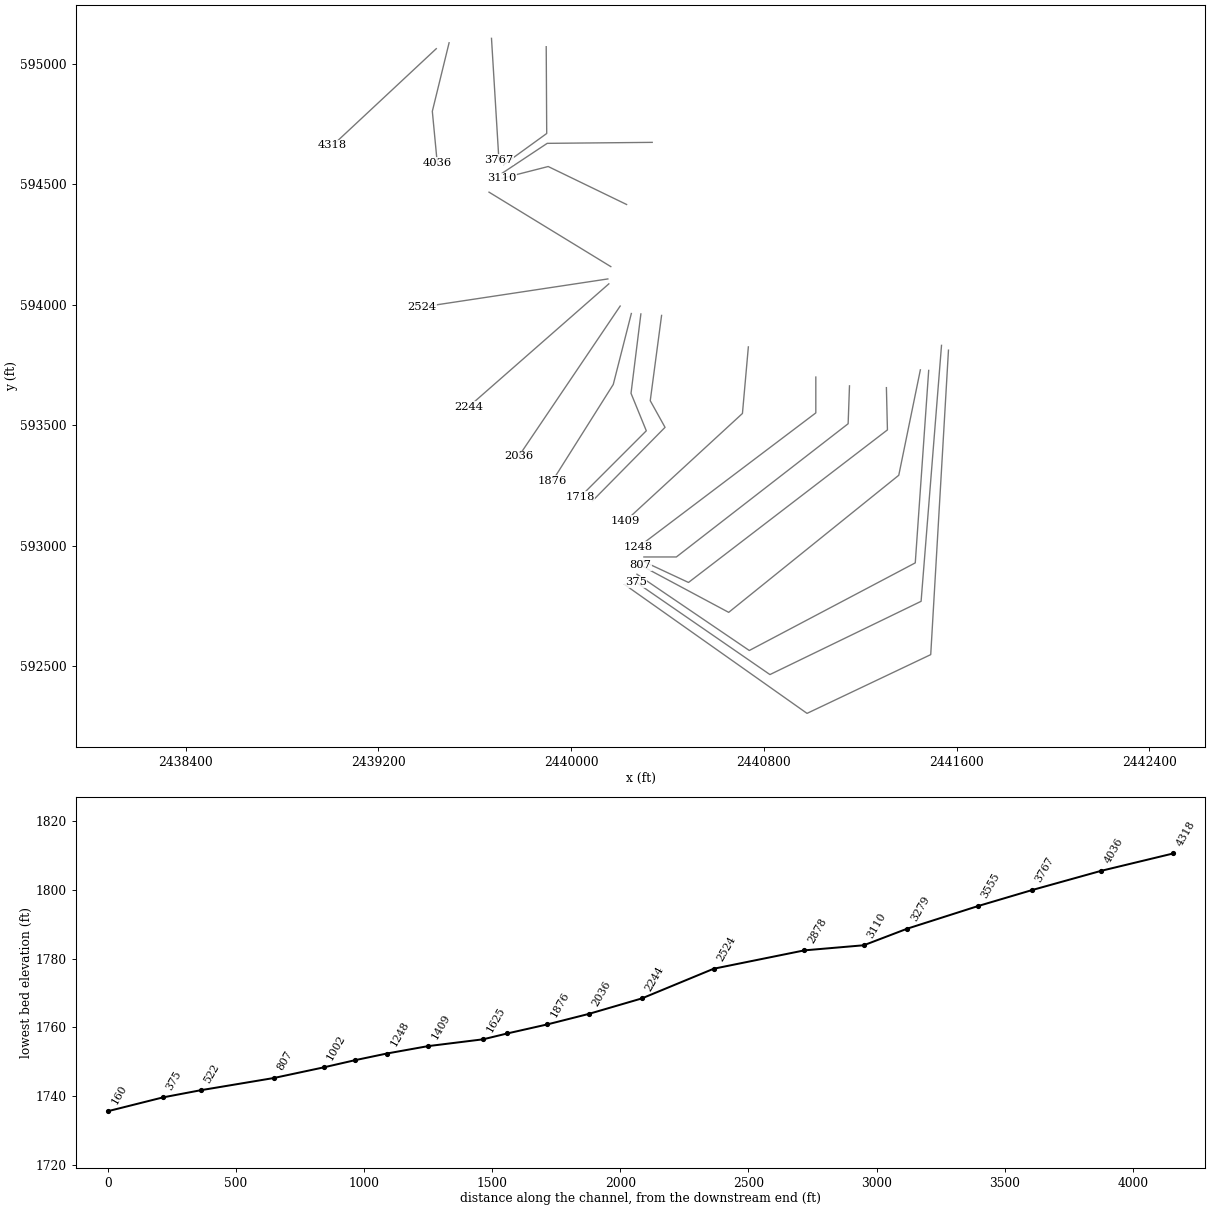
HEC-RAS study SMITHCK.prj: SMITHCK

--- SMITHCK.g01 (geometry) --- (continued)

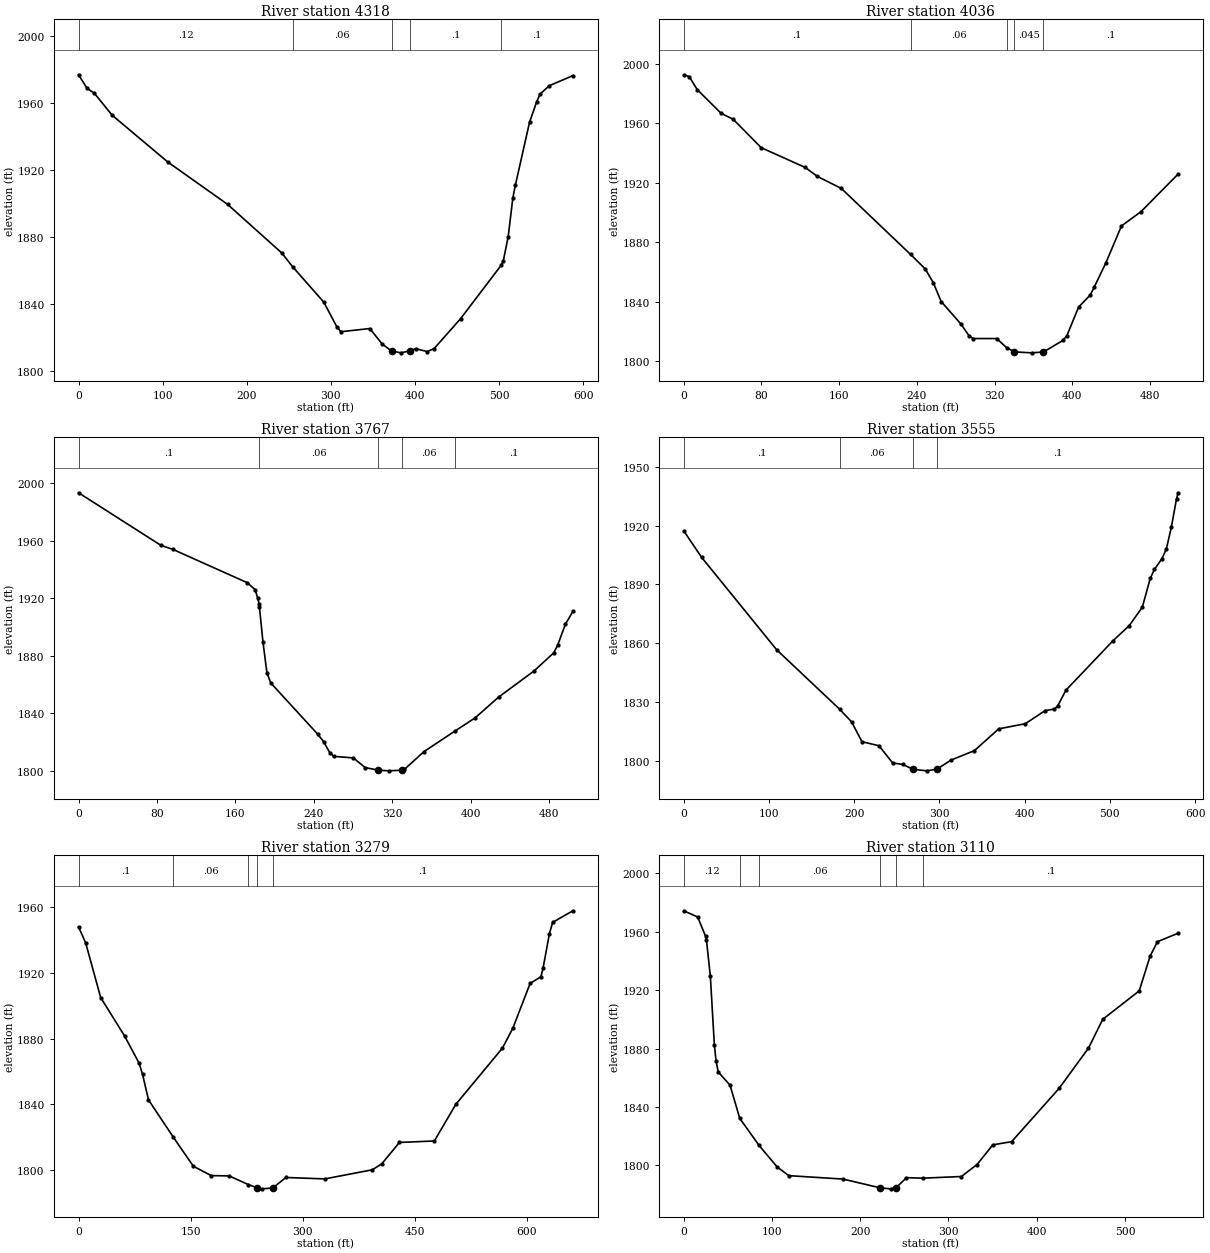
Type RM Length L Ch R = 1 ,4318    ,267.8,282.4,299.1
XS GIS Cut Line= 2
2439439.90790507595063.4369982512439010.15407905594662.333427296
#Sta/Elev= 30
       0 1976.65      10 1968.61    18.9 1965.54    39.9  1952.5   106.2 1924.51
   177.2 1899.25   241.7 1870.19  254.551861.997   291.6 1840.86   307.1 1826.15
     312 1823.18   346.3 1825.08   360.9 1815.93  372.171811.649   383.5 1810.56
  394.071811.763     401 1813.02   414.7 1811.31   422.9 1813.12   454.3 1830.95
  502.571862.836     505 1865.21   510.9 1879.83   516.5 1903.17   519.4 1910.54
   536.3 1948.25   544.8 1960.48   548.7 1964.99   559.7  1970.1   587.9 1976.15
#Mann= 5 ,-1 , 0
       0     .12       0  254.55     .06       0  372.17    .045       0
  394.07      .1       0  502.57      .1       0
Bank Sta=372.17,394.07
XS Rating Curve= 0 ,0
Exp/Cntr(USF)=0,0
Exp/Cntr=0.3,0.1

Type RM Length L Ch R = 1 ,4036    ,268.6,269.1,267.8
XS GIS Cut Line= 3
2439493.11552163595087.9943597382439423.53633075594803.538255846
2439444.00079865594588.661342835
#Sta/Elev= 30
       0 1992.52     5.6 1991.32    13.9 1982.58    38.6 1966.53    50.9 1962.61
    79.8 1943.47     125  1930.2   137.4  1924.2   162.1 1916.11  233.481871.669
   248.6 1861.89   256.8 1852.69     265 1839.97   285.6 1824.61   293.8 1816.74
   297.9 1815.11     322 1815.09  332.451808.937  340.291806.132   358.1 1805.49
  370.19 1806.05   390.3 1813.88   394.3    1817   406.3 1836.21   418.4 1844.41
   422.4 1849.61   434.5 1866.12   450.5 1890.85   470.6 1900.47   508.7 1925.68
#Mann= 5 ,-1 , 0
       0      .1       0  233.48     .06       0  332.45      .1       0
  340.29    .045       0  370.19      .1       0
Bank Sta=340.29,370.19
XS Rating Curve= 0 ,0
Exp/Cntr(USF)=0,0
Exp/Cntr=0.3,0.1

Type RM Length L Ch R = 1 ,3767    ,212.3,211.8,210.1
XS GIS Cut Line= 2
2439669.10994562595106.4123808532439699.80664748594602.986470369
#Sta/Elev= 30
       0 1993.48      84 1956.89    96.1  1954.1   172.2 1930.86   180.2 1925.98
   182.7 1920.35   184.2 1916.13  184.56 1913.72   188.2 1889.35   192.2 1868.08
   196.2 1861.01   244.3 1825.22     250 1820.22   256.3 1812.61   260.4 1809.97
   280.4 1808.91   292.4 1802.19  305.481800.422   316.5 1799.91  329.971800.343
   332.5 1800.94   352.5 1813.33  384.221827.679   404.6 1836.77   428.6 1851.24
   464.7 1869.41   484.7 1881.94   488.8 1887.31   496.8 1902.04   504.4 1910.93
#Mann= 5 ,-1 , 0
       0      .1       0  184.56     .06       0  305.48    .045       0
  329.97     .06       0  384.22      .1       0
Bank Sta=305.48,329.97
XS Rating Curve= 0 ,0
Exp/Cntr(USF)=0,0
Exp/Cntr=0.3,0.1

Type RM Length L Ch R = 1 ,3555    ,298.9,275.6,246.8
XS GIS Cut Line= 3
2439896.26553937595071.6227854132439898.31198616 594711.44815027
2439720.27111538594582.522002463
#Sta/Elev= 30
       0 1917.29    21.1 1903.75   109.1 1856.79  183.131826.494   197.1 1820.07
   209.1 1810.05   229.1    1808   245.1 1799.27   257.1 1798.48   269.1 1796.03
   285.1 1795.24   297.1 1796.09   313.7 1800.72   341.1 1805.53   369.6 1816.59
   400.7 1819.18     424 1825.86     435 1826.68   438.8 1828.26   448.6 1836.32
   503.8 1861.46   522.7 1869.06   538.1 1878.46   547.4 1893.13   552.3 1897.68
   561.1 1903.12   566.3 1908.11   572.1 1919.08   578.2  1933.5     580 1936.64
#Mann= 4 ,-1 , 0
       0      .1       0  183.13     .06       0   269.1    .045       0
   297.1      .1       0
Bank Sta=269.1,297.1
XS Rating Curve= 0 ,0
Exp/Cntr(USF)=0,0
Exp/Cntr=0.3,0.1

Type RM Length L Ch R = 1 ,3279    ,177,169.5,163
XS GIS Cut Line= 3
2440336.25159935594674.6121080392439900.35843296594670.519214458
2439712.08532822594545.685960232
#Sta/Elev= 30
       0 1947.87     9.6    1938    29.6 1904.93    61.6 1881.59    80.9 1865.15
    85.6 1858.42    93.6 1842.74  126.46 1820.35   153.6 1802.44   177.6 1796.71
   201.6 1796.55  227.231791.281   239.4 1789.27   245.6 1788.68     260  1789.2
   277.6 1795.58   329.6 1794.72   393.3 1800.26   405.9 1803.88   429.6 1816.88
   476.3 1817.76   505.1 1840.07   567.5 1874.23   581.4 1886.31   604.5 1913.49
   618.9 1917.57   621.8 1922.69   630.4 1943.84   634.7 1950.65   661.8 1957.67
#Mann= 5 ,-1 , 0
       0      .1       0  126.46     .06       0  227.23      .1       0
   239.4    .045       0     260      .1       0
Bank Sta=239.4,260
XS Rating Curve= 0 ,0
Exp/Cntr(USF)=0,0
Exp/Cntr=0.3,0.1

Type RM Length L Ch R = 1 ,3110    ,233.1,231.7,230.2
XS GIS Cut Line= 3
2440229.83636624594416.7598124252439904.45132654594574.336215301
2439712.08532822594525.221492327
#Sta/Elev= 30
       0 1974.43    15.8 1970.17    24.7 1957.05    25.8 1954.17    30.2 1929.46
    34.7 1882.56    36.7 1871.38    39.1 1863.98    52.5 1854.89   63.521832.134
   85.381813.614   105.8 1798.92   119.1  1792.9   180.4 1790.56  222.691784.522
   234.3 1783.86  240.291784.428   252.4  1791.5  270.821791.178   314.6 1792.31
   332.4 1800.54   350.2 1813.99   371.6 1816.22   425.3 1852.68   458.6 1880.29
   474.8 1900.05   516.1 1919.54   528.5 1943.44   536.8 1953.25   560.1 1959.02
#Mann= 6 ,-1 , 0
       0     .12       0   63.52      .1       0   85.38     .06       0
  222.69    .045       0  240.29     .06       0  270.82      .1       0
Bank Sta=222.69,240.29
XS Rating Curve= 0 ,0
Exp/Cntr(USF)=0,0
Exp/Cntr=0.3,0.1

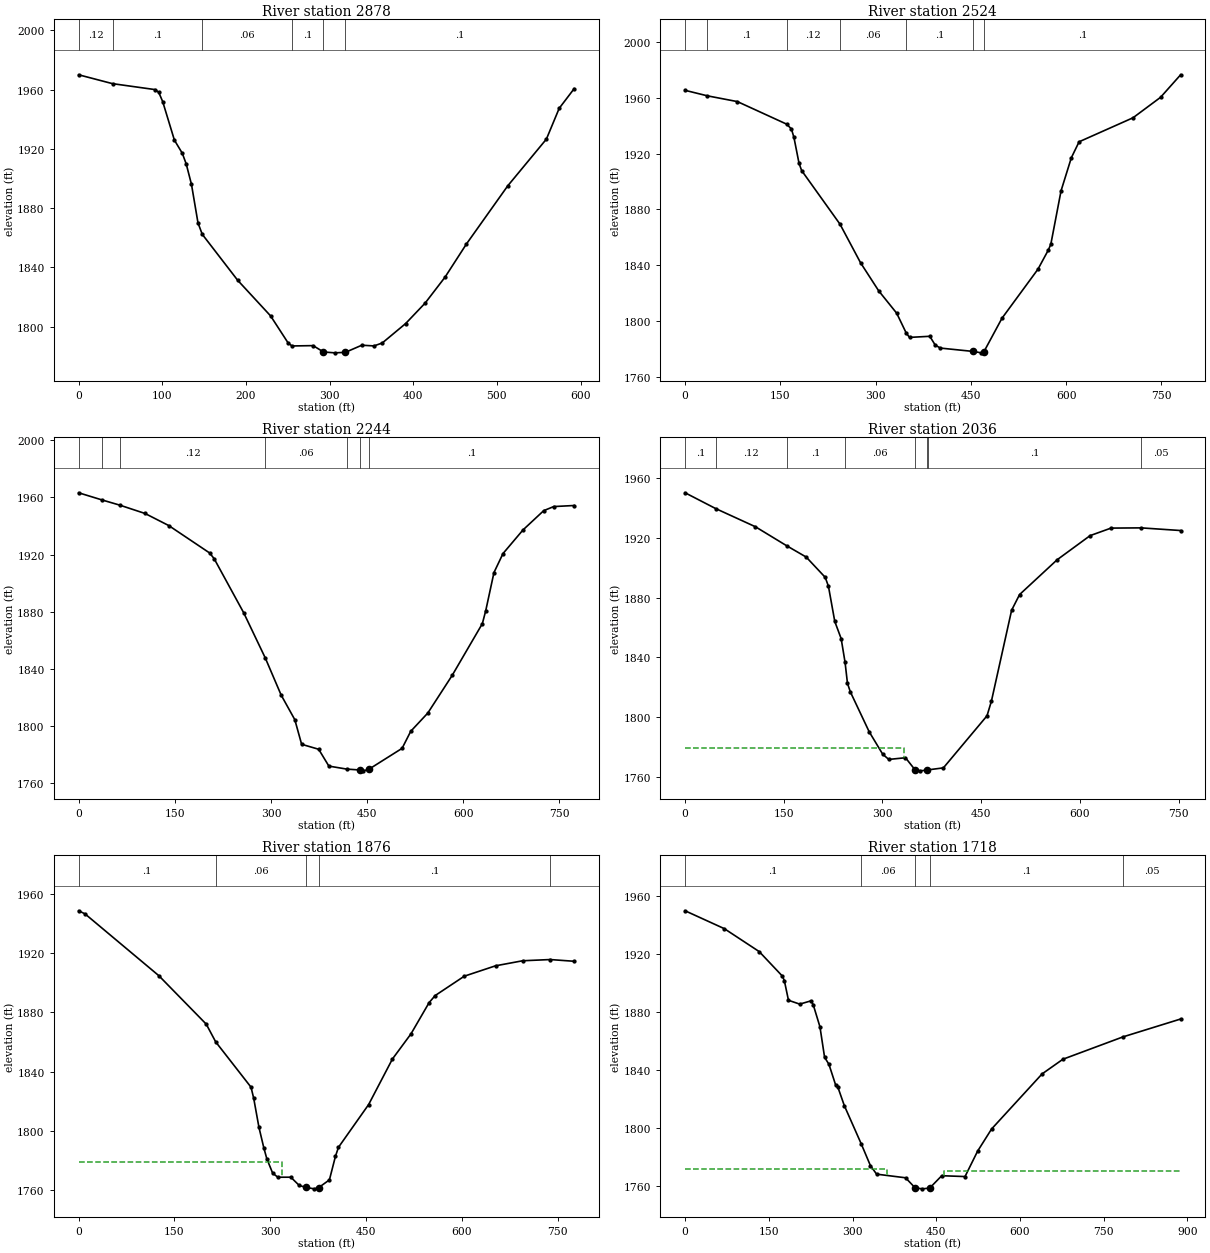
Type RM Length L Ch R = 1 ,2878    ,346.2,354,363.9
XS GIS Cut Line= 2
2440164.35006894594158.9075168122439658.87771167 594467.92098219
#Sta/Elev= 30
       0 1970.02    40.51964.032    91.5 1960.01    95.8 1958.12   100.5 1951.91
   114.5 1925.91   123.9 1917.09   128.6 1909.88   134.9 1896.07   142.7 1870.03
  147.791862.372   190.1 1831.37   229.5 1807.29   250.5    1789  255.081787.021
   280.3 1787.25  292.721782.958   306.2 1782.38  318.821782.703   338.5 1787.52
   353.1 1787.05     363 1789.04   390.9 1802.13   414.2 1815.93     438 1833.44
   463.6 1855.83     513 1895.08   559.2 1926.61   574.5 1947.39   592.4 1960.66
#Mann= 6 ,-1 , 0
       0     .12       0    40.5      .1       0  147.79     .06       0
  255.08      .1       0  292.72    .045       0  318.82      .1       0
Bank Sta=292.72,318.82
XS Rating Curve= 0 ,0
Exp/Cntr(USF)=0,0
Exp/Cntr=0.3,0.1

Type RM Length L Ch R = 1 ,2524    ,274.5,280.4,288.9
XS GIS Cut Line= 2
 2440152.0713882594107.7463470472439380.56094815593991.098879984
#Sta/Elev= 30
       0  1965.4   35.251961.437    82.4 1957.31  159.781941.166   167.4 1937.71
   171.4 1931.58   179.4 1913.05   183.5 1907.85  243.881869.387   276.3 1841.66
   304.8 1821.56   333.2 1805.47  348.191791.245   353.4 1788.12   385.3 1788.91
   393.8 1782.65   401.9 1780.46  453.691778.042   466.6 1777.04  470.691777.958
     499 1801.88   555.6 1837.03   571.8 1850.67   575.9 1854.96     592 1893.31
   608.2 1917.04   620.4 1928.48   705.3  1945.7   748.6 1960.36   780.3 1976.56
#Mann= 7 ,-1 , 0
       0     .12       0   35.25      .1       0  159.78     .12       0
  243.88     .06       0  348.19      .1       0  453.69    .045       0
  470.69      .1       0
Bank Sta=453.69,470.69
XS Rating Curve= 0 ,0
Exp/Cntr(USF)=0,0
Exp/Cntr=0.3,0.1

Type RM Length L Ch R = 1 ,2244    ,206.7,207.3,212.1
XS GIS Cut Line= 2
2440156.16428178594087.2818791412439574.97339325593577.716628285
#Sta/Elev= 30
       0  1963.3   36.851958.228    64.21954.635   103.6 1948.79   140.5 1940.34
   204.2 1921.15   211.3 1917.16   257.4 1879.24  291.211847.434   315.9 1821.49
   337.2 1804.24   347.8 1787.02   374.4 1783.53   390.3 1771.73  418.391769.616
  438.221769.027   443.5 1768.41  452.231769.378   504.5 1784.18     518 1796.13
   544.6 1808.91   582.6 1835.29   629.7 1871.59     635 1880.74   647.8 1907.39
   661.9  1920.7   693.1 1937.26   725.4 1950.78   741.1 1953.64   772.9 1954.38
#Mann= 7 ,-1 , 0
       0     .12       0   36.85      .1       0    64.2     .12       0
  291.21     .06       0  418.39      .1       0  438.22    .045       0
  452.23      .1       0
Bank Sta=438.22,452.23
XS Rating Curve= 0 ,0
Exp/Cntr(USF)=0,0
Exp/Cntr=0.3,0.1

Type RM Length L Ch R = 1 ,2036    ,160.3,160.8,161.1
XS GIS Cut Line= 2
2440203.23255796593995.191773565 2439781.6645191593371.025502436
#Sta/Elev= 30
       0 1950.17   46.441939.601   106.9 1927.41  154.231914.726   184.1  1907.1
     213 1893.51   217.9  1887.5   227.5 1863.98   237.2 1852.48  243.121836.648
   246.8 1822.52   251.2 1816.77   279.8 1790.07   300.4 1775.01   309.6 1771.55
     335 1772.67   349.4 1764.64   357.8  1763.9   367.31764.409  369.821764.586
   392.6 1765.89   458.9 1800.77   465.6  1810.6   496.3  1871.5   508.4 1881.99
   565.6 1905.34   615.6 1921.47   647.4 1926.51   693.2 1926.66   753.2 1924.88
#Mann= 8 ,-1 , 0
       0      .1       0   46.44     .12       0  154.23      .1       0
  243.12     .06       0   349.4    .045       0   367.3     .06       0
  369.82      .1       0   693.2     .05       0
#XS Ineff= 2 , 0
           332.8 1778.88
Permanent Ineff=
       F       F
Bank Sta=349.4,367.3
XS Rating Curve= 0 ,0
Exp/Cntr(USF)=0,0
Exp/Cntr=0.3,0.1

Type RM Length L Ch R = 1 ,1876    ,142,157.4,173.6
XS GIS Cut Line= 3
2440249.58987331593964.2375532092440174.58230289593669.806733862
      2439922.93      593270.509
#Sta/Elev= 30
       0 1948.57     9.9 1946.51   125.5 1904.78   199.8 1872.04  214.581860.075
   269.9 1829.48   274.1 1821.95   282.3 1802.38   289.9 1788.58   294.7 1781.05
   303.8 1771.44   311.9 1768.71   332.2 1768.73   345.4 1763.14  356.311761.778
     369 1760.87  375.711761.672   392.6 1766.91   402.1 1782.88   406.8 1788.91
     454 1817.76   491.3 1848.54   520.3 1865.47   548.7 1886.57   558.1 1891.32
   603.8 1904.42   652.7 1911.42   695.2 1914.83  738.341915.648   775.8 1914.48
#Mann= 5 ,-1 , 0
       0      .1       0  214.58     .06       0  356.31    .045       0
  375.71      .1       0  738.34     .05       0
#XS Ineff= 2 , 0
          318.08 1778.89
Permanent Ineff=
       F       F
Bank Sta=356.31,375.71
XS Rating Curve= 0 ,0
Exp/Cntr(USF)=0,0
Exp/Cntr=0.5,0.3

Type RM Length L Ch R = 1 ,1718    ,92.7,93.5,98.2
XS GIS Cut Line= 4
2440289.18332317593962.4486249162440248.25438736593632.970691631
2440311.69423786593477.4407355472440037.47036793593203.216865608
#Sta/Elev= 30
       0 1949.75    70.3 1937.43   132.8 1921.63   174.2 1904.79   177.8 1901.64
   185.2  1888.1   205.4 1885.45   225.5 1887.71   229.5 1885.11   241.6 1869.82
   249.9 1848.83   257.7    1844   269.8 1829.64   273.9 1828.04   285.3  1815.5
  315.591789.173     332 1774.23   343.1 1768.34     395 1765.83   412.2 1758.87
   425.2 1758.22   438.2 1758.74   459.8 1767.26   501.5 1766.68   524.1 1784.21
   549.1 1799.45   639.6 1837.39   676.9 1847.49   784.61862.902   887.8  1875.2
#Mann= 5 ,-1 , 0
       0      .1       0  315.59     .06       0   412.2    .045       0
   438.2      .1       0   784.6     .05       0
#XS Ineff= 2 , 0
          361.93    1772  464.29         1770.49
Permanent Ineff=
       F       F
Bank Sta=412.2,438.2
XS Rating Curve= 0 ,0
Exp/Cntr(USF)=0,0
Exp/Cntr=0.5,0.3

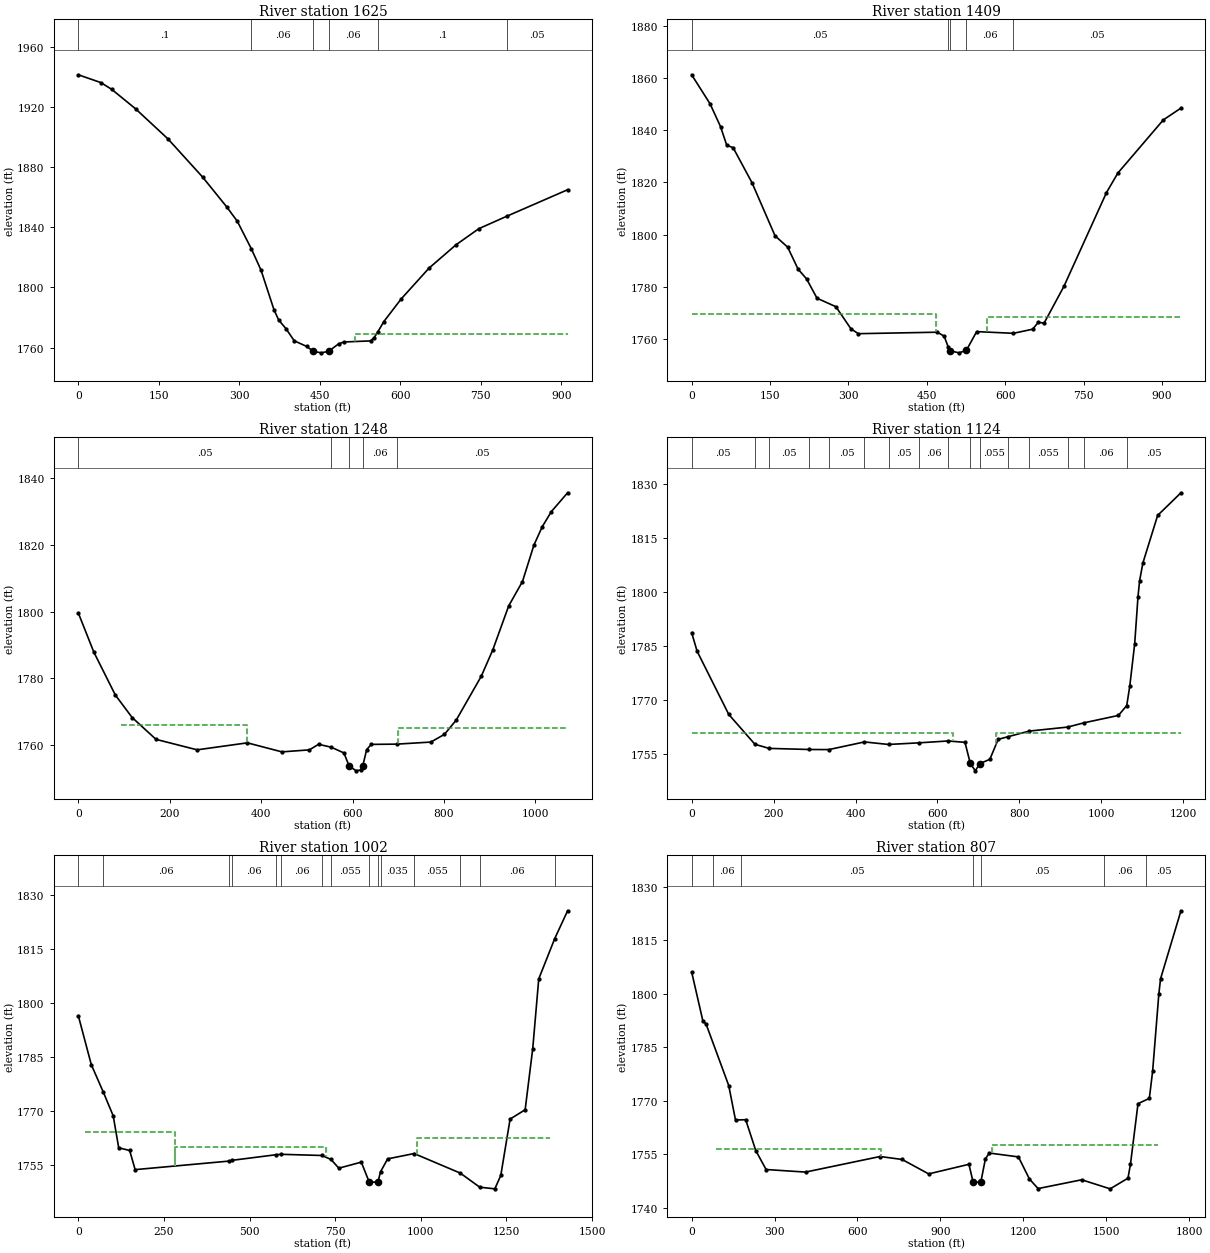
Type RM Length L Ch R = 1 ,1625    ,234.7,215.7,189
XS GIS Cut Line= 4
2440375.13408837593956.3092845442440328.06581219593602.273989772
2440389.45921591593491.7658630812440088.63153769593186.845291283
#Sta/Elev= 30
       0 1941.42      42 1936.23    62.2 1931.74   106.6 1918.83   167.1 1898.78
   231.7 1873.38   276.2 1853.73   296.2 1844.08  322.651825.578   340.6 1811.43
   364.6 1785.25   373.4 1778.34   387.1 1772.57   402.4 1764.53   425.3 1760.84
   438.1 1757.51   452.8 1756.53   466.5 1757.55   485.1 1762.49   494.8 1763.74
   544.6 1764.48   551.4 1766.65   558.5 1770.66   569.4 1777.31   601.5 1792.28
   653.6 1812.86     704  1828.4   746.5  1839.1  798.951847.424   911.9 1864.98
#Mann= 6 ,-1 , 0
       0      .1       0  322.65     .06       0   438.1    .045       0
   466.5     .06       0   558.5      .1       0  798.95     .05       0
#XS Ineff= 2 , 0
                          516.33         1768.78
Permanent Ineff=
       F       F
Bank Sta=438.1,466.5
XS Rating Curve= 0 ,0
Exp/Cntr(USF)=0,0
Exp/Cntr=0.5,0.3

Type RM Length L Ch R = 1 ,1409    ,162.1,160.6,158.7
XS GIS Cut Line= 3
2440735.29188033593825.6202168682440710.73451884593549.349900139
2440225.72662948593103.224499791
#Sta/Elev= 30
       0 1861.38    35.1 1850.27    55.2 1841.49    67.2 1834.28    79.3 1833.39
   115.4 1819.94   159.6 1799.49   183.7 1795.16   203.7 1786.68   219.8 1782.98
   239.9 1775.52     276 1772.27   304.8 1763.77     319  1761.9   470.3 1762.47
   483.2 1760.93  490.941756.801     494 1755.39   511.3 1754.54   525.6 1755.47
   545.4  1762.7  615.671762.039   652.6 1763.63   663.4 1766.32   674.3 1765.91
   712.3 1780.06   793.8 1816.12   815.6 1823.63   902.5 1844.03   936.3 1848.58
#Mann= 5 ,-1 , 0
       0     .05       0  490.94     .06       0     494    .045       0
   525.6     .06       0  615.67     .05       0
#XS Ineff= 2 , 0
          468.09 1769.43  565.96         1768.29
Permanent Ineff=
       F       F
Bank Sta=494,525.6
XS Rating Curve= 0 ,0
Exp/Cntr(USF)=0,0
Exp/Cntr=0.3,0.1

Type RM Length L Ch R = 1 ,1248    ,124,124.9,125.2
XS GIS Cut Line= 3
2441015.29576939593700.4893997342441015.29576939593551.707945823
2440279.81009157 592995.88289159
#Sta/Elev= 30
       0 1799.58    33.8 1787.93      81 1775.05   117.8 1768.33     170  1761.8
     260 1758.67   369.9 1760.76   445.5 1758.06   505.7 1758.66   525.7 1760.32
  553.16 1759.47   581.2 1757.74   592.6 1753.84   608.2 1752.39   618.3 1752.68
  622.35 1753.85     631 1758.73     641  1760.3  696.891760.373   771.4 1760.99
   801.1 1763.29   826.8 1767.53   881.7 1780.66   906.8 1788.49   941.8 1801.71
   971.9 1808.99     997 1819.89  1015.2 1825.38  1035.2 1829.91  1070.7 1835.52
#Mann= 5 ,-1 , 0
       0     .05       0  553.16     .06       0   592.6    .045       0
  622.35     .06       0  696.89     .05       0
#XS Ineff= 2 ,-1
   94.11  368.72 1766.19  699.52  1070.7 1765.06
Permanent Ineff=
       F       F
Bank Sta=592.6,622.35
XS Rating Curve= 0 ,0
Exp/Cntr(USF)=0,0
Exp/Cntr=0.5,0.3

Type RM Length L Ch R = 1 ,1124    ,123,121.2,123.3
XS GIS Cut Line= 4
2441155.06917729593663.928574377 2441149.4547828593506.725528735
2440436.42668293592953.7076717462440301.68121524592953.707671746
#Sta/Elev= 30
       0 1788.71    13.3 1783.56    90.6 1766.06  154.461757.785  189.261756.654
  287.59 1756.35  334.911756.325  421.761758.443  480.561757.744  555.94  1758.2
   626.21758.713   667.2 1758.33  680.181752.488   692.5 1750.44  703.131752.429
   727.9 1753.63   748.2 1759.15  771.851759.884  824.281761.455  917.491762.551
  958.461763.758  1041.7 1765.78 1062.061768.511  1069.5 1773.93  1081.5 1785.65
  1089.5 1798.62  1093.5  1803.1  1101.5    1808  1137.5 1821.17  1194.4 1827.44
#Mann= 16 ,-1 , 0
       0     .05       0  154.46     .06       0  189.26     .05       0
  287.59     .06       0  334.91     .05       0  421.76     .06       0
  480.56     .05       0  555.94     .06       0   626.2    .055       0
  680.18    .045       0  703.13    .055       0  771.85     .06       0
  824.28    .055       0  917.49     .05       0  958.46     .06       0
 1062.06     .05       0
#XS Ineff= 2 , 0
           637.5    1761   742.5            1761
Permanent Ineff=
       F       F
Bank Sta=680.18,703.13
XS Rating Curve= 0 ,0
Exp/Cntr(USF)=0,0
Exp/Cntr=0.5,0.3

Type RM Length L Ch R = 1 ,1002    ,195.6,195.1,195.9
XS GIS Cut Line= 4
2441308.28826402593656.5317971712441312.56687589593481.108710771
2440486.79478624592847.8741549822440294.25725239592937.725004114
#Sta/Elev= 30
       0  1796.5    37.9 1782.89   73.221775.206   101.9 1768.65   117.9 1759.79
   149.9 1759.03   165.9 1753.71  440.94 1756.09  447.971756.285  575.811757.834
  592.761757.967  710.691757.645  737.56 1756.56   760.6 1754.11   826.2 1755.79
  849.381750.243  874.681750.237  882.351753.117   903.2  1756.7  980.441758.182
 1115.31 1752.74 1171.941748.827  1216.1 1748.37  1233.5  1752.1  1260.7 1767.77
  1304.6 1770.35  1326.8 1787.37  1344.3 1806.73 1391.061817.956  1428.6 1825.67
#Mann= 15 ,-1 , 0
       0     .05       0   73.22     .06       0  440.94    .055       0
  447.97     .06       0  575.81     .05       0  592.76     .06       0
  710.69     .05       0  737.56    .055       0  849.38    .045       0
  874.68    .055       0  882.35    .035       0  980.44    .055       0
 1115.31     .05       0 1171.94     .06       0 1391.06     .05       0
#XS Ineff= 3 ,-1
   19.72  282.63 1764.07  282.63  722.71 1759.98  989.58 1377.36 1762.38
Permanent Ineff=
       F       F       F
Bank Sta=849.38,874.68
XS Rating Curve= 0 ,0
Exp/Cntr(USF)=0,0
Exp/Cntr=0.5,0.3

Type RM Length L Ch R = 1 ,807     ,285.3,285.2,279.5
XS GIS Cut Line= 4
2441449.24955768593730.4053545512441359.63160639593292.849788779
2440653.66064892592723.7944109422440285.70002866 592920.61055666
#Sta/Elev= 30
       0  1806.1    40.3 1792.48    52.6 1791.41   134.2 1774.24   158.7 1764.57
   195.5 1764.66   232.2 1755.97   269.4 1750.69   412.1 1749.97   681.9 1754.34
   761.6 1753.51   857.7 1749.46  1003.4 1752.15  1018.41747.224  1046.31747.093
  1063.1  1753.7  1077.3 1755.31  1182.5 1754.23  1222.4 1748.03  1253.7 1745.34
  1411.5 1747.81  1514.5 1745.27    1579 1748.26  1588.1 1752.23  1615.3 1769.16
  1656.3 1770.65  1668.2 1778.25  1690.7 1799.97  1696.9  1804.2  1770.7 1823.27
#Mann= 7 ,-1 , 0
       0     .05       0   77.04     .06       0  177.65     .05       0
  1018.4    .045       0  1046.3     .05       0 1490.81     .06       0
 1645.16     .05       0
#XS Ineff= 2 ,-1
   88.51  686.54 1756.41 1085.68  1689.3  1757.6
Permanent Ineff=
       F       F
Bank Sta=1018.4,1046.3
XS Rating Curve= 0 ,0
Exp/Cntr(USF)=0,0
Exp/Cntr=0.3,0.1

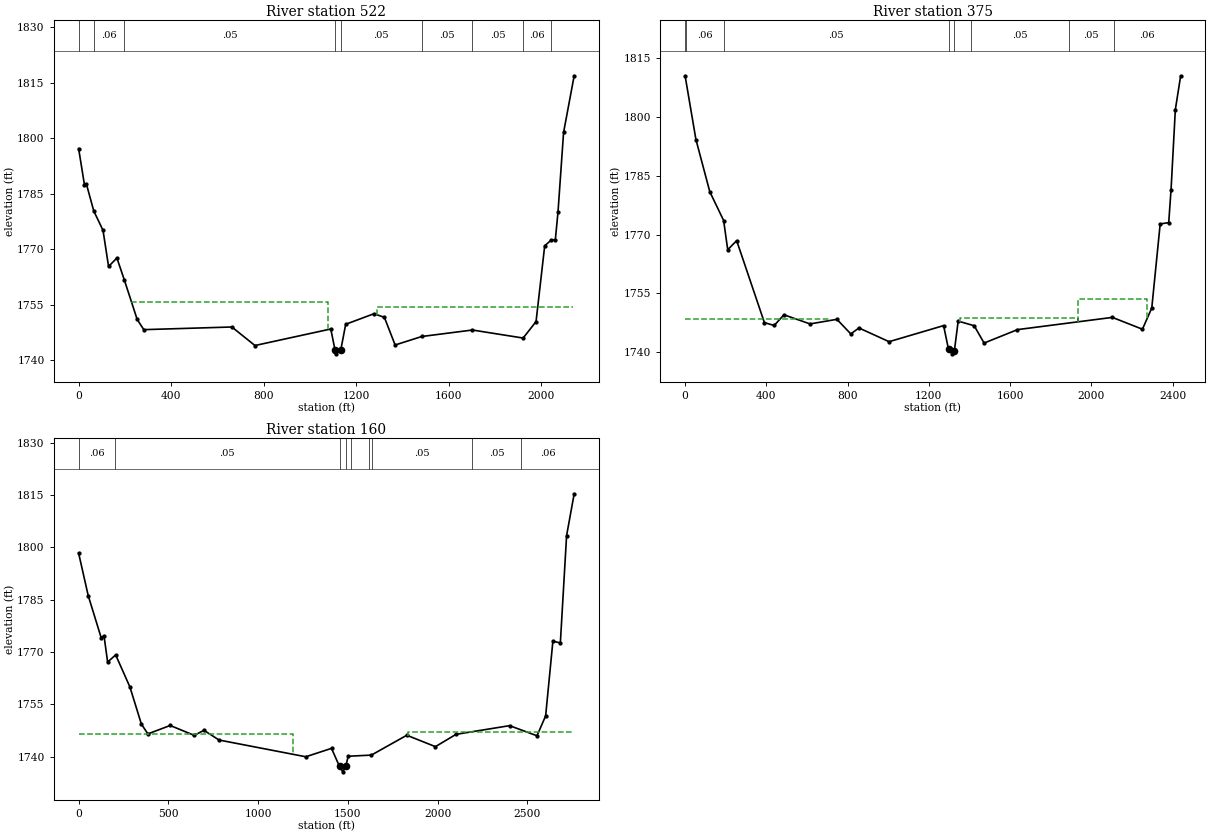
Type RM Length L Ch R = 1 ,522     ,148.7,146.6,146
XS GIS Cut Line= 4
2441483.81291014593728.098819839 2441428.0893962592929.167780387
2440739.23288619592565.4857719952440272.86419307 592882.10304989
#Sta/Elev= 30
       0 1797.22    25.3 1787.38    33.3 1787.72    65.4 1780.36   105.5 1775.11
   129.5 1765.34   165.6 1767.64   198.4 1761.56   253.3 1751.01   281.9 1748.26
   662.8 1748.98   762.7 1743.97  1090.7 1748.44  1108.71742.871  1114.4 1741.72
  1134.31742.869  1155.2 1749.71  1277.7 1752.57  1322.6 1751.58    1369 1744.11
  1484.4 1746.41  1703.4 1748.16  1922.7 1745.99  1978.6 1750.44    2016 1770.93
    2042 1772.37  2062.1 1772.63  2073.6 1780.11  2097.7  1801.6  2143.5 1816.91
#Mann= 9 ,-1 , 0
       0     .05       0    65.4     .06       0   198.4     .05       0
  1108.7    .045       0  1134.3     .05       0  1484.4     .05       0
  1703.4     .05       0  1922.7     .06       0    2042     .05       0
#XS Ineff= 2 ,-1
  230.74 1078.741755.735 1290.51 2137.191754.406
Permanent Ineff=
       F       F
Bank Sta=1108.7,1134.3
XS Rating Curve= 0 ,0
Exp/Cntr(USF)=0,0
Exp/Cntr=0.3,0.1

Type RM Length L Ch R = 1 ,375     ,216.5,215.7,216
XS GIS Cut Line= 4
 2441537.0382914593832.023765278 2441452.2935304592769.657879708
2440824.87892885592465.5538636512440267.88841523592849.685252354
#Sta/Elev= 30
       0 1810.37    53.3 1794.16   121.5 1780.89   189.7 1773.56   209.8 1766.14
   253.9 1768.43   390.4  1747.6   438.5 1746.86   486.7 1749.58   615.1 1747.26
   747.5 1748.43   815.7 1744.72   855.8 1746.23  1004.3 1742.74  1272.6 1746.83
  1296.81740.804  1314.5 1739.65  1325.6 1740.38  1344.4 1747.97  1423.1  1746.8
    1472 1742.39  1636.4 1745.81  2103.5 1748.92  2251.5 1745.91  2297.5 1751.31
  2338.9 1772.68  2380.9 1773.03  2392.4 1781.39  2413.5 1801.76  2439.6 1810.32
#Mann= 8 ,-1 , 0
       0     .05       0    3.11     .06       0  189.21     .05       0
  1296.8    .045       0  1325.6     .05       0 1409.26     .05       0
 1889.49     .05       0 2109.35     .06       0
#XS Ineff= 3 ,-1
       0  710.071748.573 1354.12 1933.651748.842 1933.65  2272.4 1753.56
Permanent Ineff=
       F       F       F
Bank Sta=1296.8,1325.6
XS Rating Curve= 0 ,0
Exp/Cntr(USF)=0,0
Exp/Cntr=0.3,0.1

Type RM Length L Ch R = 1 ,160     ,,,
XS GIS Cut Line= 4
2441565.91883423593812.1042746662441492.26857415592548.371324542
2440978.83515054592304.4904483262440221.52085071592839.316931255
#Sta/Elev= 30
       0  1798.3    53.3 1786.15   125.4 1774.11   141.5 1774.61   161.5 1767.09
   206.4 1769.14   285.7 1759.96   349.8  1749.3   385.9 1746.49   510.1 1748.91
     644 1746.08   698.4 1747.52   782.5 1744.74  1265.9 1739.94  1409.2 1742.35
  1453.81737.154  1472.3 1735.62  1489.21737.358  1502.3 1740.09  1631.4 1740.42
  1828.7 1746.11  1988.2 1742.84    2103 1746.37  2401.5 1748.86  2554.2 1745.96
  2602.4 1751.65  2642.8 1773.07  2684.4 1772.58  2719.1  1803.3  2761.4 1815.33
#Mann= 9 ,-1 , 0
       0     .06       0  202.24     .05       0  1453.8    .045       0
  1489.2     .05       0 1515.27     .05       0 1618.08     .05       0
 1635.95     .05       0 2194.03     .05       0 2463.92     .06       0
#XS Ineff= 2 , 0
         1197.031746.329 1833.34        1747.008
Permanent Ineff=
       F       F
Bank Sta=1453.8,1489.2
XS Rating Curve= 0 ,0
Exp/Cntr(USF)=0,0
Exp/Cntr=0.3,0.1
LCMann Table=0

Chan Stop Cuts=-1
Use User Specified Reach Order=0
Composite Channel Slope=5